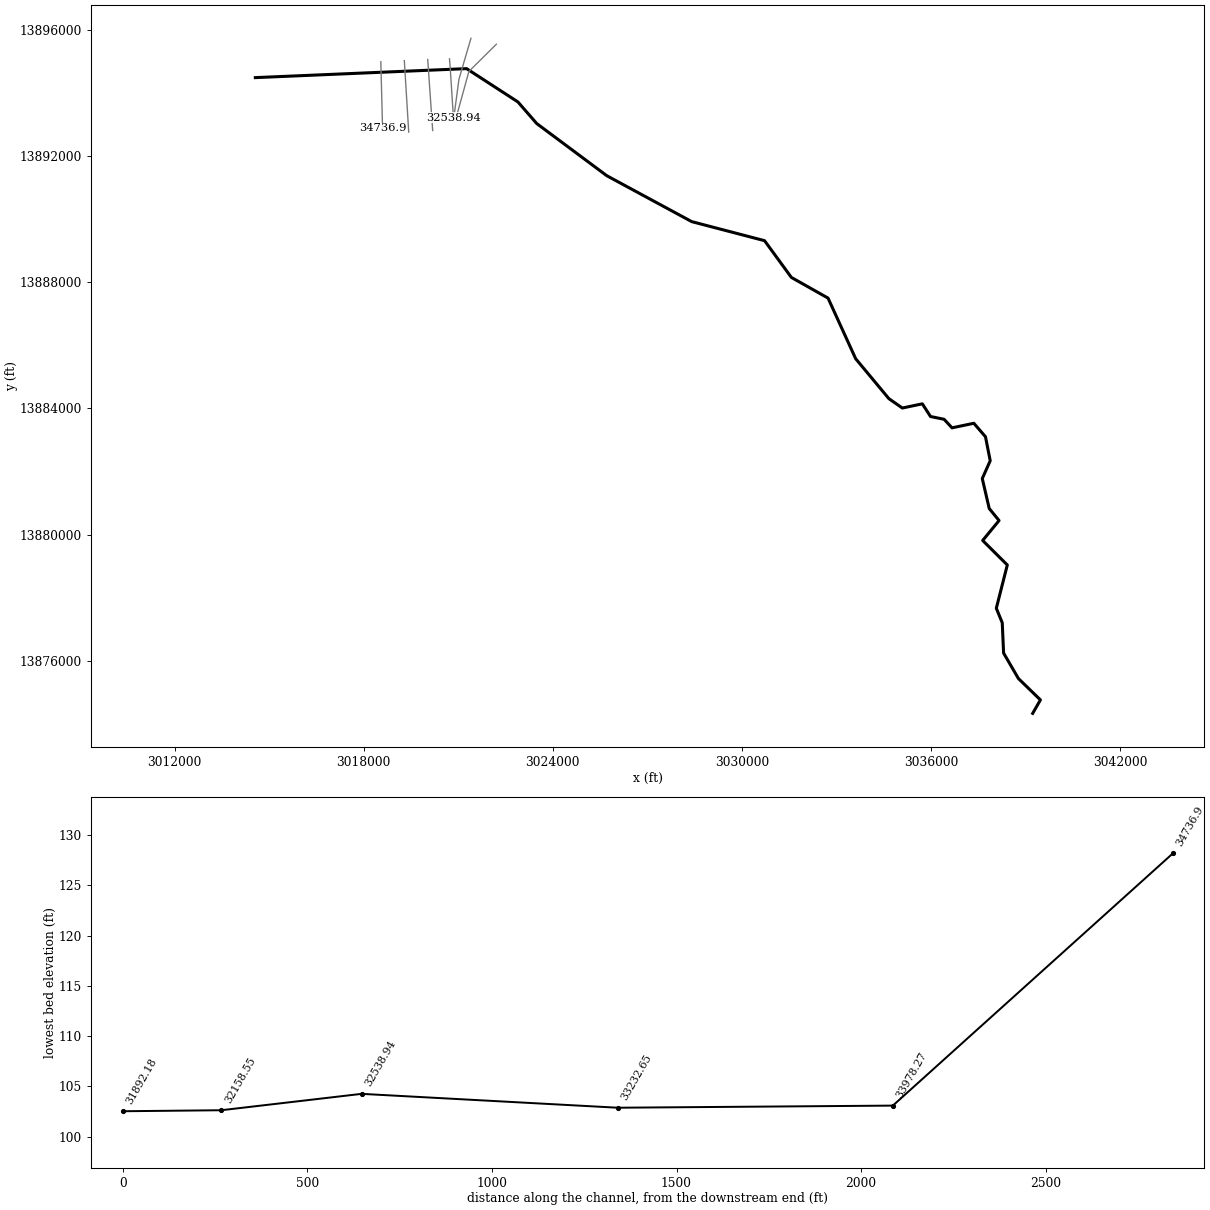
--- U106-00-00.prj (project) ---

Proj Title=U106-00-00 2019 (Re-Study)
Current Plan=p02
Default Exp/Contr=0.3,0.1
English Units
Geom File=g01
Flow File=f01
Flow File=f02
Flow File=f03
Plan File=p01
Plan File=p02
Plan File=p03
Y Axis Title=Elevation
X Axis Title(PF)=Main Channel Distance
X Axis Title(XS)=Station
BEGIN DESCRIPTION:
Horsepen Creek (U106-00-00)
(Flood Hazard & Floodway) Model
10-, 2-, 1-, and 0.2% Events
Filename U106_00_00.prj
Prepared by:  LAN                               Date: 10/29/2012
Reviewed by: HCFCD                         Date: 10/18/2012
STATUS: Final
ADDICKS WATERSHED MODEL UPDATE
HARRIS COUNTY, TEXAS
END DESCRIPTION:
DSS Export Rating Curves= 0
DSS Export Rating Curve Sorted= 0
DSS Export Volume Flow Curves= 0
DXF OffsetX= 0
DXF OffsetY= 0
DXF ScaleX= 1
DXF ScaleY= 10

--- U106-00-00.p02 (plan) ---

Plan Title=Effective Floodway 2019 (Re-Study)
Program Version=4.10
Short Identifier=Eff+ ReStudy FW
Geom File=g01
Flow File=f02
Subcritical Flow
K Sum by GR= 0
Std Step Tol= 0.01
Critical Tol= 0.01
Num of Std Step Trials= 20
Max Error Tol= 0.3
Flow Tol Ratio= 0.001
Split Flow NTrial= 30
Split Flow Tol= 0.02
Split Flow Ratio= 0.02
Log Output Level= 0
Friction Slope Method= 1
Unsteady Friction Slope Method= 2
Unsteady Bridges Friction Slope Method= 1
Parabolic Critical Depth
Global Vel Dist= 0 , 0 , 0
Global Log Level= 0
CheckData=True
Encroach Param=-1 ,0,0, 2
Encroach River=U106-00-00
Encroach Reach=U106-00-00_0006
Encroach Node=34736.9
       1  269.84  384.77
Encroach Node=33978.27
       1  264.87  379.81
Encroach Node=33232.65
       1  264.56  379.37
Encroach Node=32538.94
       1   260.8  380.81
Encroach Node=32158.55
       1  923.88 1053.72
Encroach Node=31892.18
       1 1137.08 1226.85
Encroach Node=31295.21
       1 1726.81 1811.18
Encroach Node=30906.18
       1 2135.01 2227.85
Encroach Node=30251.07
       1 1504.49 1633.14
Encroach Node=30237.72
       1 1496.69 1626.84
Encroach Node=30163.92
       1 1491.71 1597.59
Encroach Node=30145.7
       1 1498.92 1603.83
Encroach Node=29925.7
       1 1157.86 1236.93
Encroach Node=28984.21
       1  647.26  745.22
Encroach Node=28885.46
       1  681.54  774.61
Encroach Node=28808.57
       1  671.22   763.1
Encroach Node=28676.88
       1  666.33  758.32
Encroach Node=28596.48
       1  704.27  799.26
Encroach Node=28491.74
       1  859.12  943.67
Encroach Node=28110.07
       1  753.24  836.46
Encroach Node=27792.54
       1  691.02  782.72
Encroach Node=27664.41
       1   686.1  797.04
Encroach Node=27344.77
       1   769.9  872.46
Encroach Node=27238.83
       1  815.62  965.93
Encroach Node=27203.95
       1  800.64  949.07
Encroach Node=27108.55
       1  793.14  945.59
Encroach Node=27032.86
       1  784.99  915.95
Encroach Node=26660.09
       1  822.81  936.42
Encroach Node=26124.21
       1  681.88  804.95
Encroach Node=24973.88
       1  691.67  819.07
Encroach Node=24659.03
       1  430.29  549.82
Encroach Node=24544.18
       1   443.5  563.09
Encroach Node=24439.49
       1  434.76   554.7
Encroach Node=23995.34
       1  570.86   698.5
Encroach Node=23852.47
       1  515.95  635.62
Encroach Node=23788.41
       1  522.23  641.98
Encroach Node=23712.13
       1  436.61   601.4
Encroach Node=23589.06
       1  374.69  504.58
Encroach Node=23506.34
       1  354.61  489.45
Encroach Node=22853.56
       1  342.96   470.5
Encroach Node=22164.43
       1  822.52  955.83
Encroach Node=22005.4
       1  757.29  921.36
Encroach Node=21941.71
       1  757.29  936.25
Encroach Node=21939.22
       1  757.29  936.25
Encroach Node=21928.05
       1  772.19  921.36
Encroach Node=21901.5
       1  767.22  906.47
Encroach Node=21273.96
       1  752.99  886.54
Encroach Node=20985.72
       1  749.23  908.22
Encroach Node=20274.23
       1 1174.46 1343.75
Encroach Node=20114.5
       1 1121.07  1322.2
Encroach Node=20066.32
       1  1116.1 1317.33
Encroach Node=19978.63
       1 1136.94 1315.46
Encroach Node=19902.81
       1 1135.34 1324.49
Encroach Node=19722.39
       1 1228.51 1407.09
Encroach Node=19379.8
       1 1256.61 1434.16
Encroach Node=19149.03
       1 1218.04 1397.62
Encroach Node=18008.87
       1 1134.98 1319.73
Encroach Node=17829.24
       1 1251.46  1445.5
Encroach Node=17815.82
       1 1232.62  1454.3
Encroach Node=17675.65
       1 1242.43 1469.18
Encroach Node=17659.51
       1  1225.9 1460.08
Encroach Node=17099
       1   495.4  678.25
Encroach Node=16293.39
       1  324.15  503.25
Encroach Node=15604.09
       1 1016.55 1213.61
Encroach Node=15471.62
       1 1286.81 1515.31
Encroach Node=15434.33
       1 1286.81 1500.56
Encroach Node=15350.12
       1 1093.24 1299.83
Encroach Node=15320.28
       1 1088.44 1324.45
Encroach Node=14811.87
       1 1094.56 1269.17
Encroach Node=14194.91
       1 1490.81 1655.17
Encroach Node=14061.19
       1 1452.55 1624.54
Encroach Node=14003.57
       1 1452.55 1619.61
Encroach Node=13646.79
       1 1587.41 1764.46
Encroach Node=13005.42
       1 1340.94 1518.19
Encroach Node=12230.04
       1 1888.42 2070.04
Encroach Node=11675.06
       1 2287.33 2494.55
Encroach Node=11568.75
       1 1769.67 1924.19
Encroach Node=11515.39
       1 1759.75 1914.83
Encroach Node=11005.42
       1 1761.66 1938.85
Encroach Node=10050.94
       1 1144.98 1307.89
Encroach Node=10025.62
       1 1144.98 1303.07
Encroach Node=10009.41
       1 1121.48 1333.94
Encroach Node=9878.908
       1 1141.42 1324.13
Encroach Node=9856.587
       1 1142.32  1330.1
Encroach Node=9832.995
       1 1142.32 1310.13
Encroach Node=9619.335
       1 1114.95 1274.02
Encroach Node=9578.745
       1 1119.92 1284.02
Encroach Node=8794.251
       1 1452.62 1600.98
Encroach Node=8163.752
       1 1574.43 1720.86
Encroach Node=7905.084
       1  1561.4 1720.97
Encroach Node=7388.485
       1 1339.89 1489.23
Encroach Node=7093.843
       1 1425.33 1618.87
Encroach Node=6479.06
       1 1412.58 1717.03
Encroach Node=5787.579
       1 1158.86  1343.4
Encroach Node=5054.988
       1 1131.91 1310.47
Encroach Node=4135.911
       1 1117.45  1310.2
Encroach Node=3194.384
       1 1240.11 1423.77
Encroach Node=3027.574
       1 1072.07 1271.65
Encroach Node=2904.468
       1 1081.69 1286.44
Encroach Node=2393.094
       1 1151.36 1339.31
Encroach Node=1884.233
       1 1017.18 1211.03
Encroach Node=1354.328
       1  911.51 1103.68
Encroach Node=1154.309
       1  798.86 1014.14
Encroach Node=1145.811
       1  798.86 1017.35
Encroach Node=575.5177
       1  480.08  702.47
Computation Interval=1HOUR
Output Interval=1HOUR
Run HTab= 0
Run UNet= 0
Run PostProcess= 0
Run WQNet= 0
UNET Theta= 1
UNET Theta Warmup= 1
UNET ZTol= 0.02
UNET ZSATol= 0.05
UNET MxIter= 20
UNET MaxInSteps= 0
UNET DtIC= 0
UNET DtMin= 0
UNET MaxCRTS= 20
UNET WFStab= 2
UNET SFStab= 1
UNET WFX= 1
UNET SFX= 1
UNET DSS MLevel= 4
UNET DZMax Abort= 100
UNET Convert EG Bridges= 0
UNET Use Existing IB Tables=-1
UNET Froude Reduction=False
UNET Froude Limit= 1
UNET Froude Power= 10
UNET Time Slicing=0,0, 5
UNET Junction Losses=0
Instantaneous Interval=1HOUR
Write IC File= 0
Write IC File at Sim End=0
Echo Input=False
Echo Parameters=False
Echo Output=False
Write Detailed= 0
WQ AD Non Conservative
WQ ULTIMATE=-1
WQ Max Comp Step=1HOUR
WQ Output Interval=15MIN
WQ Output Selected Increments= 0
WQ Output face flow=0
WQ Output face velocity=0
WQ Output face area=0
WQ Output face dispersion=0
WQ Output cell volume=0
WQ Output cell surface area=0
WQ Output cell continuity=0
WQ Output cumulative cell continuity=0
WQ Output face conc=0
WQ Output face dconc_dx=0
WQ Output face courant=0
WQ Output face peclet=0
WQ Output face adv mass=0
WQ Output face disp mass=0
WQ Output cell mass=0
WQ Output cell source sink temp=0
WQ Output cell source sink nsm=0
WQ Output MaxMinRange=-1
WQ Daily Max Min Mean=-1
WQ Daily Range=0
WQ Daily Time=0
WQ Create Restart=0
WQ Fixed Restart=0
WQ System Summary=0
WQ Use Fixed Temperature=0
Sorting and Armoring Iterations= 10
XS Update Threshold= 0.02
Hydraulics Update Threshold= 0.02
Energy Slope Method= 1
Volume Change Method= 0
XS Weighting Method= 0
Number of US Weighted Cross Sections= 1
Number of DS Weighted Cross Sections= 1
Upstream XS Weight=0.25
Main XS Weight=0.5
Downstream XS Weight=0.25
Number of DS XS's Weighted with US Boundary= 1
Upstream Boundary Weight= 1
Weight of XSs Associated with US Boundary= 0
Number of US XS's Weighted with DS Boundary= 1
Downstream Boundary Weight= 0.5
Weight of XSs Associated with DS Boundary= 0.5
Sediment Output Level= 4
Mass or Volume Output= 0
Output Increment Type= 1
Profile and TS Output Increment= 10
XS Output Flag= 0
XS Output Increment= 10
Disregard all LS=0
Disregard all Conn=0
Disregard all Breaches=0
Disregard all Pumps=0

--- U106-00-00.p01 (plan) ---

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Plan Title=Effective Multi-Profile 2019 (Re-Study)
Short Identifier=Eff+ReStudy MP
Geom File=g01
Flow File=f01
Encroach Param=-1 ,0,0, 0

--- U106-00-00.p03 (plan) ---

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Plan Title=Storage Routing (SV-SQ)
Short Identifier=SV-SQ
Geom File=g01
Flow File=f03
Encroach Param=-1 ,0,0, 0

--- U106-00-00.f02 (steady flow) ---

Flow Title=Effective Floodway 2019
Program Version=4.10
Number of Profiles= 2
Profile Names=100YR,FW
River Rch & RM=U106-00-00,U106-00-00_0006 ,34736.9
     277     277
River Rch & RM=U106-00-00,U106-00-00_0006 ,33978.27
     354     354
River Rch & RM=U106-00-00,U106-00-00_0006 ,33232.65
     445     445
River Rch & RM=U106-00-00,U106-00-00_0006 ,32538.94
     504     504
River Rch & RM=U106-00-00,U106-00-00_0006 ,32158.55
     550     550
River Rch & RM=U106-00-00,U106-00-00_0006 ,31892.18
     670     670
River Rch & RM=U106-00-00,U106-00-00_0006 ,31295.21
     762     762
River Rch & RM=U106-00-00,U106-00-00_0006 ,30906.18
     946     946
River Rch & RM=U106-00-00,U106-00-00_0006 ,30251.07
     950     950
River Rch & RM=U106-00-00,U106-00-00_0006 ,30237.72
     980     980
River Rch & RM=U106-00-00,U106-00-00_0006 ,30145.7
    1016    1016
River Rch & RM=U106-00-00,U106-00-00_0006 ,29925.7
    1186    1186
River Rch & RM=U106-00-00,U106-00-00_0006 ,28984.21
    1221    1221
River Rch & RM=U106-00-00,U106-00-00_0006 ,28808.57
    1264    1264
River Rch & RM=U106-00-00,U106-00-00_0006 ,28596.48
    1286    1286
River Rch & RM=U106-00-00,U106-00-00_0006 ,28491.74
    1369    1369
River Rch & RM=U106-00-00,U106-00-00_0006 ,28110.07
    1443    1443
River Rch & RM=U106-00-00,U106-00-00_0006 ,27792.54
    1553    1553
River Rch & RM=U106-00-00,U106-00-00_0006 ,27344.77
    1589    1589
River Rch & RM=U106-00-00,U106-00-00_0006 ,27203.95
    1634    1634
River Rch & RM=U106-00-00,U106-00-00_0006 ,27032.86
    1738    1738
River Rch & RM=U106-00-00,U106-00-00_0006 ,26660.09
    1898    1898
River Rch & RM=U106-00-00,U106-00-00_0006 ,26124.21
    2293    2293
River Rch & RM=U106-00-00,U106-00-00_0006 ,24973.88
    2415    2415
River Rch & RM=U106-00-00,U106-00-00_0006 ,24659.03
    2504    2504
River Rch & RM=U106-00-00,U106-00-00_0006 ,24439.49
    2693    2693
River Rch & RM=U106-00-00,U106-00-00_0006 ,23995.34
    2757    2757
River Rch & RM=U106-00-00,U106-00-00_0006 ,23852.47
    2879    2879
River Rch & RM=U106-00-00,U106-00-00_0006 ,23589.06
    2919    2919
River Rch & RM=U106-00-00,U106-00-00_0006 ,23506.34
    3250    3250
River Rch & RM=U106-00-00,U106-00-00_0006 ,22853.56
    3544    3544
River Rch & RM=U106-00-00,U106-00-00_0006 ,22164.43
    3664    3664
River Rch & RM=U106-00-00,U106-00-00_0006 ,21901.5
    3965    3965
River Rch & RM=U106-00-00,U106-00-00_0006 ,21273.96
    4111    4111
River Rch & RM=U106-00-00,U106-00-00_0006 ,20985.72
    4497    4497
River Rch & RM=U106-00-00,U106-00-00_0006 ,20274.23
    4712    4712
River Rch & RM=U106-00-00,U106-00-00_0006 ,19902.81
    4821    4821
River Rch & RM=U106-00-00,U106-00-00_0006 ,19722.39
    5033    5033
River Rch & RM=U106-00-00,U106-00-00_0006 ,19379.8
    5182    5182
River Rch & RM=U106-00-00,U106-00-00_0006 ,19149.03
    5982    5982
River Rch & RM=U106-00-00,U106-00-00_0006 ,18008.87
    6251    6251
River Rch & RM=U106-00-00,U106-00-00_0006 ,17659.51
    6558    6558
River Rch & RM=U106-00-00,U106-00-00_0006 ,15350.12
    6886    6886
River Rch & RM=U106-00-00,U106-00-00_0006 ,13005.42
    7179    7179
River Rch & RM=U106-00-00,U106-00-00_0006 ,11005.42
    7517    7517
River Rch & RM=U106-00-00,U106-00-00_0006 ,8794.251
    7888    7888
River Rch & RM=U106-00-00,U106-00-00_0006 ,6479.06
    8282    8282
River Rch & RM=U106-00-00,U106-00-00_0006 ,4135.911
    8679    8679
River Rch & RM=U106-00-00,U106-00-00_0006 ,1884.233
    8919    8919
Boundary for River Rch & Prof#=U106-00-00,U106-00-00_0006 , 1
Up Type= 0
Dn Type= 3
Dn Slope=0.0012
Boundary for River Rch & Prof#=U106-00-00,U106-00-00_0006 , 2
Up Type= 0
Dn Type= 3
Dn Slope=0.0012
Observed WS=U106-00-00      ,U106-00-00_0006 ,34736.9 ,0,131.76,133.72
Observed WS=U106-00-00      ,U106-00-00_0006 ,33978.27,0,131.76,133.72
Observed WS=U106-00-00      ,U106-00-00_0006 ,33232.65,0,131.76,133.72
Observed WS=U106-00-00      ,U106-00-00_0006 ,32538.94,0,131.76,133.72
Observed WS=U106-00-00      ,U106-00-00_0006 ,32158.55,0,131.76,133.72
Observed WS=U106-00-00      ,U106-00-00_0006 ,31892.18,0,131.76,133.72
Observed WS=U106-00-00      ,U106-00-00_0006 ,31295.21,0,131.76,133.71
Observed WS=U106-00-00      ,U106-00-00_0006 ,30906.18,0,131.75,133.71
Observed WS=U106-00-00      ,U106-00-00_0006 ,30251.07,0,131.67,133.61
Observed WS=U106-00-00      ,U106-00-00_0006 ,30237.72,0,131.67,133.61
Observed WS=U106-00-00      ,U106-00-00_0006 ,30163.92,0,131.38,132.92
Observed WS=U106-00-00      ,U106-00-00_0006 ,30145.7 ,0,131.36,132.9
Observed WS=U106-00-00      ,U106-00-00_0006 ,29925.7 ,0,131.11,132.61
Observed WS=U106-00-00      ,U106-00-00_0006 ,28984.21,0,130.02,131.46
Observed WS=U106-00-00      ,U106-00-00_0006 ,28885.46,0,129.91,131.34
Observed WS=U106-00-00      ,U106-00-00_0006 ,28808.57,0,129.74,131.17
Observed WS=U106-00-00      ,U106-00-00_0006 ,28676.88,0,129.44,130.89
Observed WS=U106-00-00      ,U106-00-00_0006 ,28596.48,0,129.25,130.71
Observed WS=U106-00-00      ,U106-00-00_0006 ,28491.74,0,129.02,130.48
Observed WS=U106-00-00      ,U106-00-00_0006 ,28110.07,0,128.15,129.65
Observed WS=U106-00-00      ,U106-00-00_0006 ,27792.54,0,127.65,129.23
Observed WS=U106-00-00      ,U106-00-00_0006 ,27664.41,0,126.99,128.42
Observed WS=U106-00-00      ,U106-00-00_0006 ,27344.77,0,126.98,128.41
Observed WS=U106-00-00      ,U106-00-00_0006 ,27238.83,0,126.82,128.27
Observed WS=U106-00-00      ,U106-00-00_0006 ,27203.95,0,126.77,128.23
Observed WS=U106-00-00      ,U106-00-00_0006 ,27108.55,0,126.47,127.95
Observed WS=U106-00-00      ,U106-00-00_0006 ,27032.86,0,126.4,127.89
Observed WS=U106-00-00      ,U106-00-00_0006 ,26660.09,0,126.08,127.62
Observed WS=U106-00-00      ,U106-00-00_0006 ,26124.21,0,125.57,127.2
Observed WS=U106-00-00      ,U106-00-00_0006 ,24973.88,0,124.75,126.65
Observed WS=U106-00-00      ,U106-00-00_0006 ,24659.03,0,124.7,126.61
Observed WS=U106-00-00      ,U106-00-00_0006 ,24544.18,0,124.68,126.59
Observed WS=U106-00-00      ,U106-00-00_0006 ,24439.49,0,124.67,126.58
Observed WS=U106-00-00      ,U106-00-00_0006 ,23995.34,0,124.6,126.52
Observed WS=U106-00-00      ,U106-00-00_0006 ,23852.47,0,124.39,126.29
Observed WS=U106-00-00      ,U106-00-00_0006 ,23788.41,0,124.3,126.19
Observed WS=U106-00-00      ,U106-00-00_0006 ,23712.13,0,124.18,126.07
Observed WS=U106-00-00      ,U106-00-00_0006 ,23589.06,0,124,125.88
Observed WS=U106-00-00      ,U106-00-00_0006 ,23506.34,0,123.88,125.74
Observed WS=U106-00-00      ,U106-00-00_0006 ,22853.56,0,122.92,124.71
Observed WS=U106-00-00      ,U106-00-00_0006 ,22164.43,0,121.63,123.62
Observed WS=U106-00-00      ,U106-00-00_0006 ,22005.4 ,0,120.97,123.03
Observed WS=U106-00-00      ,U106-00-00_0006 ,21941.71,0,120.39,122.6
Observed WS=U106-00-00      ,U106-00-00_0006 ,21939.22,0,120.38,122.59
Observed WS=U106-00-00      ,U106-00-00_0006 ,21928.05,0,120.35,122.57
Observed WS=U106-00-00      ,U106-00-00_0006 ,21901.5 ,0,120.26,122.5
Observed WS=U106-00-00      ,U106-00-00_0006 ,21273.96,0,118.3,120.97
Observed WS=U106-00-00      ,U106-00-00_0006 ,20985.72,0,118.07,120.81
Observed WS=U106-00-00      ,U106-00-00_0006 ,20274.23,0,117.61,120.46
Observed WS=U106-00-00      ,U106-00-00_0006 ,20114.5 ,0,117.44,120.3
Observed WS=U106-00-00      ,U106-00-00_0006 ,20066.32,0,117.31,120.18
Observed WS=U106-00-00      ,U106-00-00_0006 ,19978.63,0,117.23,120.11
Observed WS=U106-00-00      ,U106-00-00_0006 ,19902.81,0,117.16,120.05
Observed WS=U106-00-00      ,U106-00-00_0006 ,19722.39,0,117,119.9
Observed WS=U106-00-00      ,U106-00-00_0006 ,19379.8 ,0,116.7,119.63
Observed WS=U106-00-00      ,U106-00-00_0006 ,19149.03,0,116.49,119.45
Observed WS=U106-00-00      ,U106-00-00_0006 ,18008.87,0,115.79,118.85
Observed WS=U106-00-00      ,U106-00-00_0006 ,17829.24,0,115.59,118.65
Observed WS=U106-00-00      ,U106-00-00_0006 ,17815.82,0,115.57,118.63
Observed WS=U106-00-00      ,U106-00-00_0006 ,17675.65,0,115.28,118.36
Observed WS=U106-00-00      ,U106-00-00_0006 ,17659.51,0,115.27,118.35
Observed WS=U106-00-00      ,U106-00-00_0006 ,17099   ,0,114.82,117.96
Observed WS=U106-00-00      ,U106-00-00_0006 ,16293.39,0,114.28,117.49
Observed WS=U106-00-00      ,U106-00-00_0006 ,15604.09,0,113.35,116.86
Observed WS=U106-00-00      ,U106-00-00_0006 ,15471.62,0,113.29,116.81
Observed WS=U106-00-00      ,U106-00-00_0006 ,15434.33,0,113.27,116.8
Observed WS=U106-00-00      ,U106-00-00_0006 ,15350.12,0,113.23,116.77
Observed WS=U106-00-00      ,U106-00-00_0006 ,15320.28,0,113.05,116.51
Observed WS=U106-00-00      ,U106-00-00_0006 ,14811.87,0,112.59,116.08
Observed WS=U106-00-00      ,U106-00-00_0006 ,14194.91,0,112.08,115.63
Observed WS=U106-00-00      ,U106-00-00_0006 ,14061.19,0,111.97,115.54
Observed WS=U106-00-00      ,U106-00-00_0006 ,14003.57,0,111.72,114.86
Observed WS=U106-00-00      ,U106-00-00_0006 ,13646.79,0,111.51,114.67
Observed WS=U106-00-00      ,U106-00-00_0006 ,13005.42,0,111.15,114.35
Observed WS=U106-00-00      ,U106-00-00_0006 ,12230.04,0,110.6,113.88
Observed WS=U106-00-00      ,U106-00-00_0006 ,11675.06,0,109.81,113.11
Observed WS=U106-00-00      ,U106-00-00_0006 ,11568.75,0,109.72,113.02
Observed WS=U106-00-00      ,U106-00-00_0006 ,11515.39,0,109.45,112.53
Observed WS=U106-00-00      ,U106-00-00_0006 ,11005.42,0,109.33,112.44
Observed WS=U106-00-00      ,U106-00-00_0006 ,10050.94,0,108.89,111.94
Observed WS=U106-00-00      ,U106-00-00_0006 ,10025.62,0,108.87,111.91
Observed WS=U106-00-00      ,U106-00-00_0006 ,10009.41,0,108.86,111.9
Observed WS=U106-00-00      ,U106-00-00_0006 ,9878.908,0,108.67,111.64
Observed WS=U106-00-00      ,U106-00-00_0006 ,9856.587,0,108.69,111.7
Observed WS=U106-00-00      ,U106-00-00_0006 ,9832.995,0,108.66,111.66
Observed WS=U106-00-00      ,U106-00-00_0006 ,9619.335,0,108.29,111.22
Observed WS=U106-00-00      ,U106-00-00_0006 ,9578.745,0,108.26,111.19
Observed WS=U106-00-00      ,U106-00-00_0006 ,8794.251,0,107.71,110.61
Observed WS=U106-00-00      ,U106-00-00_0006 ,8163.752,0,107.11,109.92
Observed WS=U106-00-00      ,U106-00-00_0006 ,7905.084,0,106.98,109.78
Observed WS=U106-00-00      ,U106-00-00_0006 ,7388.485,0,106.73,109.49
Observed WS=U106-00-00      ,U106-00-00_0006 ,7093.843,0,106.51,109.18
Observed WS=U106-00-00      ,U106-00-00_0006 ,6479.06 ,0,106.15,108.82
Observed WS=U106-00-00      ,U106-00-00_0006 ,5787.579,0,105.64,108.34
Observed WS=U106-00-00      ,U106-00-00_0006 ,5054.988,0,105.02,107.69
Observed WS=U106-00-00      ,U106-00-00_0006 ,4135.911,0,104.34,107
Observed WS=U106-00-00      ,U106-00-00_0006 ,3194.384,0,103.71,106.33
Observed WS=U106-00-00      ,U106-00-00_0006 ,3027.574,0,103.58,106.19
Observed WS=U106-00-00      ,U106-00-00_0006 ,2904.468,0,103.35,105.83
Observed WS=U106-00-00      ,U106-00-00_0006 ,2393.094,0,102.88,105.32
Observed WS=U106-00-00      ,U106-00-00_0006 ,1884.233,0,102.55,104.97
Observed WS=U106-00-00      ,U106-00-00_0006 ,1354.328,0,102.02,104.38
Observed WS=U106-00-00      ,U106-00-00_0006 ,1154.309,0,101.79,104.12
Observed WS=U106-00-00      ,U106-00-00_0006 ,1145.811,0,101.78,104.11
Observed WS=U106-00-00      ,U106-00-00_0006 ,575.5177,0,101.15,103.46
DSS Import GetInterval= 0
DSS Import GetPeak= 0
DSS Import FillOption= 0

--- U106-00-00.f01 (steady flow) ---

Flow Title=Effective Multi-Profile 2019
Program Version=4.10
Number of Profiles= 4
Profile Names=10YR,50YR,100YR,500YR
River Rch & RM=U106-00-00,U106-00-00_0006 ,34736.9
     237     264     277     548
River Rch & RM=U106-00-00,U106-00-00_0006 ,33978.27
     277     329     354     661
River Rch & RM=U106-00-00,U106-00-00_0006 ,33232.65
     320     403     445     787
River Rch & RM=U106-00-00,U106-00-00_0006 ,32538.94
     347     451     504     866
River Rch & RM=U106-00-00,U106-00-00_0006 ,32158.55
     367     488     550     926
River Rch & RM=U106-00-00,U106-00-00_0006 ,31892.18
     416     583     670    1076
River Rch & RM=U106-00-00,U106-00-00_0006 ,31295.21
     451     653     762    1187
River Rch & RM=U106-00-00,U106-00-00_0006 ,30906.18
     518     793     946    1399
River Rch & RM=U106-00-00,U106-00-00_0006 ,30251.07
     520     796     950    1404
River Rch & RM=U106-00-00,U106-00-00_0006 ,30237.72
     530     818     980    1437
River Rch & RM=U106-00-00,U106-00-00_0006 ,30145.7
     548     848    1016    1490
River Rch & RM=U106-00-00,U106-00-00_0006 ,29925.7
     636     989    1186    1742
River Rch & RM=U106-00-00,U106-00-00_0006 ,28984.21
     653    1018    1221    1794
River Rch & RM=U106-00-00,U106-00-00_0006 ,28808.57
     675    1054    1264    1858
River Rch & RM=U106-00-00,U106-00-00_0006 ,28596.48
     687    1072    1286    1890
River Rch & RM=U106-00-00,U106-00-00_0006 ,28491.74
     729    1141    1369    2014
River Rch & RM=U106-00-00,U106-00-00_0006 ,28110.07
     766    1202    1443    2123
River Rch & RM=U106-00-00,U106-00-00_0006 ,27792.54
     822    1293    1553    2286
River Rch & RM=U106-00-00,U106-00-00_0006 ,27344.77
     840    1323    1589    2341
River Rch & RM=U106-00-00,U106-00-00_0006 ,27203.95
     863    1361    1634    2408
River Rch & RM=U106-00-00,U106-00-00_0006 ,27032.86
     915    1446    1738    2562
River Rch & RM=U106-00-00,U106-00-00_0006 ,26660.09
     996    1579    1898    2800
River Rch & RM=U106-00-00,U106-00-00_0006 ,26124.21
    1192    1906    2293    3388
River Rch & RM=U106-00-00,U106-00-00_0006 ,24973.88
    1253    2006    2415    3570
River Rch & RM=U106-00-00,U106-00-00_0006 ,24659.03
    1297    2080    2504    3702
River Rch & RM=U106-00-00,U106-00-00_0006 ,24439.49
    1390    2236    2693    3986
River Rch & RM=U106-00-00,U106-00-00_0006 ,23995.34
    1422    2289    2757    4081
River Rch & RM=U106-00-00,U106-00-00_0006 ,23852.47
    1482    2390    2879    4264
River Rch & RM=U106-00-00,U106-00-00_0006 ,23589.06
    1501    2422    2919    4322
River Rch & RM=U106-00-00,U106-00-00_0006 ,23506.34
    1663    2695    3250    4817
River Rch & RM=U106-00-00,U106-00-00_0006 ,22853.56
    1819    2940    3544    5250
River Rch & RM=U106-00-00,U106-00-00_0006 ,22164.43
    1882    3040    3664    5426
River Rch & RM=U106-00-00,U106-00-00_0006 ,21901.5
    2041    3290    3965    5869
River Rch & RM=U106-00-00,U106-00-00_0006 ,21273.96
    2119    3412    4111    6085
River Rch & RM=U106-00-00,U106-00-00_0006 ,20985.72
    2323    3733    4497    6651
River Rch & RM=U106-00-00,U106-00-00_0006 ,20274.23
    2438    3913    4712    6967
River Rch & RM=U106-00-00,U106-00-00_0006 ,19902.81
    2496    4003    4821    7126
River Rch & RM=U106-00-00,U106-00-00_0006 ,19722.39
    2609    4180    5033    7438
River Rch & RM=U106-00-00,U106-00-00_0006 ,19379.8
    2688    4303    5182    7656
River Rch & RM=U106-00-00,U106-00-00_0006 ,19149.03
    3117    4970    5982    8830
River Rch & RM=U106-00-00,U106-00-00_0006 ,18008.87
    3261    5194    6251    9224
River Rch & RM=U106-00-00,U106-00-00_0006 ,17659.51
    3417    5456    6558    9635
River Rch & RM=U106-00-00,U106-00-00_0006 ,15350.12
    3584    5737    6886   10072
River Rch & RM=U106-00-00,U106-00-00_0006 ,13005.42
    3732    5987    7179   10459
River Rch & RM=U106-00-00,U106-00-00_0006 ,11005.42
    3903    6276    7517   10906
River Rch & RM=U106-00-00,U106-00-00_0006 ,8794.251
    4090    6594    7888   11393
River Rch & RM=U106-00-00,U106-00-00_0006 ,6479.06
    4289    6932    8282   11909
River Rch & RM=U106-00-00,U106-00-00_0006 ,4135.911
    4490    7274    8679   12426
River Rch & RM=U106-00-00,U106-00-00_0006 ,1884.233
    4610    7480    8919   12737
Boundary for River Rch & Prof#=U106-00-00,U106-00-00_0006 , 1
Up Type= 0
Dn Type= 3
Dn Slope=0.0012
Boundary for River Rch & Prof#=U106-00-00,U106-00-00_0006 , 2
Up Type= 0
Dn Type= 3
Dn Slope=0.0012
Boundary for River Rch & Prof#=U106-00-00,U106-00-00_0006 , 3
Up Type= 0
Dn Type= 3
Dn Slope=0.0012
Boundary for River Rch & Prof#=U106-00-00,U106-00-00_0006 , 4
Up Type= 0
Dn Type= 3
Dn Slope=0.0012
Observed WS=U106-00-00      ,U106-00-00_0006 ,34736.9 ,0,131.76,133.72,134.77,135.73
Observed WS=U106-00-00      ,U106-00-00_0006 ,33978.27,0,131.76,133.72,134.77,135.73
Observed WS=U106-00-00      ,U106-00-00_0006 ,33232.65,0,131.76,133.72,134.77,135.73
Observed WS=U106-00-00      ,U106-00-00_0006 ,32538.94,0,131.76,133.72,134.77,135.73
Observed WS=U106-00-00      ,U106-00-00_0006 ,32158.55,0,131.76,133.72,134.77,135.73
Observed WS=U106-00-00      ,U106-00-00_0006 ,31892.18,0,131.76,133.72,134.77,135.73
Observed WS=U106-00-00      ,U106-00-00_0006 ,31295.21,0,131.76,133.71,134.77,135.72
Observed WS=U106-00-00      ,U106-00-00_0006 ,30906.18,0,131.75,133.71,134.77,135.72
Observed WS=U106-00-00      ,U106-00-00_0006 ,30251.07,0,131.67,133.61,134.66,135.7
Observed WS=U106-00-00      ,U106-00-00_0006 ,30237.72,0,131.67,133.61,134.66,135.7
Observed WS=U106-00-00      ,U106-00-00_0006 ,30163.92,0,131.38,132.92,133.62,135.16
Observed WS=U106-00-00      ,U106-00-00_0006 ,30145.7 ,0,131.36,132.9,133.59,135.14
Observed WS=U106-00-00      ,U106-00-00_0006 ,29925.7 ,0,131.11,132.61,133.29,134.86
Observed WS=U106-00-00      ,U106-00-00_0006 ,28984.21,0,130.02,131.46,132.12,133.67
Observed WS=U106-00-00      ,U106-00-00_0006 ,28885.46,0,129.91,131.34,132,133.55
Observed WS=U106-00-00      ,U106-00-00_0006 ,28808.57,0,129.74,131.17,131.84,133.38
Observed WS=U106-00-00      ,U106-00-00_0006 ,28676.88,0,129.44,130.89,131.57,133.08
Observed WS=U106-00-00      ,U106-00-00_0006 ,28596.48,0,129.25,130.71,131.4,132.91
Observed WS=U106-00-00      ,U106-00-00_0006 ,28491.74,0,129.02,130.48,131.18,132.67
Observed WS=U106-00-00      ,U106-00-00_0006 ,28110.07,0,128.15,129.65,130.39,131.82
Observed WS=U106-00-00      ,U106-00-00_0006 ,27792.54,0,127.65,129.23,130.02,131.44
Observed WS=U106-00-00      ,U106-00-00_0006 ,27664.41,0,126.99,128.42,129.12,130.96
Observed WS=U106-00-00      ,U106-00-00_0006 ,27344.77,0,126.98,128.41,129.11,130.95
Observed WS=U106-00-00      ,U106-00-00_0006 ,27238.83,0,126.82,128.27,128.99,130.84
Observed WS=U106-00-00      ,U106-00-00_0006 ,27203.95,0,126.77,128.23,128.95,130.81
Observed WS=U106-00-00      ,U106-00-00_0006 ,27108.55,0,126.47,127.95,128.68,130.58
Observed WS=U106-00-00      ,U106-00-00_0006 ,27032.86,0,126.4,127.89,128.63,130.54
Observed WS=U106-00-00      ,U106-00-00_0006 ,26660.09,0,126.08,127.62,128.37,130.33
Observed WS=U106-00-00      ,U106-00-00_0006 ,26124.21,0,125.57,127.2,127.99,130.01
Observed WS=U106-00-00      ,U106-00-00_0006 ,24973.88,0,124.75,126.65,127.5,129.61
Observed WS=U106-00-00      ,U106-00-00_0006 ,24659.03,0,124.7,126.61,127.46,129.58
Observed WS=U106-00-00      ,U106-00-00_0006 ,24544.18,0,124.68,126.59,127.44,129.57
Observed WS=U106-00-00      ,U106-00-00_0006 ,24439.49,0,124.67,126.58,127.43,129.56
Observed WS=U106-00-00      ,U106-00-00_0006 ,23995.34,0,124.6,126.52,127.37,129.51
Observed WS=U106-00-00      ,U106-00-00_0006 ,23852.47,0,124.39,126.29,127.14,129.27
Observed WS=U106-00-00      ,U106-00-00_0006 ,23788.41,0,124.3,126.19,127.04,129.16
Observed WS=U106-00-00      ,U106-00-00_0006 ,23712.13,0,124.18,126.07,126.91,129.03
Observed WS=U106-00-00      ,U106-00-00_0006 ,23589.06,0,124,125.88,126.72,128.82
Observed WS=U106-00-00      ,U106-00-00_0006 ,23506.34,0,123.88,125.74,126.58,128.68
Observed WS=U106-00-00      ,U106-00-00_0006 ,22853.56,0,122.92,124.71,125.53,127.57
Observed WS=U106-00-00      ,U106-00-00_0006 ,22164.43,0,121.63,123.62,124.59,126.79
Observed WS=U106-00-00      ,U106-00-00_0006 ,22005.4 ,0,120.97,123.03,124.07,126.3
Observed WS=U106-00-00      ,U106-00-00_0006 ,21941.71,0,120.39,122.6,123.71,126.11
Observed WS=U106-00-00      ,U106-00-00_0006 ,21939.22,0,120.38,122.59,123.7,126.1
Observed WS=U106-00-00      ,U106-00-00_0006 ,21928.05,0,120.35,122.57,123.68,126.08
Observed WS=U106-00-00      ,U106-00-00_0006 ,21901.5 ,0,120.26,122.5,123.62,126.02
Observed WS=U106-00-00      ,U106-00-00_0006 ,21273.96,0,118.3,120.97,122.27,124.65
Observed WS=U106-00-00      ,U106-00-00_0006 ,20985.72,0,118.07,120.81,122.14,124.46
Observed WS=U106-00-00      ,U106-00-00_0006 ,20274.23,0,117.61,120.46,121.84,124.18
Observed WS=U106-00-00      ,U106-00-00_0006 ,20114.5 ,0,117.44,120.3,121.7,124.07
Observed WS=U106-00-00      ,U106-00-00_0006 ,20066.32,0,117.31,120.18,121.39,123.99
Observed WS=U106-00-00      ,U106-00-00_0006 ,19978.63,0,117.23,120.11,121.32,123.91
Observed WS=U106-00-00      ,U106-00-00_0006 ,19902.81,0,117.16,120.05,121.26,123.84
Observed WS=U106-00-00      ,U106-00-00_0006 ,19722.39,0,117,119.9,121.12,123.68
Observed WS=U106-00-00      ,U106-00-00_0006 ,19379.8 ,0,116.7,119.63,120.85,123.37
Observed WS=U106-00-00      ,U106-00-00_0006 ,19149.03,0,116.49,119.45,120.68,123.18
Observed WS=U106-00-00      ,U106-00-00_0006 ,18008.87,0,115.79,118.85,120.12,122.69
Observed WS=U106-00-00      ,U106-00-00_0006 ,17829.24,0,115.59,118.65,119.91,122.55
Observed WS=U106-00-00      ,U106-00-00_0006 ,17815.82,0,115.57,118.63,119.89,122.54
Observed WS=U106-00-00      ,U106-00-00_0006 ,17675.65,0,115.28,118.36,119.62,121.82
Observed WS=U106-00-00      ,U106-00-00_0006 ,17659.51,0,115.27,118.35,119.61,121.81
Observed WS=U106-00-00      ,U106-00-00_0006 ,17099   ,0,114.82,117.96,119.24,121.31
Observed WS=U106-00-00      ,U106-00-00_0006 ,16293.39,0,114.28,117.49,118.78,120.72
Observed WS=U106-00-00      ,U106-00-00_0006 ,15604.09,0,113.35,116.86,118.21,120.19
Observed WS=U106-00-00      ,U106-00-00_0006 ,15471.62,0,113.29,116.81,118.17,120.14
Observed WS=U106-00-00      ,U106-00-00_0006 ,15434.33,0,113.27,116.8,118.16,120.13
Observed WS=U106-00-00      ,U106-00-00_0006 ,15350.12,0,113.23,116.77,118.14,120.1
Observed WS=U106-00-00      ,U106-00-00_0006 ,15320.28,0,113.05,116.51,117.72,119.86
Observed WS=U106-00-00      ,U106-00-00_0006 ,14811.87,0,112.59,116.08,117.31,119.57
Observed WS=U106-00-00      ,U106-00-00_0006 ,14194.91,0,112.08,115.63,116.89,119.03
Observed WS=U106-00-00      ,U106-00-00_0006 ,14061.19,0,111.97,115.54,116.83,119.03
Observed WS=U106-00-00      ,U106-00-00_0006 ,14003.57,0,111.72,114.86,116.26,119.03
Observed WS=U106-00-00      ,U106-00-00_0006 ,13646.79,0,111.51,114.67,116.09,118.88
Observed WS=U106-00-00      ,U106-00-00_0006 ,13005.42,0,111.15,114.35,115.81,118.74
Observed WS=U106-00-00      ,U106-00-00_0006 ,12230.04,0,110.6,113.88,115.38,118.38
Observed WS=U106-00-00      ,U106-00-00_0006 ,11675.06,0,109.81,113.11,114.66,117.64
Observed WS=U106-00-00      ,U106-00-00_0006 ,11568.75,0,109.72,113.02,114.58,117.6
Observed WS=U106-00-00      ,U106-00-00_0006 ,11515.39,0,109.45,112.53,113.77,116.65
Observed WS=U106-00-00      ,U106-00-00_0006 ,11005.42,0,109.33,112.44,113.7,116.57
Observed WS=U106-00-00      ,U106-00-00_0006 ,10050.94,0,108.89,111.94,113.19,115.95
Observed WS=U106-00-00      ,U106-00-00_0006 ,10025.62,0,108.87,111.91,113.16,115.91
Observed WS=U106-00-00      ,U106-00-00_0006 ,10009.41,0,108.86,111.9,113.15,115.88
Observed WS=U106-00-00      ,U106-00-00_0006 ,9878.908,0,108.67,111.64,112.88,115.55
Observed WS=U106-00-00      ,U106-00-00_0006 ,9856.587,0,108.69,111.7,112.95,115.69
Observed WS=U106-00-00      ,U106-00-00_0006 ,9832.995,0,108.66,111.66,112.9,115.63
Observed WS=U106-00-00      ,U106-00-00_0006 ,9619.335,0,108.29,111.22,112.42,115.14
Observed WS=U106-00-00      ,U106-00-00_0006 ,9578.745,0,108.26,111.19,112.39,115.11
Observed WS=U106-00-00      ,U106-00-00_0006 ,8794.251,0,107.71,110.61,111.8,114.57
Observed WS=U106-00-00      ,U106-00-00_0006 ,8163.752,0,107.11,109.92,111.08,113.95
Observed WS=U106-00-00      ,U106-00-00_0006 ,7905.084,0,106.98,109.78,110.93,113.75
Observed WS=U106-00-00      ,U106-00-00_0006 ,7388.485,0,106.73,109.49,110.63,113.35
Observed WS=U106-00-00      ,U106-00-00_0006 ,7093.843,0,106.51,109.18,110.29,112.89
Observed WS=U106-00-00      ,U106-00-00_0006 ,6479.06 ,0,106.15,108.82,109.95,112.66
Observed WS=U106-00-00      ,U106-00-00_0006 ,5787.579,0,105.64,108.34,109.52,112.36
Observed WS=U106-00-00      ,U106-00-00_0006 ,5054.988,0,105.02,107.69,108.87,111.72
Observed WS=U106-00-00      ,U106-00-00_0006 ,4135.911,0,104.34,107,108.23,111.45
Observed WS=U106-00-00      ,U106-00-00_0006 ,3194.384,0,103.71,106.33,107.6,110.76
Observed WS=U106-00-00      ,U106-00-00_0006 ,3027.574,0,103.58,106.19,107.46,110.61
Observed WS=U106-00-00      ,U106-00-00_0006 ,2904.468,0,103.35,105.83,106.82,109.13
Observed WS=U106-00-00      ,U106-00-00_0006 ,2393.094,0,102.88,105.32,106.33,108.82
Observed WS=U106-00-00      ,U106-00-00_0006 ,1884.233,0,102.55,104.97,105.98,108.36
Observed WS=U106-00-00      ,U106-00-00_0006 ,1354.328,0,102.02,104.38,105.37,107.71
Observed WS=U106-00-00      ,U106-00-00_0006 ,1154.309,0,101.79,104.12,105.1,107.39
Observed WS=U106-00-00      ,U106-00-00_0006 ,1145.811,0,101.78,104.11,105.09,107.38
Observed WS=U106-00-00      ,U106-00-00_0006 ,575.5177,0,101.15,103.46,104.45,106.73
DSS Import GetInterval= 0
DSS Import GetPeak= 0
DSS Import FillOption= 0

--- U106-00-00.f03 (steady flow) ---

Flow Title=Storage Routing Flows
Program Version=4.10
Number of Profiles= 8
Profile Names=0.2,0.4,0.6,0.8,1,1.2,1.5,2
River Rch & RM=U106-00-00,U106-00-00_0006 ,34736.9
     196     392     588     784     980    1176    1470    1960
River Rch & RM=U106-00-00,U106-00-00_0006 ,30145.7
     650    1300    1951    2601    3251    3901    4877    6502
River Rch & RM=U106-00-00,U106-00-00_0006 ,22853.56
    1252    2503    3755    5006    6258    7510    9387   12516
River Rch & RM=U106-00-00,U106-00-00_0006 ,17659.51
    1788    3575    5363    7150    8938   10726   13407   17876
Boundary for River Rch & Prof#=U106-00-00,U106-00-00_0006 , 1
Up Type= 0
Dn Type= 3
Dn Slope=0.0004
Boundary for River Rch & Prof#=U106-00-00,U106-00-00_0006 , 2
Up Type= 0
Dn Type= 3
Dn Slope=0.0004
Boundary for River Rch & Prof#=U106-00-00,U106-00-00_0006 , 3
Up Type= 0
Dn Type= 3
Dn Slope=0.0004
Boundary for River Rch & Prof#=U106-00-00,U106-00-00_0006 , 4
Up Type= 0
Dn Type= 3
Dn Slope=0.0004
Boundary for River Rch & Prof#=U106-00-00,U106-00-00_0006 , 5
Up Type= 0
Dn Type= 3
Dn Slope=0.0004
Boundary for River Rch & Prof#=U106-00-00,U106-00-00_0006 , 6
Up Type= 0
Dn Type= 3
Dn Slope=0.0004
Boundary for River Rch & Prof#=U106-00-00,U106-00-00_0006 , 7
Up Type= 0
Dn Type= 3
Dn Slope=0.0004
Boundary for River Rch & Prof#=U106-00-00,U106-00-00_0006 , 8
Up Type= 0
Dn Type= 3
Dn Slope=0.0004
DSS Import GetInterval= 0
DSS Import GetPeak= 0
DSS Import FillOption= 0

--- U106-00-00.g01 (geometry) ---

Geom Title=U106-00-00 2019 (Re-Study)
Program Version=4.10

River Reach=U106-00-00      ,U106-00-00_0006
Reach XY= 30
3014562.0350331113894485.78829783021264.4284524513894771.0475698
 3022894.231295213893715.32428753023492.0808212813893029.4368798
3025715.1574118613891376.14294233028411.4965073613889920.4827958
 3030721.290444213889316.99975093031572.5508807713888152.0214378
3032735.9993412813887497.0020785 3033612.711498613885575.2510008
3034667.7500709413884307.99992643035093.2075533613884012.2715152
3035728.6180279413884145.0707903 3035987.665738213883743.6959369
3036418.8157945313883654.96481513036670.1217223613883384.0070237
3037362.3214534413883529.17766513037732.0749790213883102.2100151
3037882.4080116913882340.85523863037630.2513637813881777.0017075
3037851.0022346113880827.0019671 3038162.911059613880445.2333737
3037642.9324407713879814.08601393038424.5627672813879037.1190639
3038075.7573625313877665.86360443038264.5427461113877203.1447135
3038306.8221891113876244.8018139 3038777.500381613875437.0009361
3039475.3470830313874760.16501943039230.1303818713874333.1173171

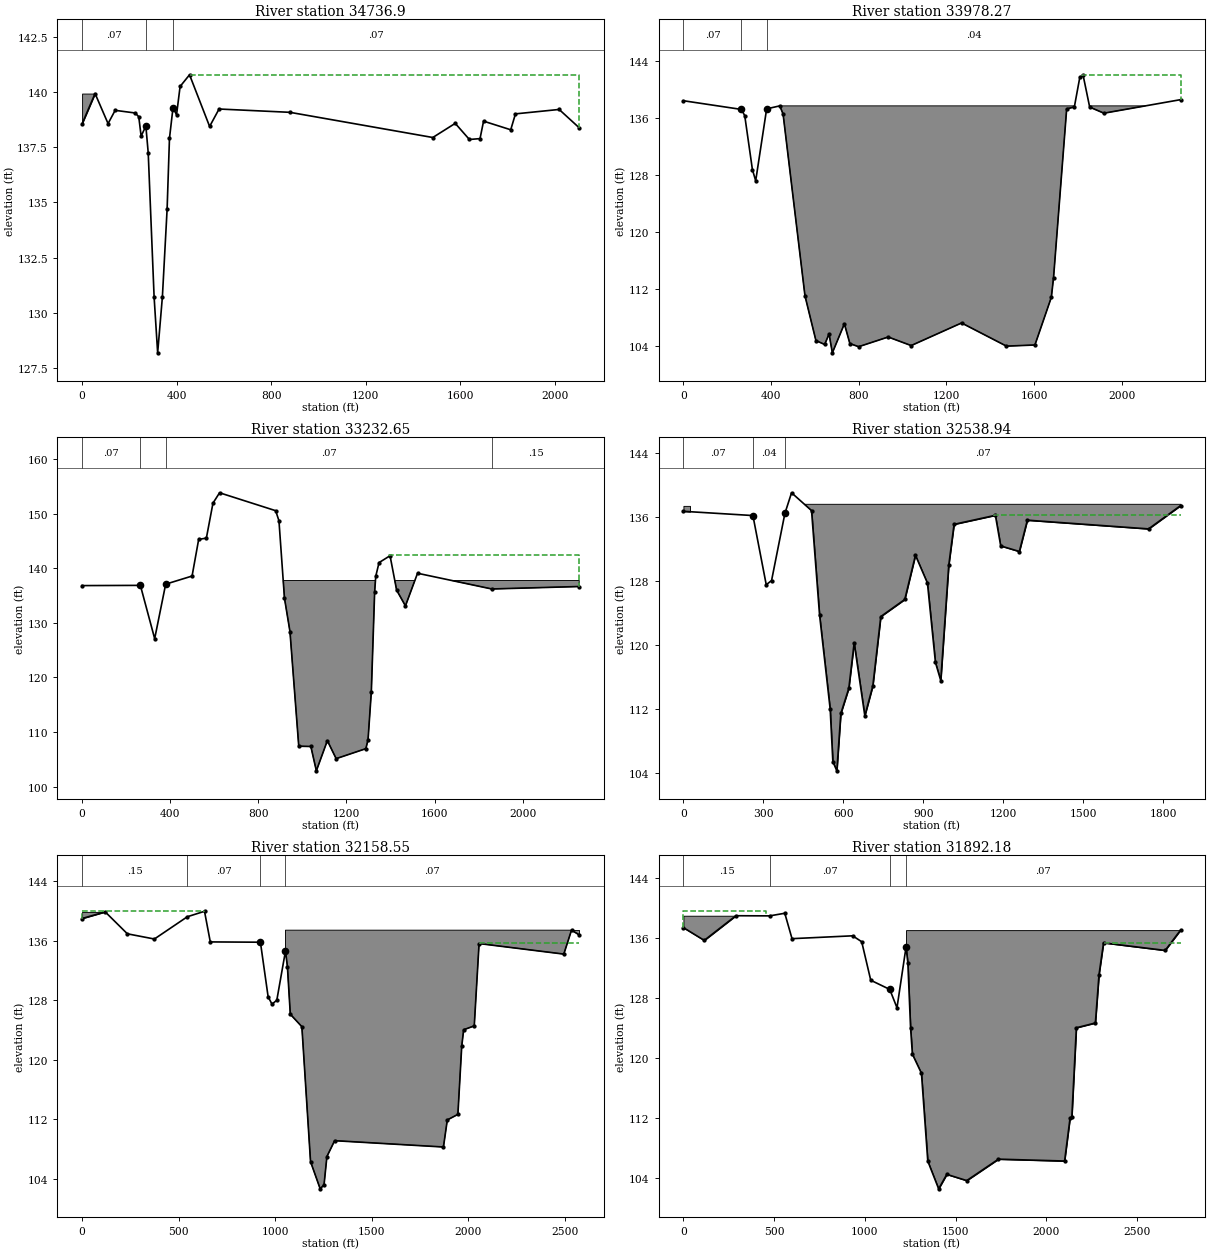
Type RM Length L Ch R = 1 ,34736.9 ,756.79,758.63,760.54
Node Name=AI
XS GIS Cut Line= 2
3018543.9998381913894988.99988983018599.2146227813892885.9844108
#Sta/Elev= 30
       0  138.56   54.97  139.93  109.93  138.57  139.92  139.17  224.87  139.05
  239.86  138.88  249.85     138  269.84  138.46  279.83  137.25  304.82  130.71
  319.81  128.19   339.8  130.72  359.78  134.69  369.78   137.9  384.77  139.29
  399.76  138.97  414.75  140.25  454.73  140.78  539.68  138.44  579.65  139.23
  879.47  139.08 1484.11  137.94 1579.05  138.58 1639.02  137.85 1683.99  137.89
 1698.98  138.68 1813.91  138.29  1833.9  139.01 2018.79  139.21 2103.74  138.38
#Mann= 3 ,-1 , 0
       0     .07       0  269.84     .04       0  384.77     .07       0
#XS Ineff= 2 , 0
       0                  454.73       0  140.78
Permanent Ineff=
       F       F
#Block Obstruct= 2 , 0
       0   54.97  139.93   499.7       0  139.33
Bank Sta=269.84,384.77
XS Rating Curve= 0 ,0
Exp/Cntr=0.3,0.1

Type RM Length L Ch R = 1 ,33978.27,745.29,745.62,746.21
XS GIS Cut Line= 2
 3019289.999986613895025.0001459 3019429.263815713892760.4308561
#Sta/Elev= 30
       0  138.45  264.87  137.23  279.86  136.35  314.84  128.79  329.83  127.22
  379.81  137.31  439.78  137.73  454.77  136.59  554.72  111.09  604.69  104.81
  644.67  104.26  664.66  105.74  679.65  103.09  734.63  107.16  759.61  104.39
  799.59  103.95  934.53  105.31 1039.47  104.11 1269.35  107.28 1474.25  104.03
 1604.18  104.19 1679.15  110.88 1689.14  113.62 1749.11  137.31 1784.09  137.57
 1809.08  141.74 1824.07  142.03 1854.06  137.56 1919.02   136.7 2268.85   138.6
#Mann= 3 ,-1 , 0
       0     .07       0  264.87     .04       0  379.81     .04       0
#XS Ineff= 2 , 0
       0                 1819.07       0  142.09
Permanent Ineff=
       F       F
#Block Obstruct= 1 ,-1
  439.78 2268.85  137.73
Bank Sta=264.87,379.81
XS Rating Curve= 0 ,0
Exp/Cntr=0.3,0.1

Type RM Length L Ch R = 1 ,33232.65,693.97,693.71,693.38
XS GIS Cut Line= 2
3020032.0001430213895060.00007583020189.56085153 13892809.257202
#Sta/Elev= 30
       0  136.81  264.56  136.85  329.45  127.09  379.37  137.07  499.17  138.56
  529.12  145.27  564.06  145.51  594.01  151.91  623.96  153.81  878.54  150.53
  893.52  148.68  918.47  134.52  943.43   128.4  983.37  107.39 1038.27  107.34
 1063.23  102.88 1113.15  108.41 1153.08  105.11 1287.86  106.94 1297.84  108.57
 1312.82  117.39 1327.79  135.63 1332.78  138.51 1347.76  141.02 1397.68  142.28
 1427.63  135.97 1467.56  133.09 1522.47  139.07 1859.52  136.19 2256.25  136.64
#Mann= 4 ,-1 , 0
       0     .07       0  264.56     .04       0  379.37     .07       0
 1859.52     .15       0
#XS Ineff= 2 , 0
       0                 1392.69       0  142.45
Permanent Ineff=
       F       F
#Block Obstruct= 1 ,-1
  504.16 2256.25  137.75
Bank Sta=264.56,379.37
XS Rating Curve= 0 ,0
Exp/Cntr=0.3,0.1

Type RM Length L Ch R = 1 ,32538.94,406.07,380.39,355.87
XS GIS Cut Line= 3
3020723.0000733613895082.00003193020742.0000353613894857.0001538
3020847.8131439413893220.5913531
#Sta/Elev= 30
       0  136.74   260.8  136.21  310.79  127.55  330.79  128.08  380.81  136.48
  405.78  139.06  480.77  136.83  510.77   123.8  550.77  111.98  560.76  105.41
  575.76  104.26  590.76  111.44  620.76   114.6  640.76  120.28  680.75  111.15
  710.75  114.88  740.75  123.57  830.74  125.71  870.73  131.24  915.73  127.76
  945.72  117.83  965.72  115.56  995.72  129.98 1015.72  135.11  1170.7  136.24
  1190.7  132.41 1260.69  131.71 1290.69  135.63 1745.64  134.54 1865.63  137.45
#Mann= 3 ,-1 , 0
       0     .07       0   260.8     .04       0  380.81     .07       0
#XS Ineff= 2 , 0
       0                  1165.7       0  136.26
Permanent Ineff=
       F       F
#Block Obstruct= 2 ,-1
       0   24.54  137.42  405.78 1865.63  137.68
Bank Sta=260.8,380.81
XS Rating Curve= 0 ,0
Exp/Cntr=0.3,0.1

Type RM Length L Ch R = 1 ,32158.55,298.48,266.36,236.53
Node Name=Start U106-14-00
XS GIS Cut Line= 3
3021404.0000236913895731.0000462 3021023.7192882 13894437.372056
3020861.36823495 13893221.035906
#Sta/Elev= 30
       0  139.01  119.85   139.9  234.72  136.95  374.55  136.25  545.42  139.25
  634.23  139.98  664.19  135.86  923.88  135.82  963.83  128.47  983.81  127.49
 1008.78  128.01 1053.72  134.64 1063.71  132.55 1078.69  126.13 1138.62  124.45
 1183.56  106.29  1233.5  102.63 1253.48  103.17 1268.46  106.98 1308.41  109.11
 1872.14  108.26 1892.09   111.9 1946.96  112.65 1966.91  121.84 1976.89  124.04
 2031.76  124.56  2056.7  135.64 2495.67  134.22 2535.58  137.44 2575.49  136.81
#Mann= 4 ,-1 , 0
       0     .15       0  545.42     .07       0  923.88     .04       0
 1053.72     .07       0
#XS Ineff= 2 , 0
       0  629.24  140.05 2061.69       0  135.75
Permanent Ineff=
       F       F
#Block Obstruct= 2 ,-1
       0  119.85   139.9 1053.72 2575.49  137.44
Bank Sta=923.88,1053.72
XS Rating Curve= 0 ,0
Exp/Cntr=0.3,0.1

Type RM Length L Ch R = 1 ,31892.18,672.46,596.97,598.99
XS GIS Cut Line= 3
3022211.0000501113895545.00009013021339.0001536913894681.9998476
3020936.86841203 13893223.512279
#Sta/Elev= 30
       0  137.38  114.71  135.68  289.26  138.97  475.53  138.95  558.56   139.3
  598.46  135.91   932.6  136.29  982.48   135.5 1032.35  130.36 1137.08  129.14
 1176.98  126.69 1226.85  134.79 1236.84  132.69 1251.81  124.01  1261.8   120.5
 1311.73  117.95 1346.68  106.23  1406.6  102.53 1451.54  104.46 1561.39  103.63
 1736.15  106.49 2100.65  106.24 2130.61  111.92 2140.59   112.1 2165.56  124.02
 2270.41  124.66 2290.38   131.1 2315.35  135.35 2654.88  134.34 2739.76  137.05
#Mann= 4 ,-1 , 0
       0     .15       0  475.53     .07       0 1137.08     .04       0
 1226.85     .07       0
#XS Ineff= 2 ,-1
       0  453.83  139.63 2320.34 2739.76  135.36
Permanent Ineff=
       F       F
#Block Obstruct= 2 ,-1
       0  289.26  138.97 1226.85 2739.76  137.05
Bank Sta=1137.08,1226.85
XS Rating Curve= 0 ,0
Exp/Cntr=0.3,0.1