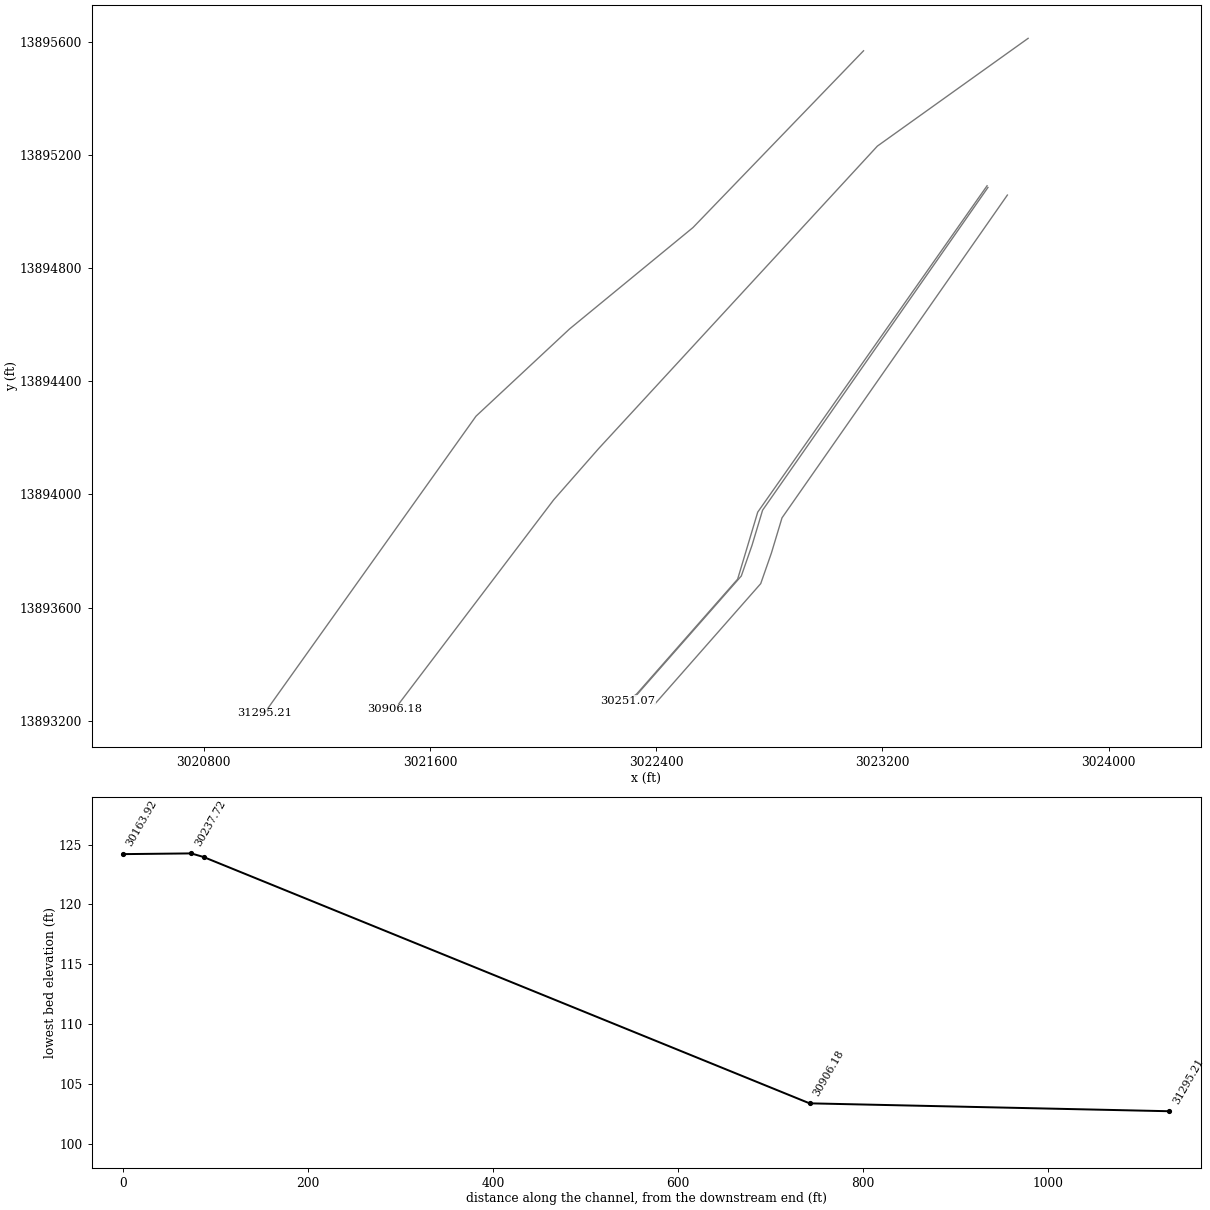
HEC-RAS study U106-00-00.prj: U106-00-00 2019 (Re-Study)

--- U106-00-00.g01 (geometry) --- (continued)

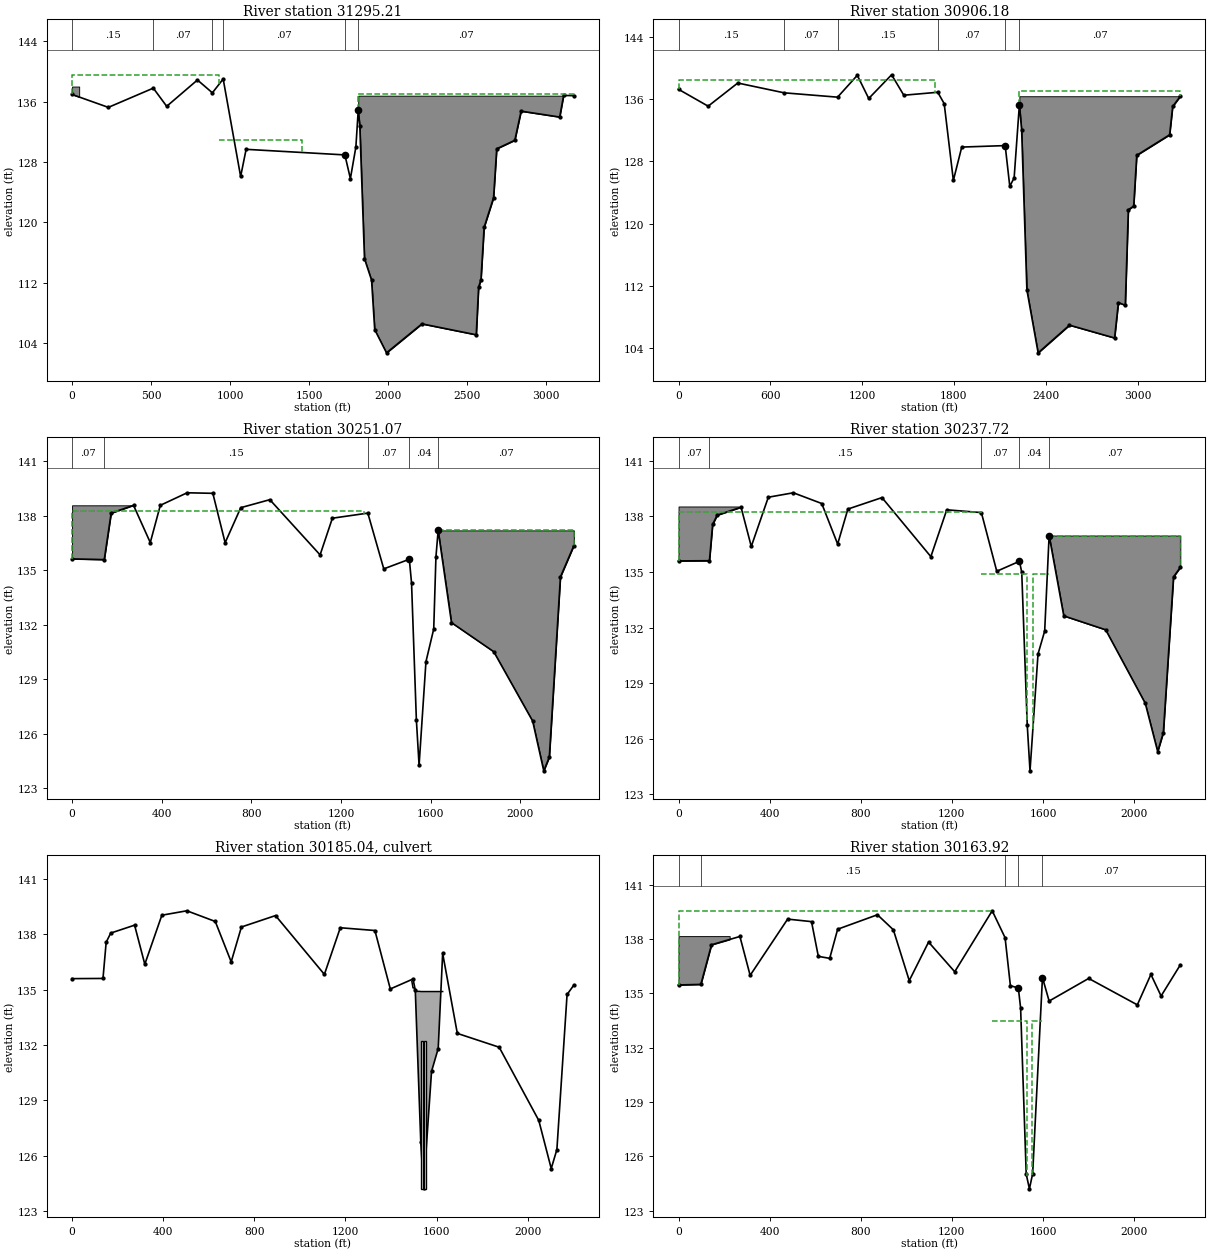
Type RM Length L Ch R = 1 ,31295.21,389.45,389.04,394.48
XS GIS Cut Line= 5
3023132.9998465313895569.00004213022530.0000682813894943.9999798
3022092.9999580213894585.00004163021762.7342143713894277.0006576
 3021013.982759113893226.0418015
#Sta/Elev= 30
       0  136.96  229.59  135.25  514.19   137.8  598.94  135.39   793.6  138.88
  888.02  137.18  956.47  139.01 1066.91  126.09 1101.63  129.69 1726.81  128.95
 1761.55  125.81 1796.29  129.99 1811.18  134.84  1821.1  132.84 1850.88  115.19
 1895.58  112.36 1915.51   105.8 1990.24  102.72 2214.45  106.56 2558.23  105.11
 2573.18  111.42 2588.12  112.41 2608.05  119.35 2667.84  123.28 2687.77  129.76
 2802.36  130.89 2842.22  134.75 3086.36  133.97 3111.27  136.83 3176.04   136.8
#Mann= 6 ,-1 , 0
       0     .15       0  514.19     .07       0  888.02     .15       0
  956.47     .07       0 1726.81     .04       0 1811.18     .07       0
#XS Ineff= 3 ,-1
       0  932.96  139.57  932.96 1453.87  130.94 1811.18 3176.04     137
Permanent Ineff=
       F       F       F
#Block Obstruct= 2 ,-1
       0   44.92  138.01 1811.18 3176.04   136.8
Bank Sta=1726.81,1811.18
XS Rating Curve= 0 ,0
Exp/Cntr=0.3,0.1

Type RM Length L Ch R = 1 ,30906.18,647.38,655.11,682.42
XS GIS Cut Line= 5
3023714.9999948613895612.99995413023182.0000766113895232.0000599
3022196.0000801113894161.99990343022037.5820898613893981.4484272
3021475.6498147713893241.1848159
#Sta/Elev= 30
       0  137.28  193.57  135.11  387.15  138.09   689.9  136.83 1039.46  136.27
 1168.42  139.08 1243.16   136.1 1392.65  139.15 1472.38  136.52 1694.46   136.9
 1736.48  135.43 1796.27  125.56 1851.09  129.85 2135.01  130.04    2165  124.81
 2193.53  125.88 2227.85  135.31 2242.56  132.01 2276.87  111.47  2350.4  103.38
 2555.26  106.94 2850.06  105.29 2875.05  109.85 2920.02  109.49    2940  121.78
 2974.98  122.26 2994.96  128.79 3209.82  131.43 3229.81  135.07 3279.77  136.39
#Mann= 6 ,-1 , 0
       0     .15       0   689.9     .07       0 1039.46     .15       0
 1694.46     .07       0 2135.01     .04       0 2227.85     .07       0
#XS Ineff= 3 ,-1
       0 1676.68  138.54 1676.68 1851.09  129.85 2227.85 3279.77     137
Permanent Ineff=
       F       F       F
#Block Obstruct= 1 ,-1
 2227.85 3279.77  136.39
Bank Sta=2135.01,2227.85
XS Rating Curve= 0 ,0
Exp/Cntr=0.3,0.1

Type RM Length L Ch R = 1 ,30251.07,14.37,13.35,9.65
XS GIS Cut Line= 5
3023569.81754245 13895091.6227163022758.8175240313893937.6227274
3022687.8176660213893700.62254533022330.8177238613893294.6227011
3022298.8174597813893270.6227491
#Sta/Elev= 30
       0  135.63  143.55  135.59  174.44  138.15  274.12  138.58  348.88  136.53
  393.74  138.58  513.35  139.27  627.99  139.24  682.81  136.52  752.59  138.45
  882.17  138.89 1106.45  135.85 1161.27  137.87  1319.4  138.15 1390.54  135.08
 1504.49  135.61 1514.38  134.31 1535.95  126.77 1548.03  124.27 1578.71  129.97
 1613.35  131.77 1623.24  135.74 1633.14   137.2  1692.6  132.12 1881.08  130.52
 2054.68   126.7 2104.28  123.96 2129.08  124.72 2178.68  134.64 2238.52  136.36
#Mann= 5 ,-1 , 0
       0     .07       0  143.55     .15       0  1319.4     .07       0
 1504.49     .04       0 1633.14     .07       0
#XS Ineff= 2 ,-1
       0 1300.83  138.24 1633.14 2238.52   137.2
Permanent Ineff=
       F       F
#Block Obstruct= 2 ,-1
       0  274.12  138.58 1633.14 2238.52   137.2
Bank Sta=1504.49,1633.14
XS Rating Curve= 0 ,0
Exp/Cntr=0.5,0.3

Type RM Length L Ch R = 1 ,30237.72,73.59,73.8,89.98
BEGIN DESCRIPTION:
Upstream Section (DETENTION OUTLET)
END DESCRIPTION:
Node Name=AH
XS GIS Cut Line= 6
3023572.9333498613895085.82449933022776.0238544513893944.4629368
3022738.6692703713893820.39855243022730.90944336 13893798.176484
3022700.7615377813893711.84299533022326.8236373713893286.6627433
#Sta/Elev= 30
       0   135.6  135.74  135.61  149.68  137.57  169.64  138.07  274.42   138.5
  319.32  136.38  394.16  139.04  503.93  139.28  628.66   138.7  698.51  136.51
  743.42   138.4   893.1  139.02 1107.65  135.83  1177.5  138.36 1329.43  138.21
 1397.03  135.04 1496.69  135.58 1506.66  134.98 1530.83  126.73 1542.91  124.26
 1578.09  130.57 1607.34  131.81 1626.84  136.97 1691.23  132.63    1875  131.88
 2048.85  127.91 2103.48   125.3 2128.31  126.33 2173.02  134.74 2202.82  135.25
#Mann= 5 ,-1 , 0
       0     .07       0  135.74     .15       0 1329.43     .07       0
 1496.69     .04       0 1626.84     .07       0
#XS Ineff= 4 ,-1
       0 1327.18  138.22 1327.18 1530.41  134.91 1555.41 1626.84   134.9
 1626.84 2202.82  136.97
Permanent Ineff=
       F       F       F       F
#Block Obstruct= 2 ,-1
       0  264.44  138.54 1626.84 2202.82  136.97
Bank Sta=1496.69,1626.84
XS Rating Curve= 0 ,0
Exp/Cntr=0.5,0.3

Type RM Length L Ch R = 2 ,30185.04,,,
BEGIN DESCRIPTION:
DETENTION OUTLET
END DESCRIPTION:
Node Name=DETENTION OUTLET
Bridge Culvert--1,0,-1,-1, 0
Deck Dist Width WeirC Skew NumUp NumDn MinLoCord MaxHiCord MaxSubmerge Is_Ogee
35.5,25,2.6,0, 29, 26, , , 0.98, 0, 0,0,,
 1491.71 1496.69 1501.68 1506.66 1511.64 1516.63 1521.61 1526.32 1531.02 1535.73
 1540.44 1545.15 1549.85 1554.56 1559.27 1563.97 1568.68 1573.38 1578.09 1582.96
 1587.84 1592.72 1597.59 1602.47 1607.34 1612.22 1617.09 1621.97 1626.84
  135.45   135.1   135.1  134.91  134.91  134.91  134.91  134.91   134.9   134.9
   134.9   134.9   134.9   134.9   134.9   134.9   134.9   134.9   134.9   134.9
   134.9   134.9   134.9   134.9   134.9   134.9   134.9   134.9   134.9
                                                                                
                                                                                
                                                                        
 1491.71 1496.69 1501.68 1506.66 1511.64 1516.63 1521.61 1526.32 1531.02 1535.73
 1540.44 1545.15 1549.85 1554.56 1559.27 1563.97 1568.68 1573.38 1578.09 1582.96
 1587.84 1592.72 1597.59 1602.47 1607.34 1612.22
   135.3   135.1   134.9   134.9   134.9   134.9   134.9   134.9   134.9   134.9
   134.9   134.9   134.9   134.9   134.9   134.9   134.9   134.9   134.9   134.9
   134.9   134.9   134.9   134.9   134.9   134.9
                                                                                
                                                                                
                                                
BR Coef=-1 , 0 , 0 ,, 0 ,,,0.8,-1,,0,
WSPro=,,,, 1 ,,,, 0 ,,,, 0 ,,,,-1 ,-1 ,-1 , 0 , 0 , 0 , 0 , 0
Culvert=2,8,12,25,0.015,0.5,1,8,1,124.2,1536.41,124.1,1533.86,Culvert #1  , 0 ,35.5
Culvert Bottom n=0.015
Culvert=2,8,12,25,0.015,0.5,1,8,1,124.2,1549.41,124.1,1546.86,Culvert #2  , 0 ,35.5
Culvert Bottom n=0.015
BC Design=,, 0 ,, 0 ,,,,,,
BC Use User HTab Curves=0
BC User HTab FreeFlow(D)= 0

Type RM Length L Ch R = 1 ,30163.92,16.15,18.22,21.09
BEGIN DESCRIPTION:
Downstream Section (DETENTION OUTLET)
END DESCRIPTION:
Node Name=AG
XS GIS Cut Line= 6
3023641.60611278 13895058.7920733022844.6966173613893917.4305106
3022807.3420332813893793.36612623022799.5822062813893771.1440578
3022769.43430069 13893684.8105693022395.49640028 13893259.630317
#Sta/Elev= 30
       0  135.47   97.95   135.5  144.69  137.69  269.43  138.15  314.33     136
  478.98  139.11  583.76  138.97  613.69  137.05  663.59  136.94  698.51  138.55
  873.14  139.35     943  138.52 1012.85  135.71 1097.67  137.84 1212.42   136.2
 1377.07  139.57 1433.55  138.08 1456.83  135.43 1491.71   135.3 1501.68   134.2
 1526.32  125.01 1540.36   124.2 1554.56  125.04 1597.59  135.88 1626.84  134.58
  1800.5  135.83 2014.08  134.37 2073.68  136.05 2118.38  134.86 2202.82  136.58
#Mann= 5 ,-1 , 0
       0     .07       0   97.95     .15       0 1433.55     .07       0
 1491.71     .04       0 1597.59     .07       0
#XS Ineff= 4 ,-1
       0 1377.07  139.57 1377.07 1527.86   133.5 1552.86 1597.59   133.5
 1597.59 2202.82  135.88
Permanent Ineff=
       F       F       F       F
#Block Obstruct= 2 , 0
       0  224.52  138.17               0
Bank Sta=1491.71,1597.59
XS Rating Curve= 0 ,0
Exp/Cntr=0.5,0.3