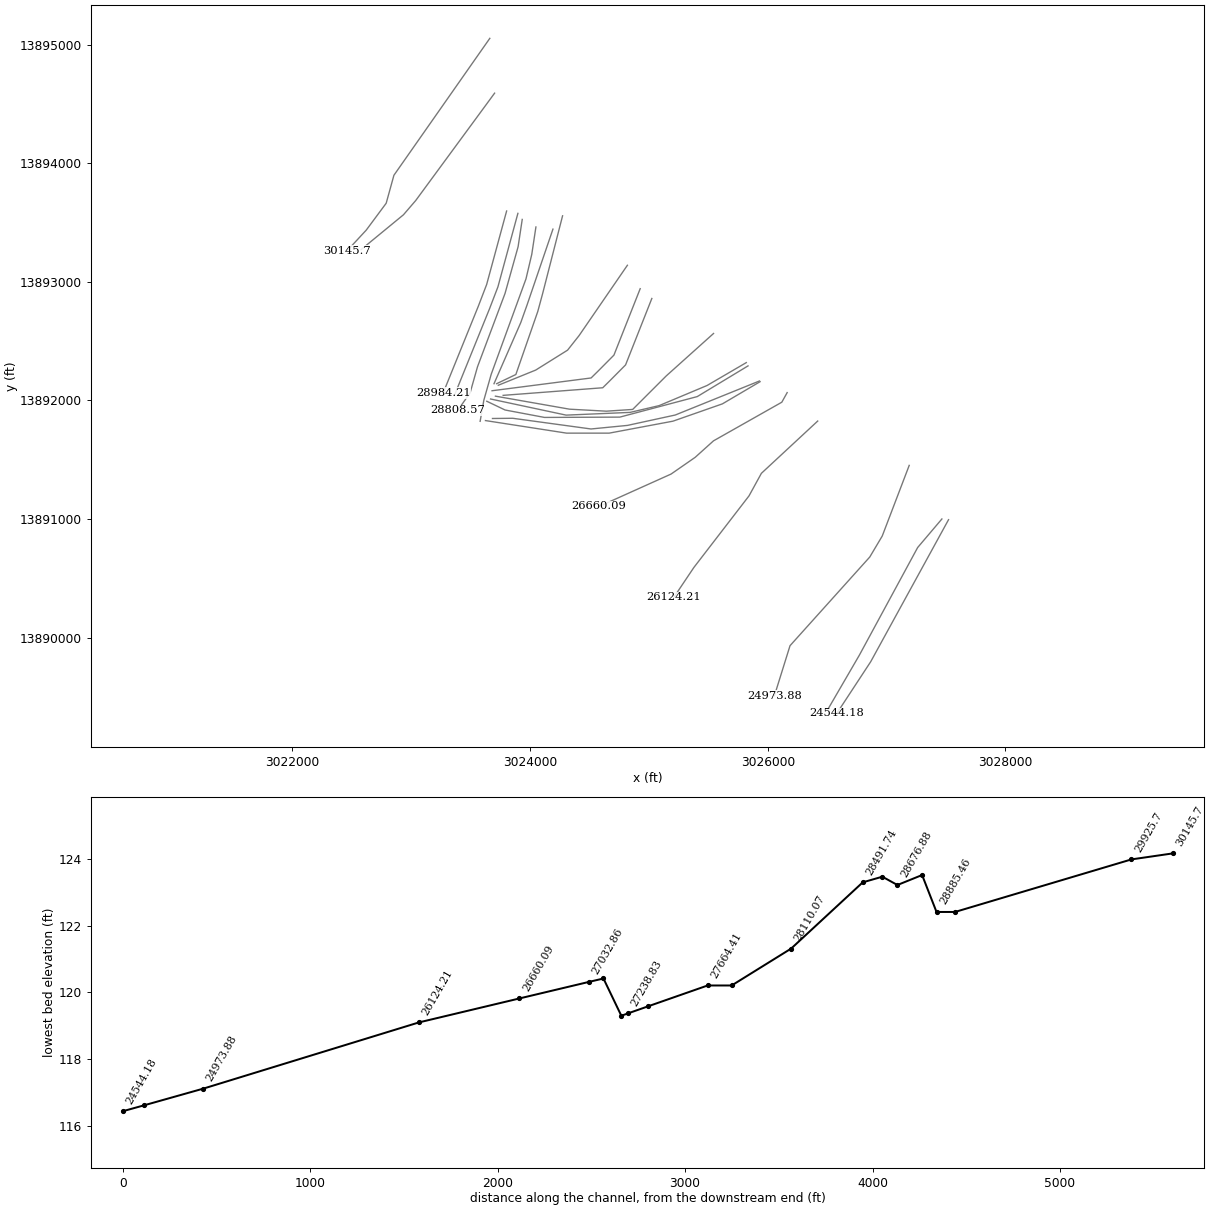
HEC-RAS study U106-00-00.prj: U106-00-00 2019 (Re-Study)

--- U106-00-00.g01 (geometry) --- (continued)

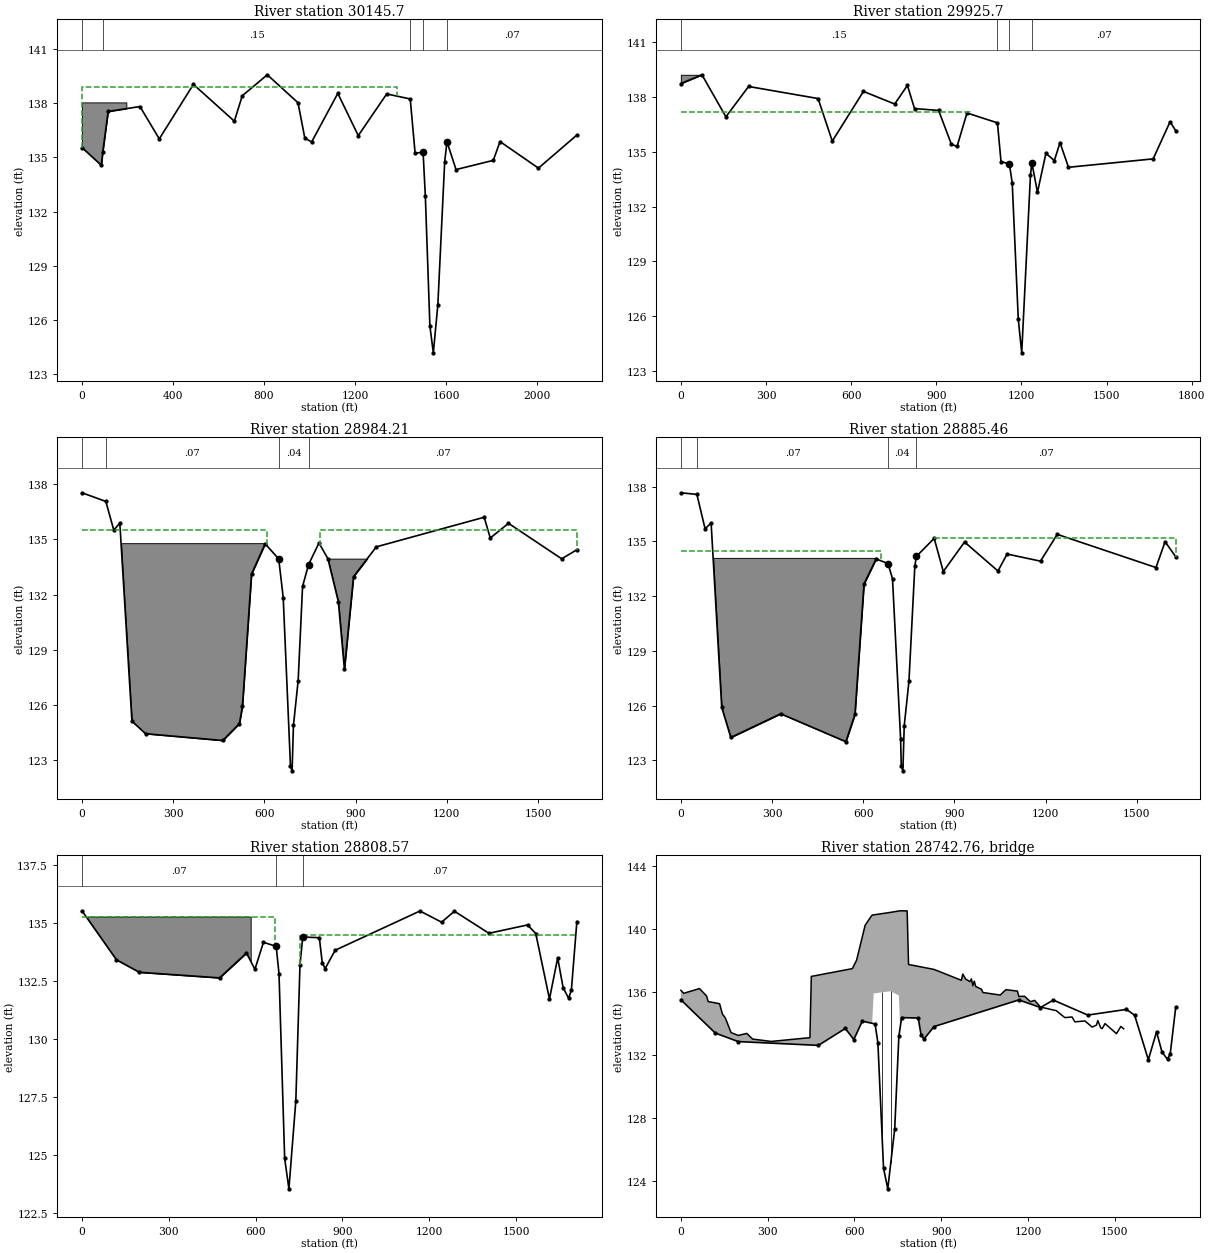
Type RM Length L Ch R = 1 ,30145.7 ,237.32,220,202.53
XS GIS Cut Line= 5
3023660.7087648713895054.40527083022853.7087384513893899.4052842
3022788.70854037   13893663.40513022620.7085482813893436.4052259
3022458.7085441913893261.4052479
#Sta/Elev= 30
       0  135.55   84.94  134.57    91.4  135.31  114.92  137.55  254.82  137.82
  339.76  136.03  489.65  139.05  669.52  137.01   704.5  138.42  814.42  139.58
  949.32  138.03   979.3  136.07 1009.28  135.86  1124.2  138.55 1214.14  136.21
 1339.05  138.52 1442.46  138.24 1463.95  135.23 1498.92   135.3 1508.91  132.85
 1528.89  125.66 1543.95  124.18 1563.86  126.85 1593.84  134.76 1603.83  135.87
 1643.79  134.33 1807.37  134.84  1837.1  135.88 2005.75  134.41 2174.66  136.24
#Mann= 5 ,-1 , 0
       0     .07       0    91.4     .15       0 1442.46     .07       0
 1498.92     .04       0 1603.83     .07       0
#XS Ineff= 2 ,-1
       0 1384.01   138.9 1603.83 2174.66  135.87
Permanent Ineff=
       F       F
#Block Obstruct= 2 , 0
       0  194.86  138.05               0
Bank Sta=1498.92,1603.83
XS Rating Curve= 0 ,0
Exp/Cntr=0.3,0.1

Type RM Length L Ch R = 1 ,29925.7 ,934.28,941.49,952.9
XS GIS Cut Line= 5
3023701.0000228613894592.00002763023621.9998527813894483.9999155
3023037.0000385213893685.99987113022933.9999164513893566.0001111
3022576.9999742813893272.0000429
#Sta/Elev= 30
       0  138.73   74.34  139.21   158.8  136.91  238.75  138.57  483.62  137.91
  533.59  135.58  643.53   138.3  753.47  137.61  798.45  138.63  823.43  137.36
  908.39  137.26  953.36  135.41  973.35  135.29 1008.33  137.12 1115.69  136.58
 1128.21  134.46 1157.86  134.33 1167.75  133.28 1189.11  125.83 1201.19     124
 1231.99  133.71 1236.93  134.39  1256.7  132.78 1286.38  134.91 1316.22  134.52
 1336.11   135.5 1365.95  134.15 1664.33  134.61    1724  136.64 1743.89  136.15
#Mann= 4 ,-1 , 0
       0     .15       0 1115.69     .07       0 1157.86     .04       0
 1236.93     .07       0
#XS Ineff= 2 ,-1
       0 1018.33  137.18 1336.11 1743.89   135.5
Permanent Ineff=
       F       F
#Block Obstruct= 2 , 0
       0   74.34  139.21    1724       0  136.64
Bank Sta=1157.86,1236.93
XS Rating Curve= 0 ,0
Exp/Cntr=0.3,0.1

Type RM Length L Ch R = 1 ,28984.21,98.36,98.74,99.68
XS GIS Cut Line= 4
3023802.0992301113893597.86290833023634.0992380213892977.8628359
3023564.0990499413892794.86287393023268.0989857813892062.8630255
#Sta/Elev= 30
       0  137.54   78.53  137.07  104.57  135.51  124.49  135.89  164.32  125.12
  209.14  124.44   463.1  124.07  517.87  124.99  527.83  125.93  557.71  133.12
  602.52  134.77  647.26  133.94  661.95  131.84  685.88  122.67  691.18  122.42
  695.62  124.89  711.13  127.33  725.63  132.45  745.22  133.63  779.51  134.81
   808.9  133.96  843.29  131.62  863.28  127.95  893.26  132.98  968.22   134.6
 1323.03  136.21 1343.02  135.08 1402.99  135.88  1577.9  133.95 1627.87  134.44
#Mann= 4 ,-1 , 0
       0     .15       0   78.53     .07       0  647.26     .04       0
  745.22     .07       0
#XS Ineff= 2 ,-1
       0   607.5   135.5  784.41 1627.87   135.5
Permanent Ineff=
       F       F
#Block Obstruct= 2 ,-1
  114.53   607.5   134.8   808.9  943.23  133.96
Bank Sta=647.26,745.22
XS Rating Curve= 0 ,0
Exp/Cntr=0.3,0.1

Type RM Length L Ch R = 1 ,28885.46,76.09,76.9,76.18
XS GIS Cut Line= 4
3023896.9999589513893578.00008713023728.9999668613892958.0000148
3023659.0001068613892775.00005273023363.0000426913892042.9998763
#Sta/Elev= 30
       0  137.67   52.83  137.58   79.67   135.7   99.59  136.01  134.45   125.9
  164.32  124.25  328.65  125.55  542.77  124.02  572.64  125.51  602.52  132.67
  642.36  134.04  681.54  133.79  696.24  132.95  722.95  124.15  725.07  122.67
  730.37  122.42  734.81  124.89  750.32  127.33  769.71  133.65  774.61  134.18
  833.39  135.17  863.28  133.35  933.24  134.97 1043.18  133.38 1073.17  134.31
 1183.11  133.92 1238.08  135.39 1562.91  133.57 1592.89  134.99 1627.87  134.16
#Mann= 4 ,-1 , 0
       0     .15       0   52.83     .07       0  681.54     .04       0
  774.61     .07       0
#XS Ineff= 2 ,-1
       0  657.05   134.5  833.39 1627.87  135.17
Permanent Ineff=
       F       F
#Block Obstruct= 1 ,-1
   94.61  647.26   134.1
Bank Sta=681.54,774.61
XS Rating Curve= 0 ,0
Exp/Cntr=0.5,0.3

Type RM Length L Ch R = 1 ,28808.57,131.88,131.69,132.83
BEGIN DESCRIPTION:
Upstream Section (QUEENSTON BLVD)
END DESCRIPTION:
XS GIS Cut Line= 6
 3023933.527444913893526.7505177 3023898.720099913893296.2828028
 3023788.942104213892902.9115423 3023557.286399513892284.3264934
 3023495.149384713892064.8272604   3023391.89749  13891917.38559
#Sta/Elev= 30
       0  135.51  119.02   133.4  198.37  132.86  475.47  132.62  568.45  133.69
  597.81  132.99  627.18  134.15  671.22  133.98  681.01   132.8  700.58  124.84
  715.26  123.53  739.18  127.33  753.54  133.19   763.1  134.38  820.51  134.35
  830.45  133.27  840.39  133.02  875.16  133.81 1168.29   135.5 1242.82  135.02
 1287.53  135.49 1406.58  134.54 1540.03   134.9 1568.44  134.53 1615.79  131.71
  1644.2  133.48 1663.14  132.19 1682.08  131.74 1691.55  132.09 1710.49  135.04
#Mann= 3 ,-1 , 0
       0     .07       0  671.22     .04       0   763.1     .07       0
#XS Ineff= 2 ,-1
       0  666.33  135.26  753.54 1710.49  134.48
Permanent Ineff=
       F       F
#Block Obstruct= 2 , 0
       0  583.13  135.26               0
Bank Sta=671.22,763.1
XS Rating Curve= 0 ,0
Exp/Cntr=0.5,0.3

Type RM Length L Ch R = 3 ,28742.76,,,
BEGIN DESCRIPTION:
QUEENSTON BLVD
U06_1300
Energy Only used for Low Flow Method to remove negative surcharge for FW Model
END DESCRIPTION:
Node Name=QUEENSTON BLVD
Bridge Culvert--1,0,-1,-1, 0
Deck Dist Width WeirC Skew NumUp NumDn MinLoCord MaxHiCord MaxSubmerge Is_Ogee
22,95,2.6,0, 60, 60, , , 0.98, 0, 0,0,,
       0    9.92   64.47   89.27   94.22   133.9  143.82  153.73  173.57  198.37
  228.12  247.94  312.35   446.1     451  592.92   607.6  636.96  656.54  661.43
  666.33  724.83  753.54  758.32   763.1  782.24  787.02  875.16  969.56  974.53
  984.47  999.37 1004.34 1009.31 1014.27 1019.24 1039.12 1044.08  1103.7 1123.58
 1163.32 1168.29 1188.16 1208.04 1222.94 1242.82 1297.47 1327.23 1352.03 1361.94
 1396.66 1421.46 1436.33 1441.29 1451.21 1456.17 1466.09 1505.76 1520.64 1530.56
  136.11  135.92  136.22  135.74   135.4  135.26   134.6  134.36  133.43  133.25
  133.38  133.02  132.87  133.11136.9904137.4841138.0269140.2299 140.764140.8735
  140.89 141.048141.1358141.1471141.1486 141.141137.7457137.4334136.7448  137.14
  136.82  136.66  136.83   136.4  136.69  136.35  136.18  135.97  135.81  136.15
  136.06  135.72  135.73  135.39  135.47  135.05  134.82  134.38  134.42  134.11
  134.17  133.78   133.9  134.19  133.73  133.68     134  133.36  133.82  133.67
       0       0       0       0       0       0       0       0       0       0
       0       0       0       0       0       0       0       0       023.60663
  135.91136.0493 135.78339.03387       0       0       0       0       0       0
       0       0       0       0       0       0       0       0       0       0
       0       0       0       0       0       0       0       0       0       0
       0       0       0       0       0       0       0       0       0       0
       0    9.92   64.47   89.27   94.22   133.9  143.82  153.73  173.57  198.37
  228.12  247.94  312.35   446.1     451   607.6   612.5  632.07  636.96  656.54
  661.43  666.33  724.83  753.54  758.32   763.1  782.24  787.02  810.95  825.48
  969.56  974.53  999.37 1004.34 1009.31 1014.27 1019.24 1044.08  1103.7 1123.58
 1163.32 1168.29 1188.16 1208.04 1222.94 1242.82 1297.47 1327.23 1352.03 1361.94
 1396.66 1421.46 1436.33 1441.29 1451.21 1456.17 1466.09 1505.76 1520.64 1530.56
  136.11  135.92  136.22  135.74   135.4  135.26   134.6  134.36  133.43  133.25
  133.38  133.02  132.87  133.11136.8806  137.74138.1003140.5236140.9037140.9424
140.9517  140.96141.0785141.1372141.1471  141.12140.9511138.7893138.5265137.6977
136.5901  137.14  136.66  136.83   136.4  136.69  136.35  135.97  135.81  136.15
  136.06  135.72  135.73  135.39  135.47  135.05  134.82  134.38  134.42  134.11
  134.17  133.78   133.9  134.19  133.73  133.68     134  133.36  133.82  133.67
       0       0       0       0       0       0       0       0       0       0
       0       0       0       0       0       0       0       0       0       0
  23.657   136.2136.3588136.188339.15175       0       0       0       0       0
       0       0       0       0       0       0       0       0       0       0
       0       0       0       0       0       0       0       0       0       0
       0       0       0       0       0       0       0       0       0       0
Pier Skew, UpSta & Num, DnSta & Num=  ,695.57, 2 ,695.57, 2 , 0 , 0 , 0 ,,
     1.5     1.5
     120  136.02
     1.5     1.5
     120  136.31
Pier Skew, UpSta & Num, DnSta & Num=  ,725.57, 2 ,725.57, 2 , 0 , 0 , 0 ,,
     1.5     1.5
     120  136.05
     1.5     1.5
     120  136.36
Abutment Skew #Up #Dn= , 4 , 4
   660.4  666.33  695.57  700.24
  137.93  135.78  125.18  123.49
   660.4  666.33  695.57  700.24
   138.2  135.95  124.83  123.06
Abutment Skew #Up #Dn= , 5 , 5
  719.49  725.57   754.9   759.7   765.7
  123.22  125.21  134.83   136.4  138.37
  719.49  725.57   754.9   759.7   765.7
  123.09  125.07  134.64   136.2  138.16
BR Coef=-1 , 0 , 0 ,1.25, 0 ,,,0.8,-1,2,1,
WSPro=,,,, 1 ,,,, 0 ,,,, 0 ,,,,-1 ,-1 ,-1 , 0 , 0 , 0 , 0 , 0
BR U #Sta/Elev= 30
       0  135.51  119.02   133.4  198.37  132.86  475.47  132.62  568.45  133.69
  597.81  132.99  627.18  134.15  671.22  133.98  681.01   132.8  700.58  124.84
  715.26  123.53  739.18  127.33  753.54  133.19   763.1  134.38  820.51  134.35
  830.45  133.27  840.39  133.02  875.16  133.81 1168.29   135.5 1242.82  135.02
 1287.53  135.49 1406.58  134.54 1540.03   134.9 1568.44  134.53 1615.79  131.71
  1644.2  133.48 1663.14  132.19 1682.08  131.74 1691.55  132.09 1710.49  135.04
BR U #Mann= 3
       0     .07  671.22    .015   763.1     .07
BR D #Sta/Elev= 30
       0  136.14   59.51  135.84  453.92  137.28  568.45  137.18  646.75  136.16
  666.33  135.14  695.69  126.93  710.37  123.43  715.26  123.23  729.61  125.84
  748.75  132.68   763.1  136.08  810.95  136.05  850.32  133.97   870.2  134.77
  909.94  133.83  929.82  134.29  954.66   133.3  974.53  134.45  989.43  133.84
 1073.89  133.95 1213.01  132.92 1451.21  134.11 1540.03  133.03 1568.44  131.78
 1606.32  133.29 1625.26  131.91 1634.73  131.93 1682.08  132.97 1710.49  134.31
BR D #Mann= 4
       0     .15  453.92     .07  666.33    .015   763.1     .07
BC Design=,, 0 ,, 0 ,,,,,,
BC Use User HTab Curves=0
BC User HTab FreeFlow(D)= 0

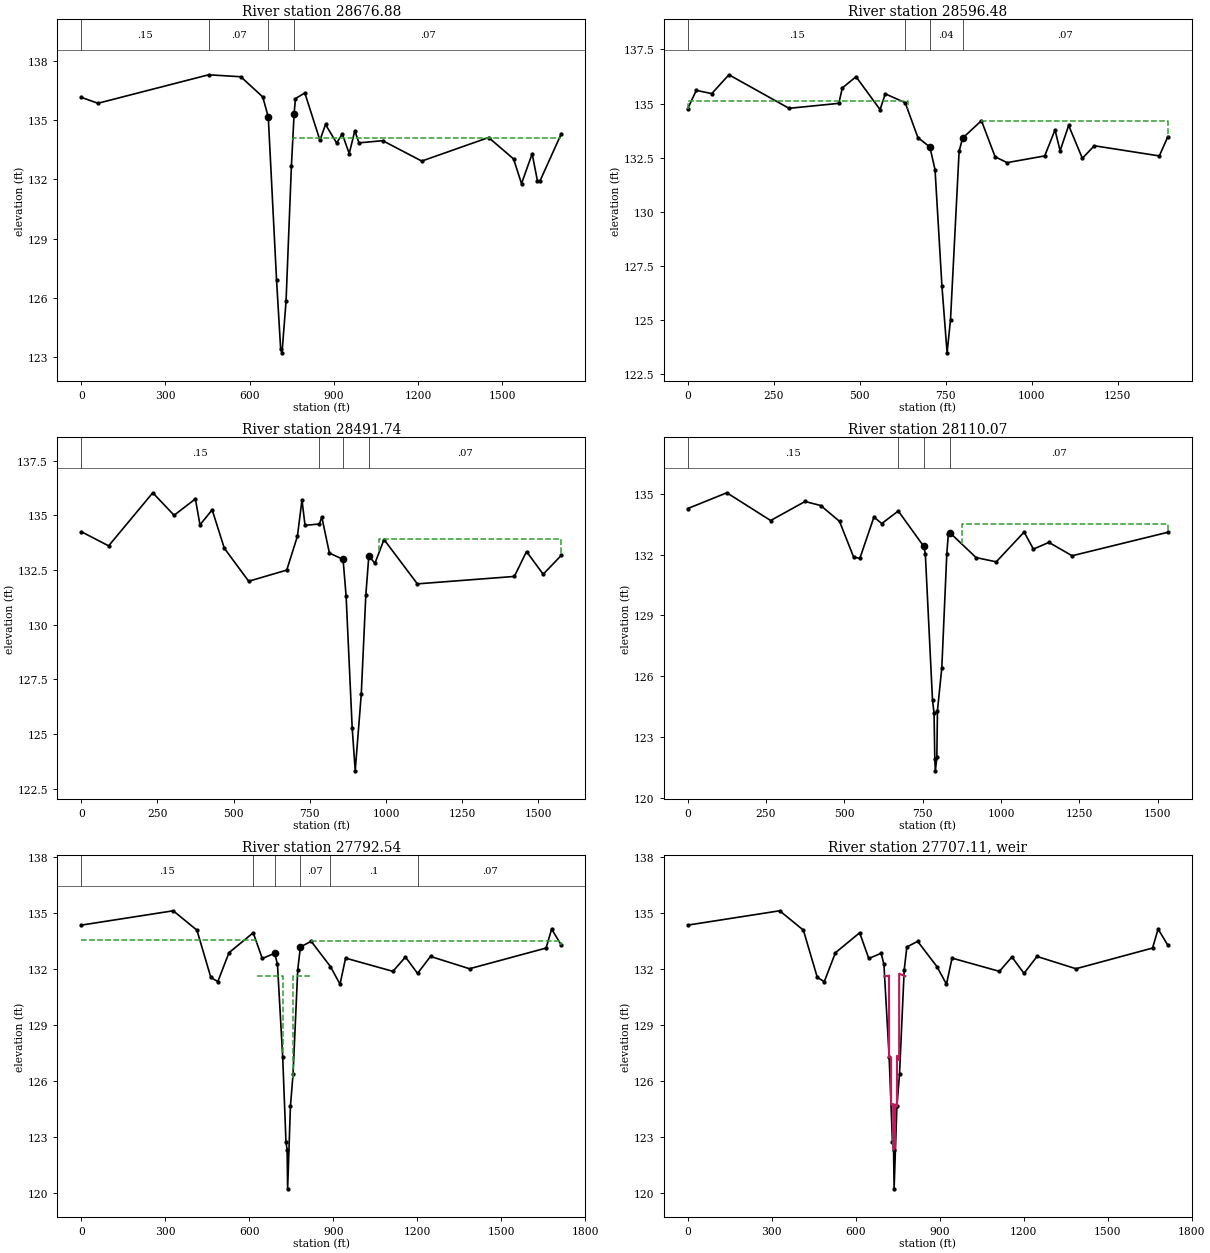
Type RM Length L Ch R = 1 ,28676.88,80.39,80.4,82.27
BEGIN DESCRIPTION:
Downstream Section (QUEENSTON BLVD)
END DESCRIPTION:
Node Name=AF
XS GIS Cut Line= 6
   3024048.6650113893463.0426399 3024013.857664913893232.5749249
 3023965.067408113893025.2164158 3023672.423964513892220.6186155
 3023610.286949713892001.1193826   3023579.31048  13891823.80481
#Sta/Elev= 30
       0  136.14   59.51  135.84  453.92  137.28  568.45  137.18  646.75  136.16
  666.33  135.14  695.69  126.93  710.37  123.43  715.26  123.23  729.61  125.84
  748.75  132.68  758.32  135.31   763.1  136.08  796.59  136.36  850.32  133.97
   870.2  134.77  909.94  133.83  929.82  134.29  954.66   133.3  974.53  134.45
  989.43  133.84 1073.89  133.95 1213.01  132.92 1451.21  134.11 1540.03  133.03
 1568.44  131.78 1606.32  133.29 1625.26  131.91 1634.73  131.93 1710.49  134.31
#Mann= 4 ,-1 , 0
       0     .15       0  453.92     .07       0  666.33     .04       0
  758.32     .07       0
#XS Ineff= 2 ,-1
       0  666.33  134.26  753.54 1710.49  134.08
Permanent Ineff=
       F       F
Bank Sta=666.33,758.32
XS Rating Curve= 0 ,0
Exp/Cntr=0.5,0.3

Type RM Length L Ch R = 1 ,28596.48,104.35,104.73,104.62
XS GIS Cut Line= 4
3024192.00002511 13893445.0000253023973.0001350313892801.9999987
3023920.9999109513892655.99996263023696.0000328613892141.0000084
#Sta/Elev= 30
       0  134.76   24.97  135.61   69.93  135.46  119.87  136.33  294.68  134.78
  439.53  135.01  449.52  135.72  489.48  136.24   559.4  134.72  574.38  135.45
  632.45  135.04  669.28  133.43  704.27  132.99  719.27  131.94  739.27  126.57
  754.26  123.48  764.26  125.02  789.26   132.8  799.26   133.4  854.15  134.21
  893.94  132.54  928.75  132.27 1038.17  132.58 1068.01  133.78 1082.93  132.82
  1107.8  133.99 1147.59  132.47  1182.4  133.05 1371.39  132.58 1396.26  133.47
#Mann= 4 ,-1 , 0
       0     .15       0  632.45     .07       0  704.27     .04       0
  799.26     .07       0
#XS Ineff= 2 ,-1
       0  639.31  135.13  854.15 1396.26  134.21
Permanent Ineff=
       F       F
Bank Sta=704.27,799.26
XS Rating Curve= 0 ,0
Exp/Cntr=0.3,0.1

Type RM Length L Ch R = 1 ,28491.74,390.18,381.68,371.28
XS GIS Cut Line= 5
3024273.0064247713893557.20025993024104.63274577 13892899.127101
3024064.1347952813892749.52799083023879.8333266113892218.6015592
3023718.2919830213892141.1102443
#Sta/Elev= 30
       0  134.26    89.9  133.61  234.75  136.04  304.67  135.01   374.6  135.76
  389.58  134.57  429.54  135.26   469.5   133.5  549.41  131.99  674.28   132.5
  709.27  134.05  724.27  135.71  734.27  134.55  781.43  134.61  789.26  134.93
  814.26  133.28  859.12  132.99  869.07  131.31  888.96  125.29  898.91  123.31
  918.81  126.82  933.73  131.36  943.67  133.15  963.57  132.81  993.41   133.9
 1102.83  131.87 1421.15  132.21 1460.96  133.35 1515.71  132.31 1575.43  133.18
#Mann= 4 ,-1 , 0
       0     .15       0  781.43     .07       0  859.12     .04       0
  943.67     .07       0
#XS Ineff= 2 ,-1
       0  799.26  133.94  978.49 1575.43  133.92
Permanent Ineff=
       F       F
Bank Sta=859.12,943.67
XS Rating Curve= 0 ,0
Exp/Cntr=0.3,0.1

Type RM Length L Ch R = 1 ,28110.07,321.17,317.52,313.62
XS GIS Cut Line= 5
3024818.4246252813893140.0810154 3024411.999913213892546.9998525
 3024315.000107213892424.00009853024046.9999870213892256.0001064
3023731.9999608513892128.0000343
#Sta/Elev= 30
       0  134.27  124.82  135.05  264.62  133.68  374.47  134.62   424.4  134.42
  484.31  133.64  529.25  131.88  549.22  131.81  594.15  133.85  619.12  133.53
  671.87  134.15  753.24   132.4  758.14  132.03  781.08   124.8  785.95  124.18
  788.38   121.9  790.16  121.32  794.88  121.98  796.83  124.29  810.78  126.42
  826.67  132.05  831.57     133  836.46  133.08   920.1  131.85  984.35  131.64
 1073.31  133.11 1102.97  132.27 1152.39   132.6 1226.42  131.94 1531.94   133.1
#Mann= 4 ,-1 , 0
       0     .15       0  671.87     .07       0  753.24     .04       0
  836.46     .07       0
#XS Ineff= 2 ,-1
       0   694.1   133.5  875.62 1531.94   133.5
Permanent Ineff=
       F       F
Bank Sta=753.24,836.46
XS Rating Curve= 0 ,0
Exp/Cntr=0.5,0.3

Type RM Length L Ch R = 1 ,27792.54,128.35,128.14,129.43
BEGIN DESCRIPTION:
Upstream Section (INLINE WEIR)
END DESCRIPTION:
Node Name=AE
XS GIS Cut Line= 6
3024926.1619426213892942.53416643024705.1591037813892382.1852215
 3024611.599907713892287.65391453024571.6190165313892247.2576699
3024512.9593569513892189.41821863023679.4971131113892081.6710588
#Sta/Elev= 30
       0  134.36  328.56  135.13  413.19  134.09  462.97  131.55  487.86  131.33
  527.68  132.88  614.22  133.95  646.69  132.57  691.02  132.85  700.88  132.25
  719.57  127.27   731.3  122.71  735.29  122.32   737.2  120.21  747.12  124.63
  756.52  126.36  773.25  131.95  782.72  133.19  821.27  133.49  889.94  132.14
   924.3  131.19  944.19  132.59 1113.27  131.88 1158.02  132.65 1201.18  131.77
 1247.53  132.68 1386.77  132.02 1660.27  133.13 1680.16  134.15 1714.97  133.28
#Mann= 6 ,-1 , 0
       0     .15       0  614.22     .07       0  691.02     .04       0
  782.72     .07       0  889.94      .1       0 1201.18     .07       0
#XS Ineff= 4 ,-1
       0  626.99  133.54  626.99  718.98  131.61  755.46  821.27  131.65
  821.27 1714.97  133.49
Permanent Ineff=
       F       F       F       F
Bank Sta=691.02,782.72
XS Rating Curve= 0 ,0
Exp/Cntr=0.5,0.3

Type RM Length L Ch R = 5 ,27707.11,,,
BEGIN DESCRIPTION:
INLINE WEIR
END DESCRIPTION:
Node Name=INLINE WEIR
IW Pilot Flow=0
#Inline Weir SE= 14
  702.59  131.61  718.98  131.65  719.23  127.27  726.51  127.26  726.58  124.74
   733.9  124.75  734.68  122.32  739.84  122.42  740.88  124.74  747.42  124.63
  747.52  127.35  755.11  127.13  755.46  131.75  777.58  131.62
IW Dist,WD,Coef,Skew,MaxSub,Min_El,Is_Ogee,SpillHt,DesHd
85,1,2.6,0,0.98,, 0 ,,,0,0,

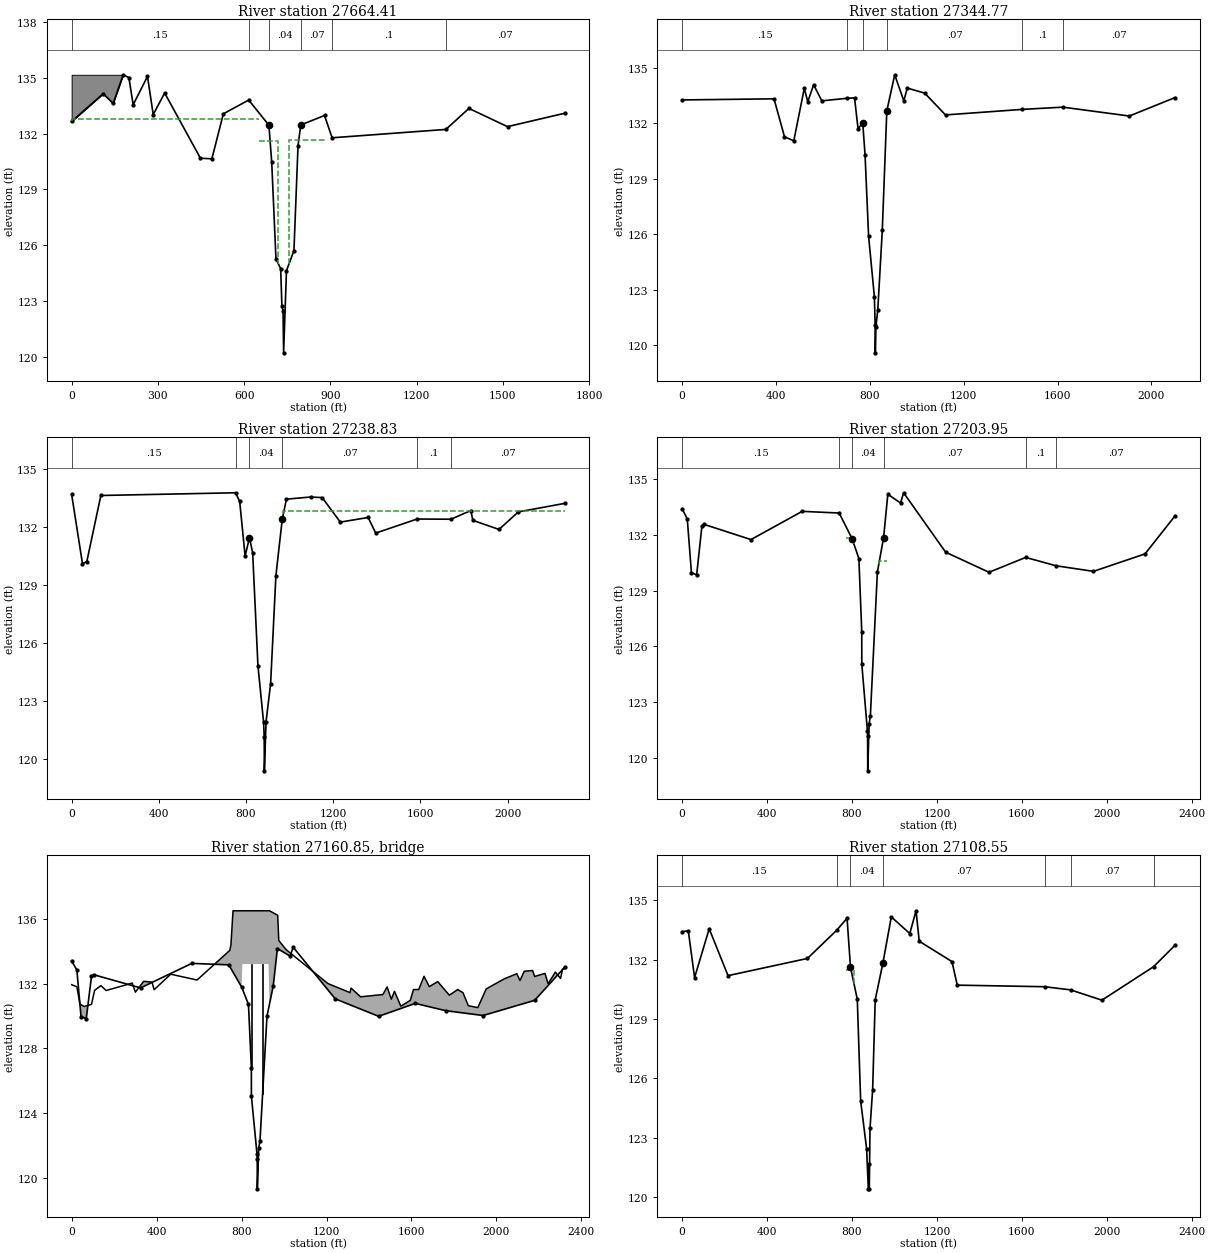
Type RM Length L Ch R = 1 ,27664.41,306.18,319.64,306.83
BEGIN DESCRIPTION:
Downstream Section (INLINE WEIR)
END DESCRIPTION:
Node Name=AD
XS GIS Cut Line= 6
 3025024.132547213892859.94738933024803.1297083613892299.5984444
3024709.5705122813892205.06713743024669.5896211113892164.6708928
3024610.9299615313892106.83144153023772.9821623613892042.7029608
#Sta/Elev= 30
       0  132.66  109.52  134.15  144.37  133.63  179.21  135.17  199.13  135.02
  214.06  133.56  263.84  135.08  283.75  133.03  323.58  134.19  448.03  130.68
  487.86  130.65  527.68  133.07  615.93  133.81   686.1  132.46  695.95  130.47
  710.73  125.26  727.04  124.74  731.44  122.71  735.36  122.48  737.34  120.21
  747.26  124.63  773.25  125.71  787.46  131.36  797.04  132.47  879.55  132.98
  906.03  131.78 1301.72  132.23 1381.79  133.36 1516.06  132.38 1714.97   133.1
#Mann= 6 ,-1 , 0
       0     .15       0  615.93     .07       0   686.1     .04       0
  797.04     .07       0  906.03      .1       0 1301.72     .07       0
#XS Ineff= 4 ,-1
       0  651.62  132.79  651.62  718.98  131.61  755.46  879.55  131.65
  879.55 1714.97  132.98
Permanent Ineff=
       F       F       F       F
#Block Obstruct= 2 , 0
       0  179.21  135.17               0
Bank Sta=686.1,797.04
XS Rating Curve= 0 ,0
Exp/Cntr=0.5,0.3

Type RM Length L Ch R = 1 ,27344.77,130.23,105.94,78.31
XS GIS Cut Line= 6
3025543.4162855313892564.72422653025145.0922790313892206.4437751
3024862.9999954413891924.00011433024641.3918428613891909.2813117
3024331.5843916113891926.14184233023708.0000088713892035.9998903
#Sta/Elev= 30
       0  133.25  391.89  133.31  436.54  131.26  476.22  131.04  520.87  133.88
  535.75  133.15  560.66  134.07  595.53   133.2  703.29  133.34  735.03  133.36
  749.97  131.69   769.9  132.01  779.87  130.26  794.81  125.89  819.55  122.61
  822.72  121.08  823.46  119.58     826     121  833.98   121.9  853.22   126.2
  872.46  132.66  906.12  134.61  944.85   133.2  959.66  133.89 1033.69  133.62
 1122.53  132.44  1450.4  132.74 1622.55  132.86 1905.71  132.38 2100.69  133.38
#Mann= 6 ,-1 , 0
       0     .15       0  703.29     .07       0   769.9     .04       0
  872.46     .07       0  1450.4      .1       0 1622.55     .07       0
#XS Ineff= 2 ,-1
       0  520.87  133.15  959.66 2100.69  133.32
Permanent Ineff=
       F       F
Bank Sta=769.9,872.46
XS Rating Curve= 0 ,0
Exp/Cntr=0.3,0.1

Type RM Length L Ch R = 1 ,27238.83,34.11,34.88,32.68
XS GIS Cut Line= 6
3025819.0000519513892318.99998043025489.0000557813892126.0000384
3025084.9998795213891956.00005033024841.0000394413891898.9998362
3024303.0001311913891875.99988223023667.0000908713892011.9999383
#Sta/Elev= 30
       0   133.7   49.65  130.11   69.51  130.21  134.05  133.64  751.83  133.78
   770.8  133.33   795.7   130.5  815.62  131.45  830.29  130.67  854.51  124.82
  880.37  121.89  883.21  121.13  883.98  119.37  891.74  121.92  912.65  123.89
  936.87  129.48  965.93   132.4  985.12  133.45  1095.8  133.56 1149.31  133.53
 1232.28  132.26 1360.21   132.5 1394.65  131.69 1584.55  132.42  1740.5  132.41
 1830.46  132.86 1840.45  132.35 1960.06  131.88 2048.99  132.79 2261.42  133.23
#Mann= 6 ,-1 , 0
       0     .15       0  751.83     .07       0  815.62     .04       0
  965.93     .07       0 1584.55      .1       0  1740.5     .07       0
#XS Ineff= 2 ,-1
       0  775.75  132.76  970.73 2261.42  132.83
Permanent Ineff=
       F       F
Bank Sta=815.62,965.93
XS Rating Curve= 0 ,0
Exp/Cntr=0.5,0.3

Type RM Length L Ch R = 1 ,27203.95,101.1,95.4,103.81
BEGIN DESCRIPTION:
Upstream Section (WEST ROAD)
1. Channel Data has been skewed by 35 deg.
2. Bridge and overbank was not skewed.
END DESCRIPTION:
Node Name=AC
XS GIS Cut Line= 6
3025833.5265976913892291.17916993025406.36045727 13892032.329622
3024754.5727188613891859.14820993024121.09760787 13891856.526824
 3023789.2117887 13891919.2117383023635.2619653613891992.9727454
#Sta/Elev= 30
       0  133.42   24.61  132.86   44.29  129.97    68.9  129.85   93.51  132.47
  103.35  132.57  324.61  131.75  565.63  133.27 739.785  133.18  800.64   131.8
 832.595  130.73 846.185   126.8 846.398  125.04 872.955  121.43 873.725  121.15
 874.364   119.3 880.819  121.83  886.61  122.24 919.786     130  949.07  131.86
 968.935  134.19 1028.61  133.72 1043.16  134.27 1241.23  131.07 1445.35  129.99
 1617.96  130.79 1761.02  130.34 1937.14  130.04 2179.98  130.98 2321.43  133.03
#Mann= 6 ,-1 , 0
       0     .15       0 739.785     .07       0  800.64     .04       0
  949.07     .07       0 1617.96      .1       0 1761.02     .07       0
#XS Ineff= 4 ,-1
       0  769.73  132.24  769.73  809.76  131.83  926.65  965.56  130.62
  965.56 2321.43  131.86
Permanent Ineff=
       F       F       F       F
Bank Sta=800.64,949.07
XS Rating Curve= 0 ,0
Exp/Cntr=0.5,0.3

Type RM Length L Ch R = 3 ,27160.85,,,
BEGIN DESCRIPTION:
WEST ROAD
END DESCRIPTION:
Node Name=WEST ROAD
Bridge Culvert--1,0,-1,-1, 0
Deck Dist Width WeirC Skew NumUp NumDn MinLoCord MaxHiCord MaxSubmerge Is_Ogee
11,76.5,2.6,0, 60, 60, , , 0.98, 0, 0,0,,
       0   24.61   39.37   59.06   93.51  108.27   137.8  162.41  285.44  300.13
   339.3  378.47  388.27  466.61  590.53  744.93  749.91  759.87   774.6  779.48
  798.99  803.86  926.65  931.61  970.41  975.26 1009.21 1206.53 1310.62 1315.58
 1360.39 1465.35 1485.34 1505.19 1520.08 1549.87 1594.55 1609.44 1634.26 1659.08
  1683.9 1723.61 1778.22 1817.93 1842.77  1867.6  1912.3 1952.04 2036.48 2096.08
 2110.98 2130.85 2170.23 2179.98 2228.76 2243.39 2277.53 2301.92 2311.67 2321.43
  131.95  131.82  130.74   130.6  130.73   131.6  131.89  131.59  132.05  131.49
  132.16  132.11  131.64   132.6  132.24  134.08  134.41  136.53  136.53  136.53
  136.53  136.53  136.53  136.53  136.25  134.69  134.13  132.02  131.46  131.74
   131.2  131.34  131.81  131.05  131.54  130.62  130.98  131.65  131.65  132.47
  131.83  132.14   131.3  131.65  131.45  130.65  130.53  131.69  132.31  132.63
  132.21  132.78  132.83  132.46  132.65  132.01  132.73  132.34  132.93  132.93
       0       0       0       0       0       0       0       0       0       0
       0       0       0       0       0       0       0       0       0   16.31
  119.29  133.23  133.23       0       0       0       0       0       0       0
       0       0       0       0       0       0       0       0       0       0
       0       0       0       0       0       0       0       0       0       0
       0       0       0       0       0       0       0       0       0       0
       0   24.61   39.37   59.06   93.51  108.27   137.8  162.41  285.44  300.13
   339.3  378.47  388.27  466.61  590.53  744.93  749.91  759.87   774.6  779.48
  798.99  803.86  926.65  931.61  970.41  975.26 1009.21 1206.53 1310.62 1315.58
 1360.39 1465.35 1485.34 1505.19 1520.08 1549.87 1594.55 1609.44 1634.26 1659.08
  1683.9 1723.61 1778.22 1817.93 1842.77  1867.6  1912.3 1952.04 2036.48 2096.08
 2110.98 2130.85 2170.23 2179.98 2228.76 2243.39 2277.53 2301.92 2311.67 2321.43
  131.95  131.82  130.74   130.6  130.73   131.6  131.89  131.59  132.05  131.49
  132.16  132.11  131.64   132.6  132.24  134.08  134.41  136.53  136.53  136.53
  136.53  136.53  136.53  136.53  136.25  134.69  134.13  132.02  131.46  131.74
   131.2  131.34  131.81  131.05  131.54  130.62  130.98  131.65  131.65  132.47
  131.83  132.14   131.3  131.65  131.45  130.65  130.53  131.69  132.31  132.63
  132.21  132.78  132.83  132.46  132.65  132.01  132.73  132.34  132.93  132.93
       0       0       0       0       0       0       0       0       0       0
       0       0       0       0       0       0       0       0       0    16.3
  119.21  133.14  133.14       0       0       0       0       0       0       0
       0       0       0       0       0       0       0       0       0       0
       0       0       0       0       0       0       0       0       0       0
       0       0       0       0       0       0       0       0       0       0
Pier Skew, UpSta & Num, DnSta & Num=  ,846.2, 2 ,846.2, 2 , 0 , 0 , 0 ,,
     1.4     1.4
  123.95  134.23
     1.4     1.4
  123.86  134.14
Pier Skew, UpSta & Num, DnSta & Num=  ,899.2, 2 ,899.2, 2 , 0 , 0 , 0 ,,
     1.4     1.4
  124.04  134.23
     1.4     1.4
  123.95  134.14
Abutment Skew #Up #Dn= , 2 , 2
  801.52  809.76
  133.23  132.63
  801.52  809.76
  133.14  132.54
Abutment Skew #Up #Dn= , 2 , 2
  886.68  931.46
  122.24  133.23
  886.68  931.46
  122.15  133.14
BR Coef=-1 , 1 , 1 ,0.9, 0 ,,,0.8,-1,1.2,0,
WSPro=,,,, 1 ,,,, 0 ,,,, 0 ,,,,-1 ,-1 ,-1 , 0 , 0 , 0 , 0 , 0
BC Design=,, 0 ,, 0 ,,,,,,
BC Use User HTab Curves=0
BC User HTab FreeFlow(D)= 0

Type RM Length L Ch R = 1 ,27108.55,53.18,75.69,54.32
BEGIN DESCRIPTION:
Downstream Section (WEST ROAD)
1. Channel Data has been skewed by 35 deg.
2. Bridge and overbank was not skewed.
END DESCRIPTION:
Node Name=AB
XS GIS Cut Line= 6
   3025929.29663  13892163.80262 3025221.335236813891876.9345916
 3024819.265502913891789.3094388 3024512.257258613891759.1546434
 3023853.904572713891849.3729669 3023683.206423313891847.5288105
#Sta/Elev= 30
       0  133.42   29.52  133.47   59.04   131.1  127.92  133.57  216.48   131.2
  590.53  132.07  727.62  133.49  776.99   134.1 793.135  131.63  825.09  130.01
 841.072  124.86 869.054  122.45 877.074  120.42 881.128  121.67 881.358  120.42
 885.191   123.5  897.38  125.43 909.569  129.98 945.588  131.83 985.316  134.17
 1072.25  133.33  1101.8  134.48  1116.8  132.94 1270.97  131.91 1295.75  130.72
 1707.21  130.64  1829.6  130.48 1976.87  129.96 2219.88  131.65 2321.43  132.74
#Mann= 7 ,-1 , 0
       0     .15       0  727.62     .07       0 793.135     .04       0
 945.588     .07       0 1707.21      .1       0  1829.6     .07       0
 2219.88      .1       0
#XS Ineff= 4 ,-1
       0  769.73  131.83  769.73  809.76   131.5  926.65  960.71   130.4
  960.71 2321.43  131.83
Permanent Ineff=
       F       F       F       F
Bank Sta=793.135,945.588
XS Rating Curve= 0 ,0
Exp/Cntr=0.5,0.3

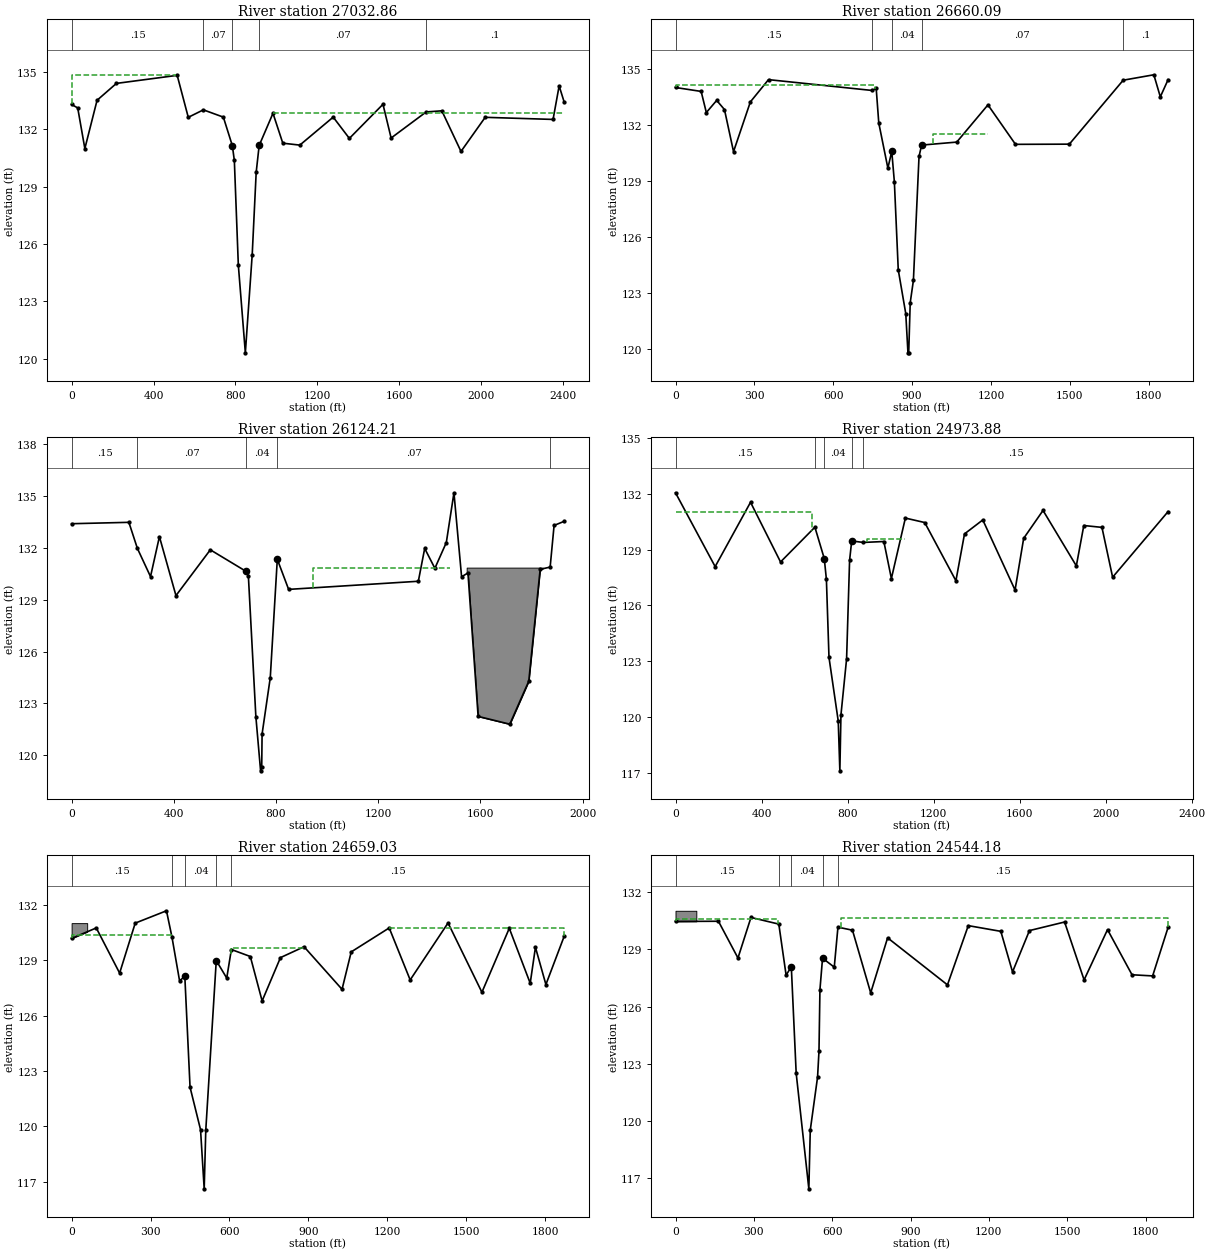
Type RM Length L Ch R = 1 ,27032.86,351.53,372.77,397.18
XS GIS Cut Line= 6
3025935.0001480313892157.99997443025618.0001258613891971.0000203
3025201.9999736113891824.99998423024665.0000633613891723.9998581
3024307.0001231913891723.99985813023623.9998487813891829.9999742
#Sta/Elev= 30
       0  133.28   29.84   133.1   64.66  130.98  124.34   133.5  218.84  134.38
  515.63   134.8  569.74  132.61  643.53     133  741.09  132.62  784.99  131.13
  794.75  130.36  814.22   124.9   848.5  120.32  882.04  125.45  901.42  129.74
  915.95  131.14  983.49  132.82 1031.47  131.26 1114.57  131.16 1277.53  132.62
 1356.54  131.51 1520.62  133.29  1560.4  131.53  1731.5  132.89  1808.1  132.95
 1901.67  130.83 2019.85  132.61  2351.3   132.5 2380.99  134.25 2405.73   133.4
#Mann= 5 ,-1 , 0
       0     .15       0  643.53     .07       0  784.99     .04       0
  915.95     .07       0  1731.5      .1       0
#XS Ineff= 3 ,-1
       0  505.79  134.83  505.79  643.53     133  983.46 2405.73  132.82
Permanent Ineff=
       F       F       F
#Block Obstruct= 2 , 0
       0                 2380.99       0  134.25
Bank Sta=784.99,915.95
XS Rating Curve= 0 ,0
Exp/Cntr=0.3,0.1

Type RM Length L Ch R = 1 ,26660.09,514.72,535.88,549.21
XS GIS Cut Line= 6
3026163.0000201213892066.0001584 3026118.000110113891984.9999923
3025542.9999477713891658.9999881 3025388.9999277 13891519.999938
3025185.8408851913891378.75842263024579.2814027813891105.2648751
#Sta/Elev= 30
       0  134.01   97.59   133.8   117.3  132.67  156.72  133.32  186.29  132.83
  220.78  130.58  284.85  133.24  353.83  134.43  748.92  133.85  763.54  133.97
  773.42  132.11     808   129.7  822.81  130.59  832.69  128.97  847.51  124.26
  876.07  121.92  884.43  119.82  887.28  119.82     893   122.5  905.13  123.69
  926.54  130.32  936.42  130.93 1069.99  131.09 1188.76  133.08 1293.51  130.97
 1498.43  130.98 1703.32   134.4 1819.92  134.69 1844.58  133.51 1874.18  134.43
#Mann= 5 ,-1 , 0
       0     .15       0  748.92     .07       0  822.81     .04       0
  936.42     .07       0 1703.32      .1       0
#XS Ineff= 3 ,-1
       0   758.6  134.12  980.91 1188.76  131.54 1188.76 1874.18  133.08
Permanent Ineff=
       F       F       F
#Block Obstruct= 2 , 0
       0    9.75  134.07 1819.92       0  134.69
Bank Sta=822.81,936.42
XS Rating Curve= 0 ,0
Exp/Cntr=0.3,0.1

Type RM Length L Ch R = 1 ,26124.21,1145.04,1150.33,1141.05
Node Name=AA
XS GIS Cut Line= 5
3026420.0001622713891825.99998223025946.0001260313891384.9998799
3025842.0000059513891194.99993193025377.9999496913890591.0001556
3025209.9999576113890340.0000014
#Sta/Elev= 30
       0   133.4  224.11  133.48  257.45  131.97  308.77  130.34  343.63  132.65
  408.37  129.24  542.84  131.89  681.88  130.65  691.73  130.38  721.07  122.23
  739.58   119.1  743.97  119.34   745.4  121.23  777.42  124.49  804.95  131.34
  849.26   129.6 1356.86  130.07 1381.75  131.97 1421.57  130.82 1466.37  132.31
 1496.24  135.19 1526.11  130.33    1551  130.55 1590.83  122.25  1714.8   121.8
 1789.07  124.29 1833.63  130.76 1872.67  130.89  1888.1   133.3 1927.71  133.54
#Mann= 5 ,-1 , 0
       0     .15       0  257.45     .07       0  681.88     .04       0
  804.95     .07       0 1872.67      .1       0
#XS Ineff= 3 ,-1
       0  542.84  131.89  943.67 1481.31  130.83 1481.31 1927.71  133.33
Permanent Ineff=
       F       F       F
#Block Obstruct= 1 ,-1
 1546.02 1843.53  130.86
Bank Sta=681.88,804.95
XS Rating Curve= 0 ,0
Exp/Cntr=0.3,0.1

Type RM Length L Ch R = 1 ,24973.88,310.99,314.85,315.06
XS GIS Cut Line= 6
 3027189.9999346 13891452.000074 3026963.000060513890855.9999537
 3026857.999942413890678.9999796 3026186.999972113889931.0001633
 3026159.000028113889841.0000152   3026055.85159  13889509.45025
#Sta/Elev= 30
       0  132.06  184.35  128.09  348.78  131.55  488.29  128.34     648  130.21
  691.67  128.52  701.47   127.4  713.49  123.21  756.47  119.79  764.02  117.11
  769.11  120.12  795.32  123.13  809.27  128.43  819.07  129.47  873.14  129.39
  968.55  129.44 1003.54  127.45 1068.54   130.7 1158.52  130.46  1303.5  127.33
  1343.5  129.85 1428.48   130.6 1578.46  126.83 1618.46  129.61 1708.44  131.11
  1863.3  128.13 1898.03   130.3 1982.36   130.2 2031.96  127.52 2289.88  131.05
#Mann= 5 ,-1 , 0
       0     .15       0     648     .07       0  691.67     .04       0
  819.07     .07       0  873.14     .15       0
#XS Ineff= 3 ,-1
       0  632.78  131.02  888.56 1068.54   129.6 1068.54 2289.88   130.7
Permanent Ineff=
       F       F       F
Bank Sta=691.67,819.07
XS Rating Curve= 0 ,0
Exp/Cntr=0.3,0.1

Type RM Length L Ch R = 1 ,24659.03,114.78,114.84,114.31
XS GIS Cut Line= 5
 3027465.000040813890999.9999938 3027261.000120713890759.0001477
 3026771.000116413889851.9999932 3026622.0000864 13889594.999851
    3026507.2985  13889397.15879
#Sta/Elev= 30
       0  130.19   93.74  130.76  182.54  128.31  241.74  131.02  360.57  131.69
  381.37  130.27  410.37  127.89  430.29  128.14  450.21  122.12  490.05  119.82
  503.95  116.61  509.97  119.79  549.82  128.99  589.66  128.04   607.2  129.59
   679.3  129.21  724.12   126.8  793.85  129.15  883.49  129.74 1027.91  127.43
 1062.78  129.46  1207.2  130.76 1286.88  127.94 1430.81  131.03 1559.54  127.27
 1663.59  130.74 1743.11  127.76 1762.99  129.71 1802.75  127.69 1872.33  130.31
#Mann= 5 ,-1 , 0
       0     .15       0  381.37     .07       0  430.29     .04       0
  549.82     .07       0   607.2     .15       0
#XS Ineff= 4 ,-1
       0  380.49  130.39   604.6  883.49  129.67  883.49  1207.2  129.74
  1207.2 1872.33  130.76
Permanent Ineff=
       F       F       F       F
#Block Obstruct= 2 , 0
       0    59.2  131.02               0
Bank Sta=430.29,549.82
XS Rating Curve= 0 ,0
Exp/Cntr=0.3,0.1

Type RM Length L Ch R = 1 ,24544.18,103.64,104.69,105.44
XS GIS Cut Line= 4
 3027520.999928813890994.0000058 3026865.999926513889796.0001052
 3026704.9999204 13889549.999941   3026580.69713  13889360.07134
#Sta/Elev= 30
       0  130.47  164.44  130.48  239.19  128.55  289.02  130.68  395.63  130.33
  423.56  127.65   443.5  128.09  462.13   122.5  510.64  116.43  516.07  119.51
  544.03   122.3  549.45  123.66  553.12  126.89  563.09  128.54  607.94  128.07
  622.07  130.17   677.7  130.01  747.46  126.72  812.24  129.61 1041.47  127.14
  1121.2  130.25 1245.77  129.95 1290.62  127.82  1355.4  129.99 1489.95  130.44
 1564.69   127.4 1654.39  130.04  1748.2  127.67 1827.16  127.61 1886.38  130.16
#Mann= 5 ,-1 , 0
       0     .15       0  395.63     .07       0   443.5     .04       0
  563.09     .07       0  622.07     .15       0
#XS Ineff= 2 , 0
       0  393.66  130.62  632.85       0  130.64
Permanent Ineff=
       F       F
#Block Obstruct= 2 , 0
       0   79.73  131.03               0
Bank Sta=443.5,563.09
XS Rating Curve= 0 ,0
Exp/Cntr=0.3,0.1