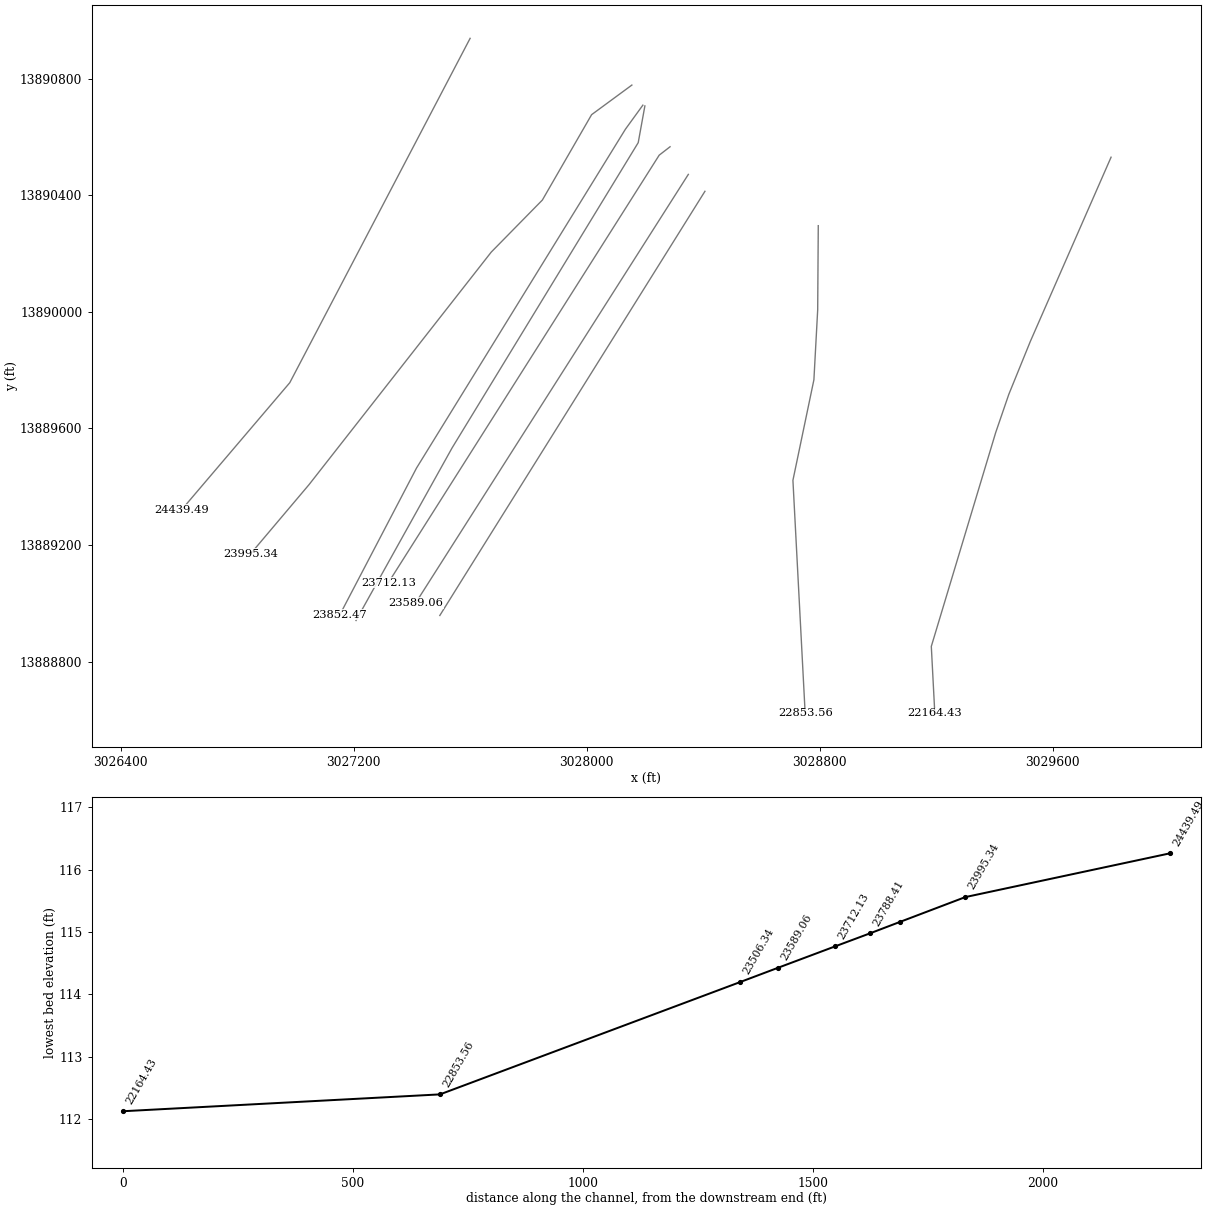
HEC-RAS study U106-00-00.prj: U106-00-00 2019 (Re-Study)

--- U106-00-00.g01 (geometry) --- (continued)

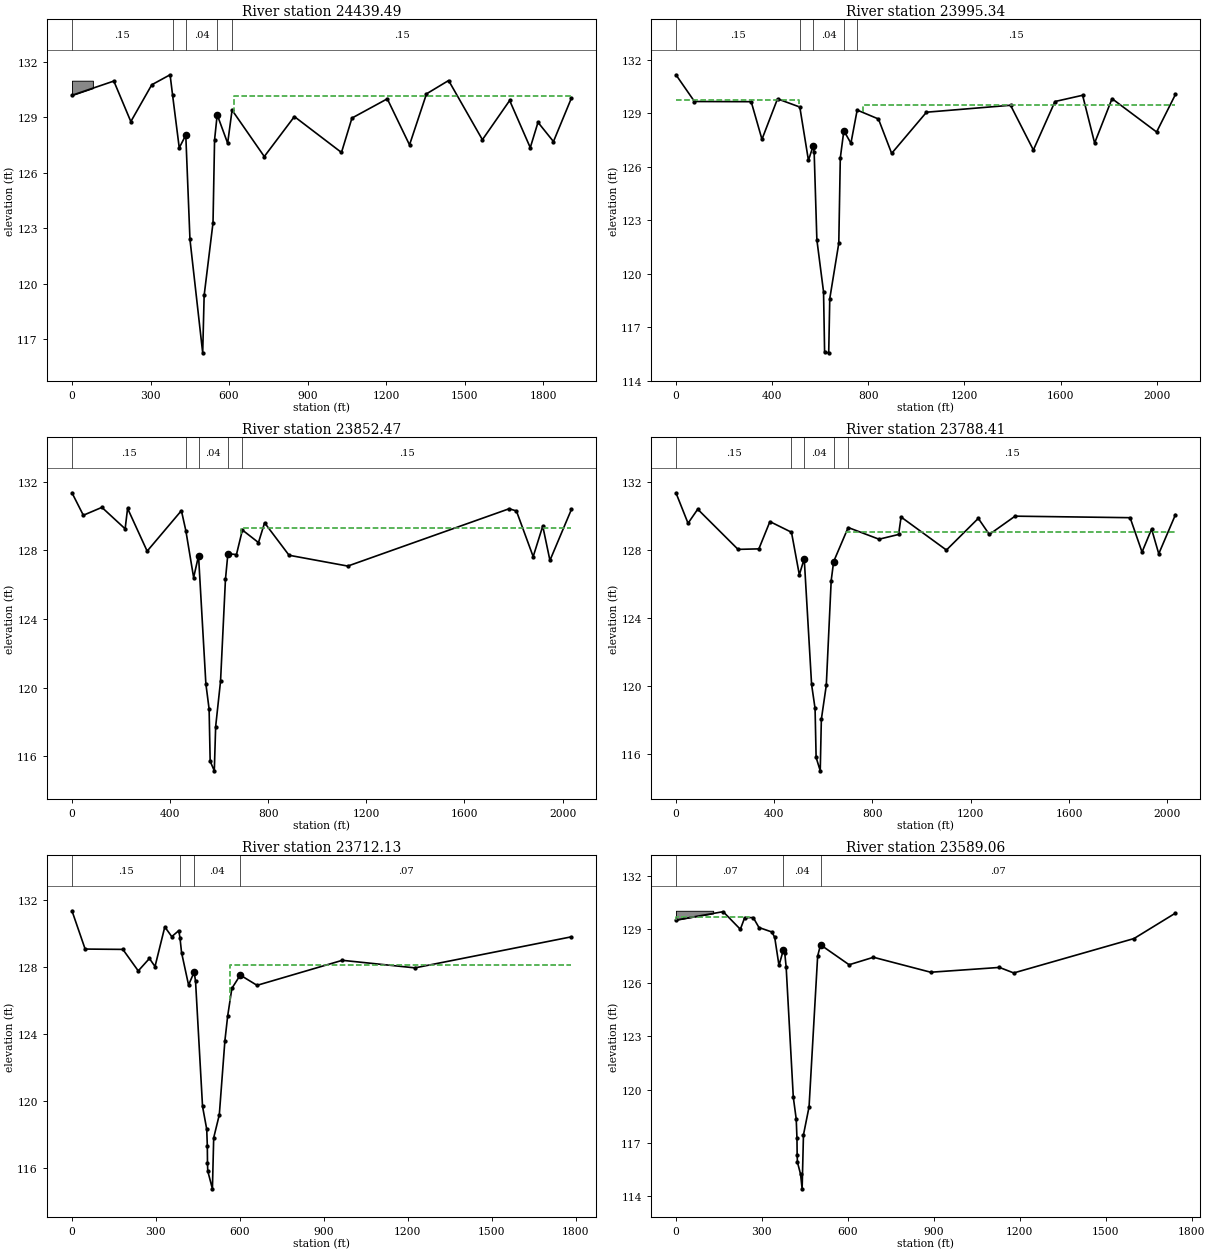
Type RM Length L Ch R = 1 ,24439.49,456.17,444.15,424.92
Node Name=Z
XS GIS Cut Line= 4
 3027600.000098913890939.0001158 3026981.000024513889756.9998551
 3026775.0001085 13889515.000011   3026609.23215  13889320.26295
#Sta/Elev= 30
       0  130.18  159.91  130.95  224.88  128.76  304.83  130.75   374.8  131.29
  384.52  130.17  409.78  127.34  434.76  128.03  450.71  122.39  499.36  116.26
  504.88  119.36  538.76  123.29   544.7  127.77   554.7  129.13  594.68  127.59
  611.52  129.38   734.6  126.87  849.54  129.03 1029.44  127.09 1069.42  128.95
 1204.35  129.99  1289.3   127.5 1354.14  130.26 1438.56  130.98 1567.66  127.78
 1671.76   129.9 1750.48  127.35    1780  128.72 1839.04  127.68 1907.92  130.04
#Mann= 5 ,-1 , 0
       0     .15       0  384.52     .07       0  434.76     .04       0
   554.7     .07       0  611.52     .15       0
#XS Ineff= 2 , 0
       0  384.79  130.13  619.66       0  130.13
Permanent Ineff=
       F       F
#Block Obstruct= 2 , 0
       0   79.96  130.97 1888.24       0  130.17
Bank Sta=434.76,554.7
XS Rating Curve= 0 ,0
Exp/Cntr=0.3,0.1

Type RM Length L Ch R = 1 ,23995.34,131.72,142.87,155.74
XS GIS Cut Line= 6
     3028155.208    13890778.601  3028016.99992113890676.9999836
  3027847.99993113890383.9999134 3027672.569179513890205.3637878
 3027046.999892513889406.9998989   3026845.99969  13889169.08129
#Sta/Elev= 30
       0  131.16   77.12  129.66  313.11  129.65  357.87  127.54  422.54  129.81
  515.32  129.35  551.22  126.36  570.86  127.17  575.01  126.82   586.3   121.9
  614.07  118.98  618.45   115.6  635.55  115.56  639.95   118.6  677.46  121.71
  683.77  126.49   698.5  128.02  727.95  127.32  753.97  129.18  842.43  128.68
  897.39  126.75 1042.29  129.06 1392.03  129.45 1486.96  126.94  1576.9  129.66
 1691.81  130.01 1741.78  127.33 1814.22  129.82 1999.65  127.95 2078.13  130.06
#Mann= 5 ,-1 , 0
       0     .15       0  515.32     .07       0  570.86     .04       0
   698.5     .07       0  753.97     .15       0
#XS Ineff= 2 , 0
       0  511.94  129.77  777.48       0  129.49
Permanent Ineff=
       F       F
#Block Obstruct= 2 , 0
       0                  1852.5       0   129.5
Bank Sta=570.86,698.5
XS Rating Curve= 0 ,0
Exp/Cntr=0.3,0.1

Type RM Length L Ch R = 1 ,23852.47,63.72,64.05,64.21
XS GIS Cut Line= 5
   3028192.93217  13890709.62705  3028133.00001713890627.0000836
 3027416.0001388 13889464.000113 3027266.000110713889177.0000308
   3027152.94878  13888960.69512
#Sta/Elev= 30
       0  131.36    46.4  130.05  122.03  130.51  216.77  129.26  226.74  130.45
  306.52  127.96  446.14  130.32  464.26  129.15     496  126.42  515.95  127.69
  545.86  120.23  559.05  118.76  563.37  115.72  580.23  115.16  585.75  117.74
   605.7  120.39  625.65  126.31  635.62  127.81  670.52  127.76  694.71  129.19
  760.28  128.46  785.21  129.61  884.94  127.72 1124.28  127.09 1782.21  130.43
 1811.69   130.3 1880.01  127.64 1919.05  129.42 1948.33  127.42 2036.17   130.4
#Mann= 5 ,-1 , 0
       0     .15       0  464.26     .07       0  515.95     .04       0
  635.62     .07       0  694.71     .15       0
#XS Ineff= 2 , 0
       0  451.12   129.5  690.47       0  129.28
Permanent Ineff=
       F       F
#Block Obstruct= 2 , 0
       0                 1782.21       0     129
Bank Sta=515.95,635.62
XS Rating Curve= 0 ,0
Exp/Cntr=0.3,0.1

Type RM Length L Ch R = 1 ,23788.41,77.07,76.28,76.31
XS GIS Cut Line= 5
   3028199.87661  13890707.02289  3028176.99992913890580.9998475
 3027537.9998948 13889532.999975 3027317.000008713889136.0001128
    3027208.3047  13888940.74198
#Sta/Elev= 30
       0  131.39   49.25  129.59   88.65  130.42  252.79  128.05  337.61  128.08
  382.52  129.69  470.36  129.06  502.27  126.55  522.23   127.5  552.17  120.08
  566.33  118.66  570.63  115.77  587.38  114.98  591.91  118.02  612.04  120.03
     632  126.21  641.98  127.33  701.09  129.34   826.6  128.65  906.43  128.93
  916.41  129.96 1101.03  128.01 1230.76  129.88 1275.66  128.93 1380.46  130.01
 1848.74  129.92 1897.34  127.89 1936.22  129.25 1965.38  127.79 2033.42   130.1
#Mann= 5 ,-1 , 0
       0     .15       0  470.36     .07       0  522.23     .04       0
  641.98     .07       0  701.09     .15       0
#XS Ineff= 2 , 0
       0  470.36  129.06  691.88       0  129.07
Permanent Ineff=
       F       F
#Block Obstruct= 2 , 0
       0                 1848.74       0     129
Bank Sta=522.23,641.98
XS Rating Curve= 0 ,0
Exp/Cntr=0.3,0.1

Type RM Length L Ch R = 1 ,23712.13,119.56,123.07,122.97
Node Name=Y
XS GIS Cut Line= 3
   3028286.24814  13890566.83191  3028249.00011313890537.9999335
 3027319.000004713889069.9999168
#Sta/Elev= 30
       0  131.33    47.1  129.05  181.93  129.03  236.86  127.75  276.81  128.49
  296.78  128.01  331.74  130.37  356.71  129.79  381.68  130.15  385.92  129.73
  391.66  128.84  416.63  126.91  436.61  127.68   441.6  127.13  466.57  119.68
  481.55  118.32  483.65  117.34  484.28  116.29  485.26  115.83  501.88  114.77
  506.46  117.81  526.49  119.18  546.47  123.59  556.45  125.07  571.43  126.71
   601.4   127.5  661.32  126.89  965.93  128.38  1225.6  127.93 1784.89  129.78
#Mann= 4 ,-1 , 0
       0     .15       0  385.92     .07       0  436.61     .04       0
   601.4     .07       0
#XS Ineff= 2 , 0
       0  344.56  128.84  564.28       0  128.13
Permanent Ineff=
       F       F
Bank Sta=436.61,601.4
XS Rating Curve= 0 ,0
Exp/Cntr=0.3,0.1

Type RM Length L Ch R = 1 ,23589.06,82.28,82.72,83.28
XS GIS Cut Line= 2
 3028348.999913213890472.00006553027413.0001447813889001.0000548
#Sta/Elev= 30
       0  129.52  164.86  129.99  224.81     129   239.8  129.65  269.77  129.66
  289.76   129.1  334.72  128.85  344.71  128.55   359.7  126.97  374.69  127.83
  379.68  127.69  384.68  126.88  409.66  119.57  419.81  118.35  422.43  117.26
  423.06  116.35  424.02  115.93  434.98  115.25  440.44  114.43  445.09  117.46
  464.61  119.03  494.59  127.49  504.58  128.13  604.49  127.01  689.42  127.43
  889.26  126.59 1129.06  126.86 1179.02  126.55 1598.66  128.48 1743.54  129.91
#Mann= 3 ,-1 , 0
       0     .07       0  374.69     .04       0  504.58     .07       0
#XS Ineff= 2 , 0
       0  254.79  129.69  504.58       0  128.13
Permanent Ineff=
       F       F
#Block Obstruct= 2 , 0
       0  129.89  130.04               0
Bank Sta=374.69,504.58
XS Rating Curve= 0 ,0
Exp/Cntr=0.3,0.1

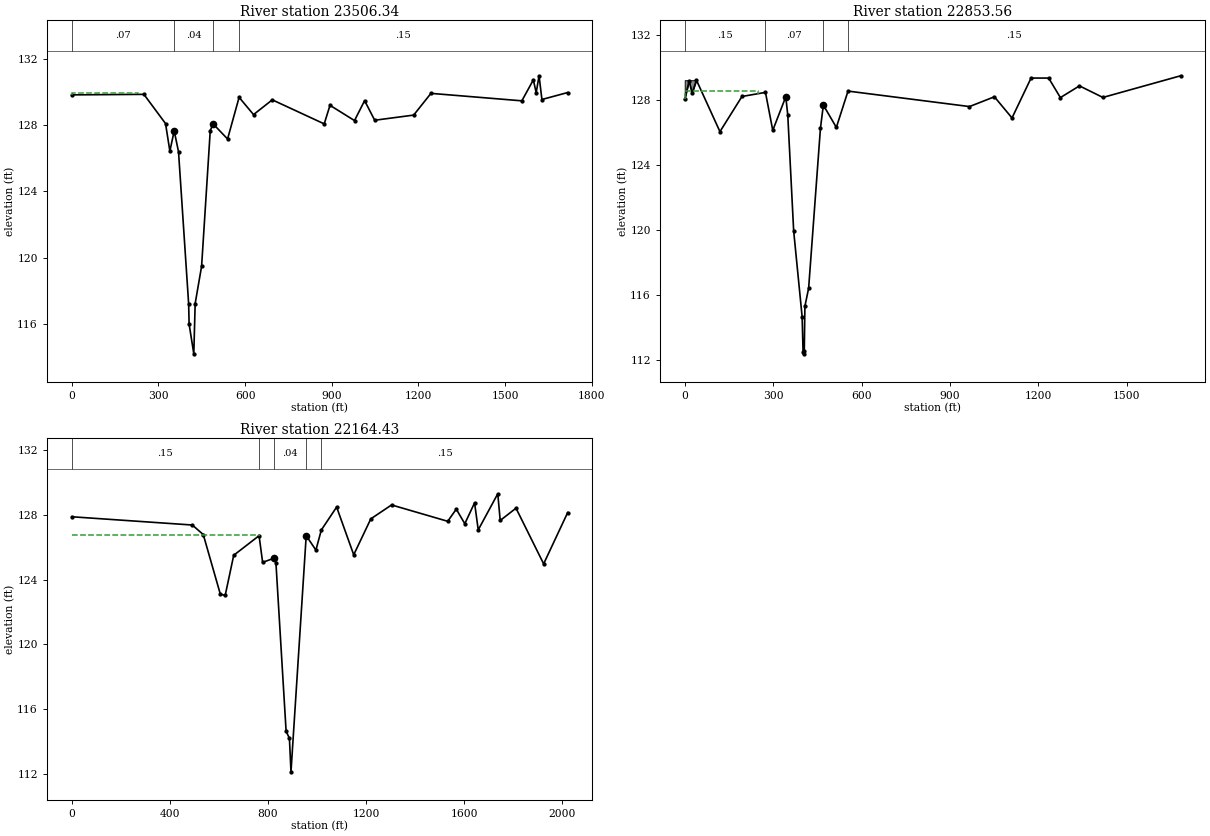
Type RM Length L Ch R = 1 ,23506.34,616.64,652.78,671.34
XS GIS Cut Line= 3
3028406.0001272713890413.99985343027572.0001548513889079.9998968
3027495.9999787813888958.0001408
#Sta/Elev= 30
       0  129.81  249.72  129.84  324.64  128.08  339.62  126.42  354.61  127.64
  369.59  126.38  404.65  117.21  406.22     116  422.51   114.2  427.21  117.23
   449.5  119.48  479.47  127.66  489.45  128.06   539.4  127.15  579.35  129.66
   629.3  128.62  694.23  129.51  874.03  128.06  894.01  129.18  978.91  128.26
 1013.87  129.46 1048.83  128.28 1183.68  128.59 1243.61   129.9 1558.26  129.45
 1598.03  130.71 1607.94  129.94 1617.85  130.96 1627.77  129.53 1716.98  129.95
#Mann= 4 ,-1 , 0
       0     .07       0  354.61     .04       0  489.45     .07       0
  579.35     .15       0
#XS Ineff= 2 , 0
       0  229.74  129.92  579.35       0  129.66
Permanent Ineff=
       F       F
Bank Sta=354.61,489.45
XS Rating Curve= 0 ,0
Exp/Cntr=0.3,0.1

Type RM Length L Ch R = 1 ,22853.56,708.33,689.13,674.14
XS GIS Cut Line= 5
3028795.0000054413890296.00008943028793.0000094513890007.0000113
3028780.0000354513889767.00016323028707.9998513613889421.9998689
3028750.0000954413888622.0001566
#Sta/Elev= 30
       0  128.03   14.95  129.15   24.91   128.4   39.86   129.2  119.59  126.04
  194.33   128.2  274.06  128.45  298.82  126.12  342.96  128.18  349.75  127.06
  369.73  119.95  398.52  114.67  401.68   112.5  403.57   112.4  405.76  112.58
  407.89  115.32  420.55  116.43  460.69  126.26   470.5  127.67  514.64   126.3
  554.18  128.53  966.38  127.58 1050.97  128.18 1110.68  126.88 1175.36  129.33
 1235.07  129.33 1274.88  128.13 1339.57  128.85 1419.18  128.14  1682.9  129.47
#Mann= 4 ,-1 , 0
       0     .15       0  274.06     .07       0   470.5      .7       0
  554.18     .15       0
#XS Ineff= 2 ,-1
       0  249.14  128.53  554.18  1682.9  128.53
Permanent Ineff=
       F       F
#Block Obstruct= 2 , 0
       0   39.86   129.2               0
Bank Sta=342.96,470.5
XS Rating Curve= 0 ,0
Exp/Cntr=0.3,0.1

Type RM Length L Ch R = 1 ,22164.43,154.25,159.03,166.6
XS GIS Cut Line= 6
3029799.9999639413890530.99994753029522.9998617813889898.9998992
3029449.0000097813889716.99993513029404.00009978 13889585.999869
 3029182.999885613888852.00002473029194.9998616113888622.0001566
#Sta/Elev= 30
       0  127.89  491.47  127.38  536.14  126.79  605.64  123.11   625.5  123.03
  660.25  125.51  763.66  126.72  778.18  125.07  822.52  125.32  832.38  125.05
   873.9  114.63   887.4  114.21  893.77  112.13  955.83  126.72   995.4  125.83
 1017.42  127.07 1079.84  128.49 1149.53  125.54 1219.21  127.76 1303.83  128.62
  1532.8  127.61 1567.64  128.36 1602.49  127.46 1642.31  128.75 1657.24  127.08
 1736.88  129.31 1746.84  127.66 1811.24  128.42 1923.95  124.98 2021.95  128.15
#Mann= 5 ,-1 , 0
       0     .15       0  763.66     .07       0  822.52     .04       0
  955.83     .07       0 1017.42     .15       0
#XS Ineff= 2 ,-1
       0  763.46  126.74 1015.19 2021.95  126.91
Permanent Ineff=
       F       F
Bank Sta=822.52,955.83
XS Rating Curve= 0 ,0
Exp/Cntr=0.5,0.3