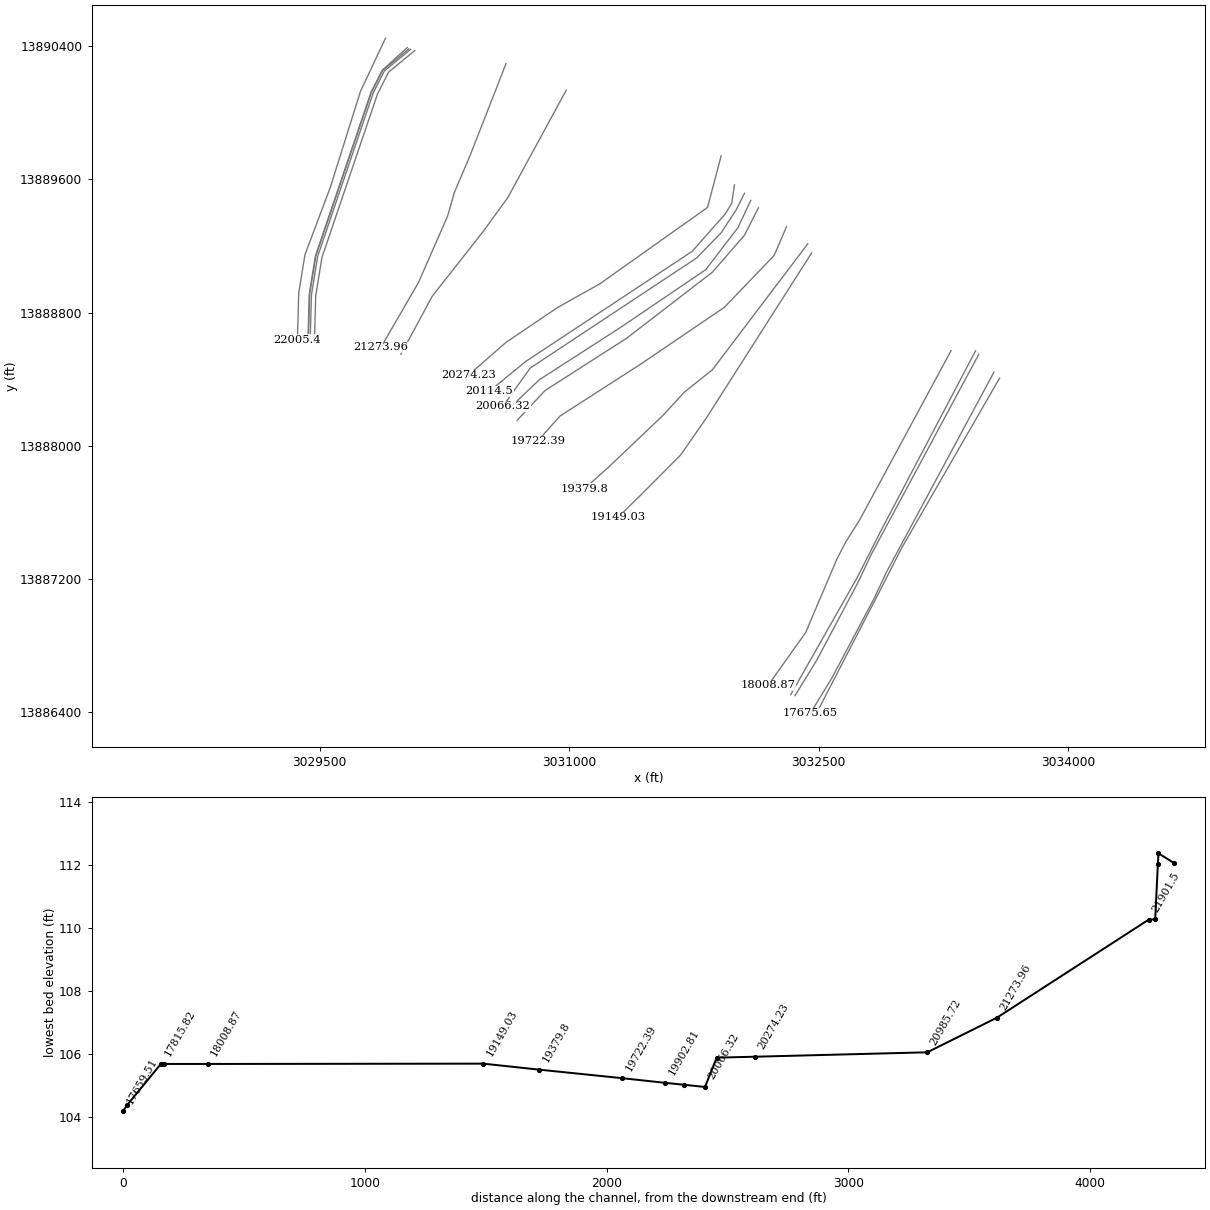
HEC-RAS study U106-00-00.prj: U106-00-00 2019 (Re-Study)

--- U106-00-00.g01 (geometry) --- (continued)

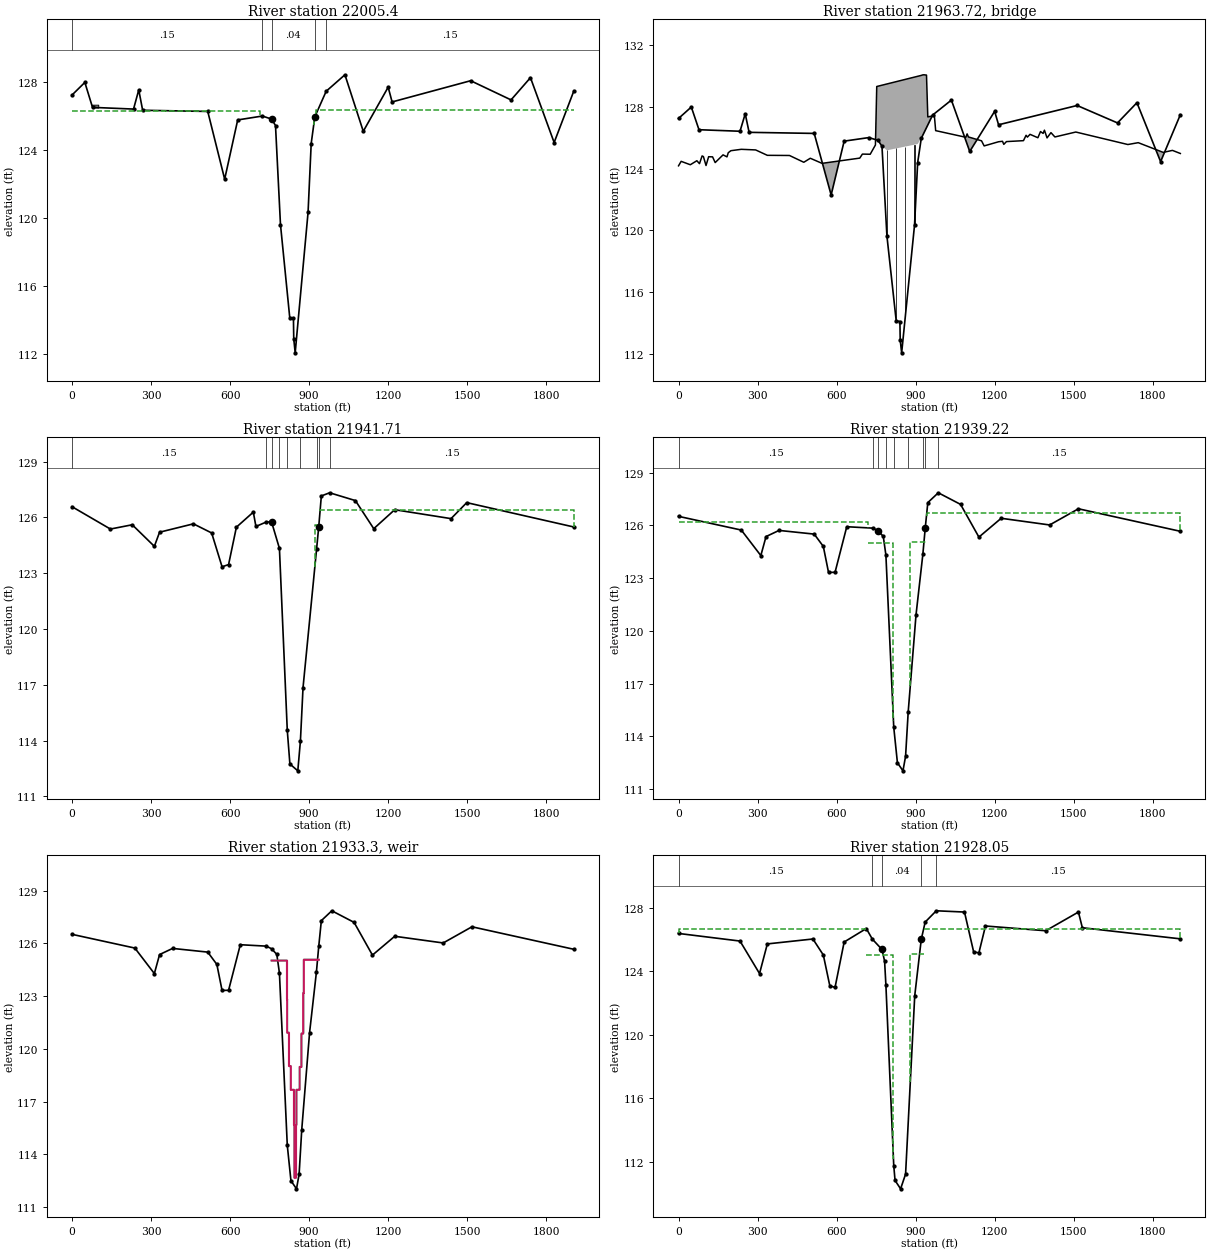
Type RM Length L Ch R = 1 ,22005.4 ,62.3,63.69,68.84
BEGIN DESCRIPTION:
Upstream Section (SUNNY RIDGE DR)
END DESCRIPTION:
Node Name=X
XS GIS Cut Line= 6
   3029896.10551  13890446.85666 3029746.132617613890128.6529832
 3029564.806864813889552.3057107 3029412.307825913889147.3225968
 3029374.896483413888917.0986478 3029366.672418513888634.7238844
#Sta/Elev= 30
       0  127.26    48.5     128    77.6  126.53  233.35  126.43  253.11  127.56
  267.92  126.36  514.99  126.29  579.24   122.3  628.67  125.79  722.33  126.02
  757.29  125.84  772.19  125.46  791.05  119.63   826.2  114.15  840.26   114.1
  841.44   112.9  846.89  112.07   895.8  120.35  907.66   124.4  921.36  125.97
  964.52  127.48 1035.69  128.45 1105.33  125.12 1199.83  127.72 1214.76  126.85
 1512.91   128.1 1666.22  126.97 1739.95  128.28 1829.79  124.46 1904.66   127.5
#Mann= 5 ,-1 , 0
       0     .15       0  722.33     .07       0  757.29     .04       0
  921.36     .07       0  964.52     .15       0
#XS Ineff= 4 ,-1
       0   712.7  126.29   712.7  774.36  124.35  917.23  926.32  125.84
  926.32 1904.66  126.36
Permanent Ineff=
       F       F       F       F
#Block Obstruct= 2 , 0
       0   99.37  126.69               0
Bank Sta=757.29,921.36
XS Rating Curve= 0 ,0
Exp/Cntr=0.5,0.3

Type RM Length L Ch R = 3 ,21963.72,,,
BEGIN DESCRIPTION:
SUNNY RIDGE DR
END DESCRIPTION:
Node Name=SUNNY RIDGE DR
Bridge Culvert--1,0,-1,-1, 0
Deck Dist Width WeirC Skew NumUp NumDn MinLoCord MaxHiCord MaxSubmerge Is_Ogee
23,39,2.6,0, 60, 60, , , 0.98, 0, 0,0,,
       0    9.94   44.72   69.56    79.5   89.44   94.41  104.34  114.28  129.19
  139.12  168.94  183.84  188.81  198.75  238.29  292.62  337.06  421.08  475.45
  500.16  544.65  687.98  697.87  727.53  747.36  752.33  921.36  926.32  931.29
  941.21  946.18  971.03     976  1090.4 1095.38 1100.35 1150.09 1160.04 1214.76
 1229.68 1234.65  1244.6 1309.26 1319.21 1324.19 1334.13 1363.98 1373.93 1383.87
 1388.85 1398.77 1413.66 1428.55 1507.95 1705.45 1744.94 1839.77 1874.71 1904.66
  124.19  124.48  124.26  124.52  124.33  124.83  124.79  124.21  124.78  124.77
   124.4   124.9  124.77  125.04  125.17  125.26  125.22  124.87  124.86  124.42
  124.68  124.35  124.69  124.95  124.94  125.54  129.33  130.05  130.08  130.09
  130.07  127.36  127.45  126.47  126.04  126.26  126.06  125.81  125.48  125.75
  125.78  125.58  125.76  125.82  126.17  126.05  126.23  126.01  126.41  126.29
   126.5     126  126.34  126.06  126.38  125.57  125.69  125.06  125.19  124.99
       0       0       0       0       0       0       0       0       0       0
       0       0       0       0       0       0       0       0       0       0
       0       0       0       0       0       0  125.06  125.65   91.19       0
       0       0       0       0       0       0       0       0       0       0
       0       0       0       0       0       0       0       0       0       0
       0       0       0       0       0       0       0       0       0       0
       0    9.94   44.72   69.56    79.5   89.44   94.41  104.34  114.28  129.19
  139.12  168.94  183.84  188.81  198.75  238.29  292.62  337.06  421.08  475.45
  500.16  544.65  687.98  697.87  727.53  747.36  752.33  921.36  926.32  931.29
  941.21  946.18  971.03     976  1090.4 1095.38 1100.35 1150.09 1160.04 1214.76
 1229.68 1234.65  1244.6 1309.26 1319.21 1324.19 1334.13 1363.98 1373.93 1383.87
 1388.85 1398.77 1413.66 1428.55 1507.95 1705.45 1744.94 1839.77 1874.71 1904.66
  124.19  124.48  124.26  124.52  124.33  124.83  124.79  124.21  124.78  124.77
   124.4   124.9  124.77  125.04  125.17  125.26  125.22  124.87  124.86  124.42
  124.68  124.35  124.69  124.95  124.94  125.54  129.33  130.05  130.08  130.09
  130.07  127.36  127.45  126.47  126.04  126.26  126.06  125.81  125.48  125.75
  125.78  125.58  125.76  125.82  126.17  126.05  126.23  126.01  126.41  126.29
   126.5     126  126.34  126.06  126.38  125.57  125.69  125.06  125.19  124.99
       0       0       0       0       0       0       0       0       0       0
       0       0       0       0       0       0       0       0       0       0
       0       0       0       0       0       0     125  125.59   91.14       0
       0       0       0       0       0       0       0       0       0       0
       0       0       0       0       0       0       0       0       0       0
       0       0       0       0       0       0       0       0       0       0
Pier Skew, UpSta & Num, DnSta & Num=  ,790.99, 2 ,790.99, 2 , 0 , 0 , 0 ,,
     1.4     1.4
  118.58  126.12
     1.4     1.4
  118.52  126.06
Pier Skew, UpSta & Num, DnSta & Num=  ,826.09, 2 ,826.09, 2 , 0 , 0 , 0 ,,
     1.4     1.4
   113.1  126.26
     1.4     1.4
  113.04   126.2
Pier Skew, UpSta & Num, DnSta & Num=  ,860.79, 2 ,860.79, 2 , 0 , 0 , 0 ,,
     1.4     1.4
  113.89   126.4
     1.4     1.4
  113.83  126.34
Pier Skew, UpSta & Num, DnSta & Num=  ,895.79, 2 ,895.79, 2 , 0 , 0 , 0 ,,
     1.4     1.4
  119.24  126.55
     1.4     1.4
  119.18  126.49
Abutment Skew #Up #Dn= , 2 , 2
  755.29  827.09
  124.97  114.08
  755.29  827.09
  124.91  114.02
Abutment Skew #Up #Dn= , 3 , 3
  857.09  924.78  927.78
   114.5  125.66  125.66
  857.09  924.78  927.78
  114.44   125.6   125.6
BR Coef=-1 , 1 , 1 ,0.9, 0 ,,,0.8,-1,1.2,0,
WSPro=,,,, 1 ,,,, 0 ,,,, 0 ,,,,-1 ,-1 ,-1 , 0 , 0 , 0 , 0 , 0
BC Design=,, 0 ,, 0 ,,,,,,
BC Use User HTab Curves=0
BC User HTab FreeFlow(D)= 0

Type RM Length L Ch R = 1 ,21941.71,2.55,2.49,2.6
BEGIN DESCRIPTION:
Downstream Section (SUNNY RIDGE DR)
END DESCRIPTION:
XS GIS Cut Line= 6
   3030027.53571  13890391.40029 3029876.438787513890254.7593583
 3029809.439905713890122.6103444  3029475.61511413889141.2799579
 3029438.203771513888911.0560089 3029429.979706613888628.6812456
#Sta/Elev= 30
       0  126.57   145.5  125.37  228.41   125.6  312.37  124.44  332.13   125.2
  460.62  125.65  529.82  125.16  569.36  123.34  594.07  123.46  623.73  125.47
  687.98  126.28  697.87  125.51  737.51  125.75  757.29  125.75  787.08  124.33
  816.87  114.55   826.8  112.74  856.83  112.37  866.76  113.98  876.69  116.85
  928.03  124.28  936.25  125.49  946.18  127.15  977.75  127.32 1075.48   126.9
 1145.12  125.39  1224.7  126.41 1438.47  125.93 1498.03  126.79 1904.66  125.48
#Mann= 9 ,-1 , 0
       0     .15       0  737.51     .07       0  757.29     .04       0
  787.08    .015       0  816.87     .04       0  866.76    .015       0
  928.03     .04       0  936.25     .07       0  977.75     .15       0
#XS Ineff= 4 ,-1
       0  687.98  126.28  687.98  782.12   123.6  921.36  941.21   125.6
  941.21 1904.66  126.38
Permanent Ineff=
       F       F       F       F
#Block Obstruct= 2 , 0
       0                 1749.93       0  126.06
Bank Sta=757.29,936.25
XS Rating Curve= 0 ,0
Exp/Cntr=0.5,0.3

Type RM Length L Ch R = 1 ,21939.22,11.42,11.17,12.75
BEGIN DESCRIPTION:
Upstream Section (WEIR DS SUNNY)
END DESCRIPTION:
Node Name=W
XS GIS Cut Line= 6
   3030036.40393   13890383.2498 3029878.843966413890254.1146745
 3029811.845084613890121.9656606 3029478.020292913889140.6352742
 3029440.608950513888910.4113252 3029432.384885513888628.0365618
#Sta/Elev= 30
       0  126.51  238.29  125.73  312.37  124.28  332.13  125.36  381.54  125.71
  514.99   125.5  549.59   124.8  569.36  123.32  594.07  123.33  638.56  125.92
  737.18  125.84  757.29  125.69  777.15  125.37  787.08  124.31  816.87  114.52
  830.82   112.5  851.87  112.04   861.8  112.87  871.72  115.39   901.5  120.92
  927.36  124.35  936.25  125.82  946.18  127.29  985.95  127.85 1070.51  127.19
 1140.14  125.33  1224.7   126.4  1408.7  126.02 1517.88  126.94 1904.66  125.66
#Mann= 9 ,-1 , 0
       0     .15       0  737.18     .07       0  757.29     .04       0
  787.08    .015       0  816.87     .04       0  871.72    .015       0
  927.36     .04       0  936.25     .07       0  985.95     .15       0
#XS Ineff= 4 ,-1
       0  717.64   126.2  717.64   815.8  125.02  879.71  941.21  125.07
  941.21 1904.66  126.71
Permanent Ineff=
       F       F       F       F
#Block Obstruct= 2 , 0
       0                 1779.88       0  126.12
Bank Sta=757.29,936.25
XS Rating Curve= 0 ,0
Exp/Cntr=0.5,0.3

Type RM Length L Ch R = 5 ,21933.3 ,,,
BEGIN DESCRIPTION:
WEIR DS SUNNY
U06_1090
END DESCRIPTION:
Node Name=WEIR DS SUNNY
IW Pilot Flow=0
#Inline Weir SE= 26
  757.29  125.02   815.8  125.02  815.81  122.82   816.3  122.82  816.31  120.92
   823.3  120.92  823.31  119.02   830.3  119.02  830.31  117.67   842.3  117.67
  842.31  115.67     844  115.67  844.01  112.67     850  112.67  850.01  115.67
   851.7  115.67  851.71  117.67   863.7  117.67  863.71  118.97   870.7  118.97
  870.71  120.87   877.8  120.87  877.81  123.17   879.7  123.17  879.71  125.07
  936.25  125.07
IW Dist,WD,Coef,Skew,MaxSub,Min_El,Is_Ogee,SpillHt,DesHd
5,2,2.6,0,0.98,, 0 ,,,0,0,

Type RM Length L Ch R = 1 ,21928.05,27.17,26.56,26.57
BEGIN DESCRIPTION:
Downstream Section (WEIR DS SUNNY)
END DESCRIPTION:
Node Name=V
XS GIS Cut Line= 6
   3030047.19098  13890380.35938 3029889.631018313890251.2242603
 3029822.632136513890119.0752464 3029488.8073449  13889137.74486
 3029451.3960024 13888907.520911 3029443.171937513888625.1461477
#Sta/Elev= 30
       0  126.39  233.35  125.91  307.43  123.86  337.06  125.73  510.05  126.04
  549.59  125.03   574.3  123.08  594.07  122.99  628.67  125.85   712.7   126.7
  735.67  126.03  772.19  125.38  782.12  124.65  787.08  123.14  816.87  111.75
  821.83  110.81  842.88  110.28   861.8  111.21  896.54  122.46  921.36  126.02
  936.25  127.11  978.34  127.82 1085.43  127.74 1120.25  125.22 1140.14  125.17
 1165.01  126.86 1393.81  126.56 1517.88  127.74 1532.76  126.75 1904.66  126.05
#Mann= 5 ,-1 , 0
       0     .15       0  735.67     .07       0  772.19     .04       0
  921.36     .07       0  978.34     .15       0
#XS Ineff= 4 ,-1
       0   712.7   126.7   712.7   815.8  125.02  879.71  931.29  125.07
  931.29 1904.66  126.69
Permanent Ineff=
       F       F       F       F
#Block Obstruct= 2 , 0
       0                 1819.81       0  126.35
Bank Sta=772.19,921.36
XS Rating Curve= 0 ,0
Exp/Cntr=0.5,0.3

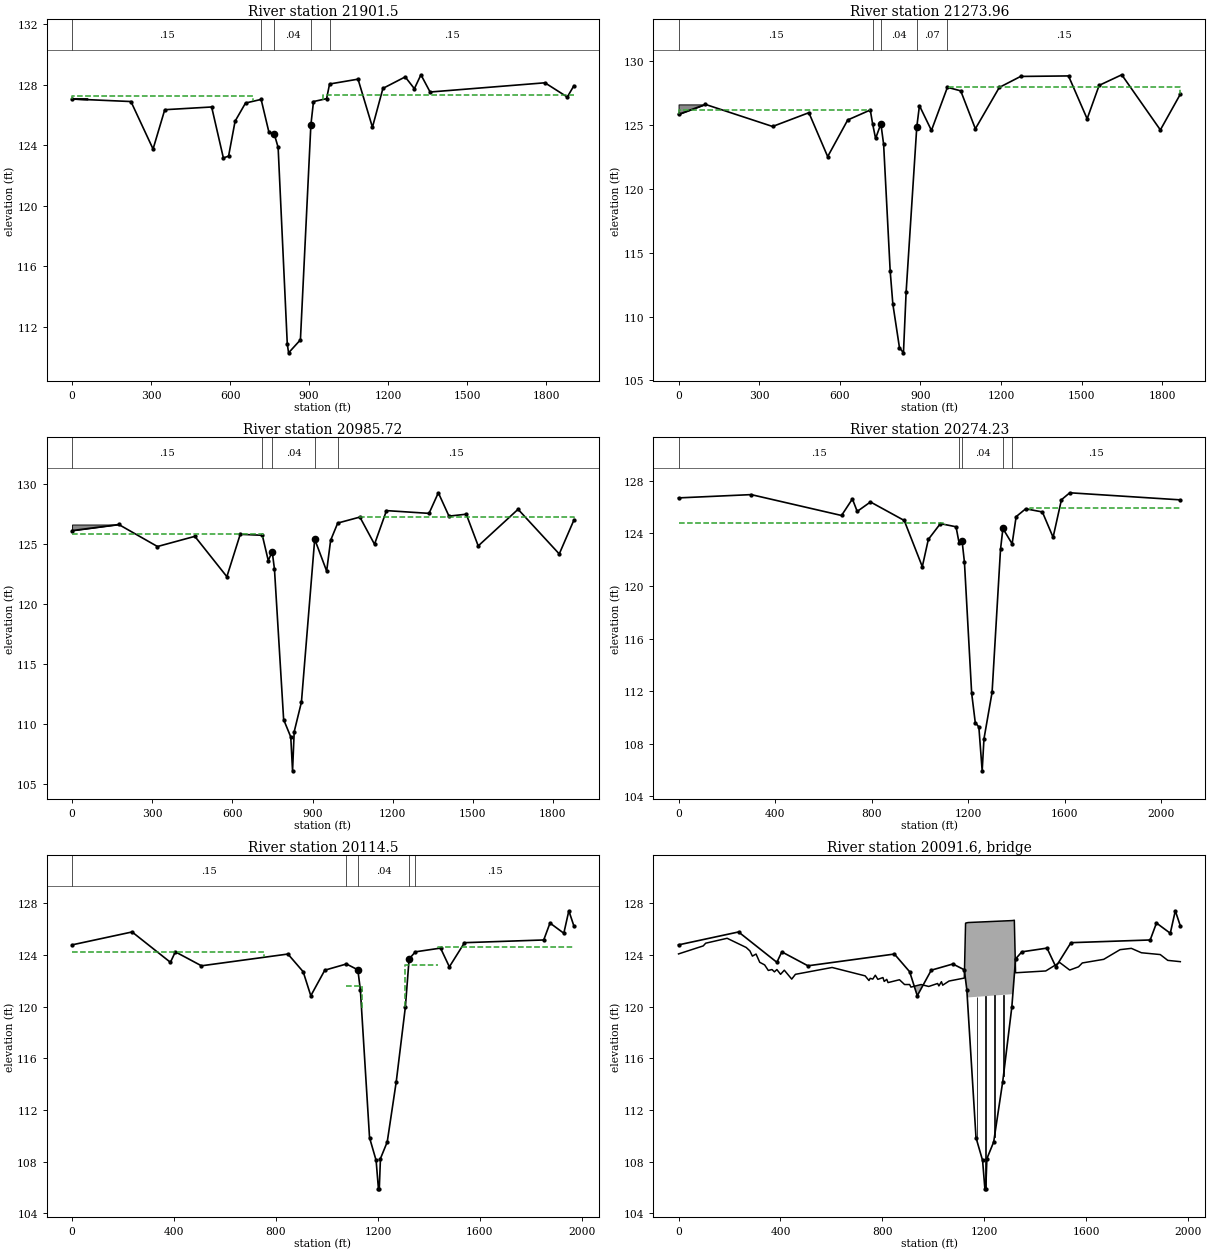
Type RM Length L Ch R = 1 ,21901.5 ,631.69,627.54,627.49
XS GIS Cut Line= 6
   3030072.84382  13890373.48505 3029915.283854113890244.3499303
 3029848.284972413890112.2009163 3029514.460180713889130.8705299
 3029477.048838213888900.6465809 3029468.824773313888618.2718176
#Sta/Elev= 30
       0  127.06  223.47  126.89  307.43  123.75  351.88  126.35  529.82  126.53
   574.3  123.16  594.07  123.28  618.79  125.59  658.33  126.79  717.64  127.03
  747.36  124.85  767.22  124.75  782.12  123.86  816.87  110.86  821.83  110.27
  866.76  111.13  906.47  125.35   916.4  126.89  966.05  127.08  977.44  128.05
 1085.43  128.37 1140.14  125.19 1179.94  127.76  1264.5  128.52 1299.31  127.74
 1324.19  128.66    1359  127.52 1794.85  128.13  1879.7  127.19 1904.66  127.93
#Mann= 5 ,-1 , 0
       0     .15       0  717.64     .07       0  767.22     .04       0
  906.47     .07       0  977.44     .15       0
#XS Ineff= 2 ,-1
       0  687.98  127.27  951.14 1904.66  127.35
Permanent Ineff=
       F       F
#Block Obstruct= 2 , 0
       0    58.2  127.12               0
Bank Sta=767.22,906.47
XS Rating Curve= 0 ,0
Exp/Cntr=0.3,0.1

Type RM Length L Ch R = 1 ,21273.96,303.2,288.24,268.74
XS GIS Cut Line= 6
3030620.9999623613890295.00009143030404.0000682813889740.9998871
3030310.99992619 13889522.999995 3030270.000008213889379.9999529
3030095.0000301213888981.00009483029869.0001540313888590.9998905
#Sta/Elev= 30
       0  125.84     100  126.62  349.99  124.89  484.99  125.97  554.98  122.53
  629.55   125.4  713.49  126.18  722.02  125.12  733.24  123.95  752.99   125.1
  763.16  123.49  787.55  113.57  797.43  110.99  822.12  107.56  836.95  107.16
  846.87  111.92  886.54  124.86  896.46  126.52  941.08  124.58 1000.56  127.96
 1050.07  127.68 1104.53  124.71 1193.65  127.95 1272.87  128.81 1451.12  128.85
 1520.47  125.49 1565.05  128.11 1649.25  128.94  1792.9  124.62  1867.2  127.42
#Mann= 5 ,-1 , 0
       0     .15       0  722.02     .07       0  752.99     .04       0
  886.54     .07       0 1000.56     .15       0
#XS Ineff= 2 ,-1
       0  713.49  126.18 1005.51  1867.2  127.97
Permanent Ineff=
       F       F
#Block Obstruct= 2 , 0
       0     100  126.62               0
Bank Sta=752.99,886.54
XS Rating Curve= 0 ,0
Exp/Cntr=0.3,0.1

Type RM Length L Ch R = 1 ,20985.72,741.76,711.5,684.94
XS GIS Cut Line= 5
3030982.9998945313890136.00008133030631.99994037 13889491.000059
3030485.9999042713889290.00013293030177.9998641213888898.9999307
3029988.9999140213888548.9999745
#Sta/Elev= 30
       0  126.13  174.84  126.64   319.7   124.8  459.57  125.65  579.46  122.28
  629.42  125.82  712.11  125.74  734.32  123.63  749.23  124.36  757.62   122.9
  791.93  110.34  818.61  108.89  825.29  106.06  831.47  109.33  858.51   111.8
  908.22  125.41  952.94  122.75  967.84  125.32  994.39  126.76 1077.32  127.26
 1132.07  124.99 1176.87   127.8 1336.15  127.57 1370.99  129.29 1410.81  127.34
 1475.51   127.5 1520.27  124.85 1669.43  127.91 1823.57  124.18 1878.26     127
#Mann= 5 ,-1 , 0
       0     .15       0  712.11     .07       0  749.23     .04       0
  908.22     .07       0  994.39     .15       0
#XS Ineff= 2 ,-1
       0  714.34  125.84 1072.34 1878.26   127.3
Permanent Ineff=
       F       F
#Block Obstruct= 2 , 0
       0  174.84  126.64               0
Bank Sta=749.23,908.22
XS Rating Curve= 0 ,0
Exp/Cntr=0.3,0.1

Type RM Length L Ch R = 1 ,20274.23,154.31,159.73,189.04
XS GIS Cut Line= 6
3031914.0000010313889740.99988713031831.9998369413889430.9998509
 3031184.000148713888972.00011283030931.9999965313888831.0000667
3030620.9999623613888621.00015863030395.0000862813888423.9998964
#Sta/Elev= 30
       0  126.71  300.93  126.96  675.26  125.37   720.2  126.63  740.18  125.68
  795.12   126.4  934.96  124.99 1009.87  121.47 1034.84  123.55 1084.79  124.75
 1149.58  124.51 1162.23  123.28 1174.46  123.46 1184.42   121.8 1214.27  111.84
  1229.2   109.6 1244.13  109.26 1257.84  105.92 1265.24  108.35 1298.92   111.9
 1333.79  122.78 1343.75  124.38  1381.9  123.21 1398.54  125.28 1438.08  125.88
 1507.21  125.64 1551.65  123.71 1586.21  126.57 1620.78   127.1 2078.72  126.56
#Mann= 5 ,-1 , 0
       0     .15       0 1162.23     .07       0 1174.46     .04       0
 1343.75     .07       0  1381.9     .15       0
#XS Ineff= 2 ,-1
       0 1104.76  124.83 1457.83 2078.72  125.91
Permanent Ineff=
       F       F
Bank Sta=1174.46,1343.75
XS Rating Curve= 0 ,0
Exp/Cntr=0.5,0.3

Type RM Length L Ch R = 1 ,20114.5 ,47.94,48.17,48.29
BEGIN DESCRIPTION:
Upstream Section (PINE FALLS ROAD)
END DESCRIPTION:
Node Name=U
XS GIS Cut Line= 6
3031994.1960348613889566.94314863031977.5438371913889456.7917941
3031939.3221288613889393.11344383031740.1683276913889167.7057581
3030739.0886369513888505.95248843030521.7855938713888328.1477259
#Sta/Elev= 30
       0  124.78  235.46  125.78  385.81  123.43  405.17  124.24  507.61  123.16
  846.79  124.07  906.65   122.7  936.57  120.84  991.44  122.82 1076.24   123.3
 1121.07  122.85    1131   121.3    1167  109.85 1192.79  108.09 1201.88  105.89
 1205.24  105.91 1209.74  108.23 1236.36  109.52 1271.85   114.2 1307.59  119.98
  1322.2  123.69 1346.69  124.24 1445.55  124.53 1480.15  123.08 1539.47  124.95
 1850.31  125.16 1874.94  126.47 1929.13  125.68 1948.83  127.42 1968.53  126.25
#Mann= 5 ,-1 , 0
       0     .15       0 1076.24     .07       0 1121.07     .04       0
  1322.2     .07       0 1346.69     .15       0
#XS Ineff= 5 ,-1
       0  752.02  124.25  752.02 1076.24   123.3 1076.24 1135.97  121.58
 1307.59 1435.67  123.25 1435.67 1968.53   124.6
Permanent Ineff=
       F       F       F       F       F
Bank Sta=1121.07,1322.2
XS Rating Curve= 0 ,0
Exp/Cntr=0.5,0.3

Type RM Length L Ch R = 3 ,20091.6 ,,,
BEGIN DESCRIPTION:
PINE FALLS ROAD
END DESCRIPTION:
Node Name=PINE FALLS ROAD
Bridge Culvert--1,0,-1,-1, 0
Deck Dist Width WeirC Skew NumUp NumDn MinLoCord MaxHiCord MaxSubmerge Is_Ogee
7,34.5,2.6,0, 60, 60, , , 0.98, 0, 0,0,,
       0   96.87  106.56  190.65  265.33   280.1  289.71  304.12  318.54  337.76
  352.17  366.59   376.2  385.81  400.32  414.87  443.99  458.54  602.38  732.07
  747.03  752.02     762  771.97  781.95   801.9  806.89  816.86  821.85  866.74
  886.69  906.65  911.63  951.54  981.47 1016.38 1021.37 1031.35 1036.33 1061.27
 1121.07 1126.03    1131 1135.97 1307.59 1312.46 1317.33  1322.2 1440.61 1494.98
 1534.53 1569.13 1583.96 1667.99 1732.09 1776.43 1815.83 1889.72 1919.28 1968.54
  124.08   124.7  124.91  125.29  124.58  124.31  123.91  124.07  123.43  123.23
   122.8  122.87  122.69  122.87   122.5  122.82  122.13   122.5  123.03  122.38
  122.02  122.19  122.13  122.43  122.11  122.25  121.95  122.11  121.86  122.08
  121.71  121.71  121.51  121.71  121.56  121.79   121.6  121.93  121.66  121.98
  122.21  126.46  126.49  126.51  126.66  126.67  126.69  122.62  122.76  123.42
  122.83  123.08  123.38  123.66  124.41  124.51  124.17  124.03  123.58  123.48
       0       0       0       0       0       0       0       0       0       0
       0       0       0       0       0       0       0       0       0       0
       0       0       0       0       0       0       0       0       0       0
       0       0       0       0       0       0       0       0       0       0
       0       0   63.28  120.71  120.96       0       0       0       0       0
       0       0       0       0       0       0       0       0       0       0
       0   96.87  106.56  190.65  265.33   280.1  289.71  304.12  318.54  337.76
  352.17  366.59   376.2  385.81  400.32  414.87  443.99  458.54  602.38  732.07
  747.03  752.02     762  771.97  781.95   801.9  806.89  816.86  821.85  866.74
  886.69  906.65  911.63  951.54  981.47 1016.38 1021.37 1031.35 1036.33 1061.27
 1121.07 1126.03    1131 1135.97 1307.59 1312.46 1317.33  1322.2 1440.61 1494.98
 1534.53 1569.13 1583.96 1667.99 1732.09 1776.43 1815.83 1889.72 1919.28 1968.54
  124.08   124.7  124.91  125.29  124.58  124.31  123.91  124.07  123.43  123.23
   122.8  122.87  122.69  122.87   122.5  122.82  122.13   122.5  123.03  122.38
  122.02  122.19  122.13  122.43  122.11  122.25  121.95  122.11  121.86  122.08
  121.71  121.71  121.51  121.71  121.56  121.79   121.6  121.93  121.66  121.98
  122.21  126.46  126.49  126.51  126.66  126.67  126.69  122.62  122.76  123.42
  122.83  123.08  123.38  123.66  124.41  124.51  124.17  124.03  123.58  123.48
       0       0       0       0       0       0       0       0       0       0
       0       0       0       0       0       0       0       0       0       0
       0       0       0       0       0       0       0       0       0       0
       0       0       0       0       0       0       0       0       0       0
       0       0   63.27  120.68  120.93       0       0       0       0       0
       0       0       0       0       0       0       0       0       0       0
Pier Skew, UpSta & Num, DnSta & Num=  ,1169.7, 2 ,1169.7, 2 , 0 , 0 , 0 ,,
     1.4     1.4
  108.79  121.74
     1.4     1.4
  108.76  121.71
Pier Skew, UpSta & Num, DnSta & Num=  ,1204.6, 2 ,1204.6, 2 , 0 , 0 , 0 ,,
     1.4     1.4
  104.89  121.77
     1.4     1.4
  104.86  121.74
Pier Skew, UpSta & Num, DnSta & Num=  ,1239.1, 2 ,1239.1, 2 , 0 , 0 , 0 ,,
     1.4     1.4
  108.49   121.8
     1.4     1.4
  108.46  121.77
Pier Skew, UpSta & Num, DnSta & Num=  ,1274.6, 2 ,1274.6, 2 , 0 , 0 , 0 ,,
     1.4     1.4
  113.13  121.83
     1.4     1.4
   113.1   121.8
Abutment Skew #Up #Dn= , 2 , 2
  1133.9    1154
  120.71  114.64
  1133.9    1154
  120.68  114.61
Abutment Skew #Up #Dn= , 2 , 2
  1269.9 1308.99
  113.68  120.96
  1269.9 1308.99
  113.65  120.93
BR Coef=-1 , 1 , 1 ,0.9, 0 ,,,0.8,-1,1.2,0,
WSPro=,,,, 1 ,,,, 0 ,,,, 0 ,,,,-1 ,-1 ,-1 , 0 , 0 , 0 , 0 , 0
BC Design=,, 0 ,, 0 ,,,,,,
BC Use User HTab Curves=0
BC User HTab FreeFlow(D)= 0

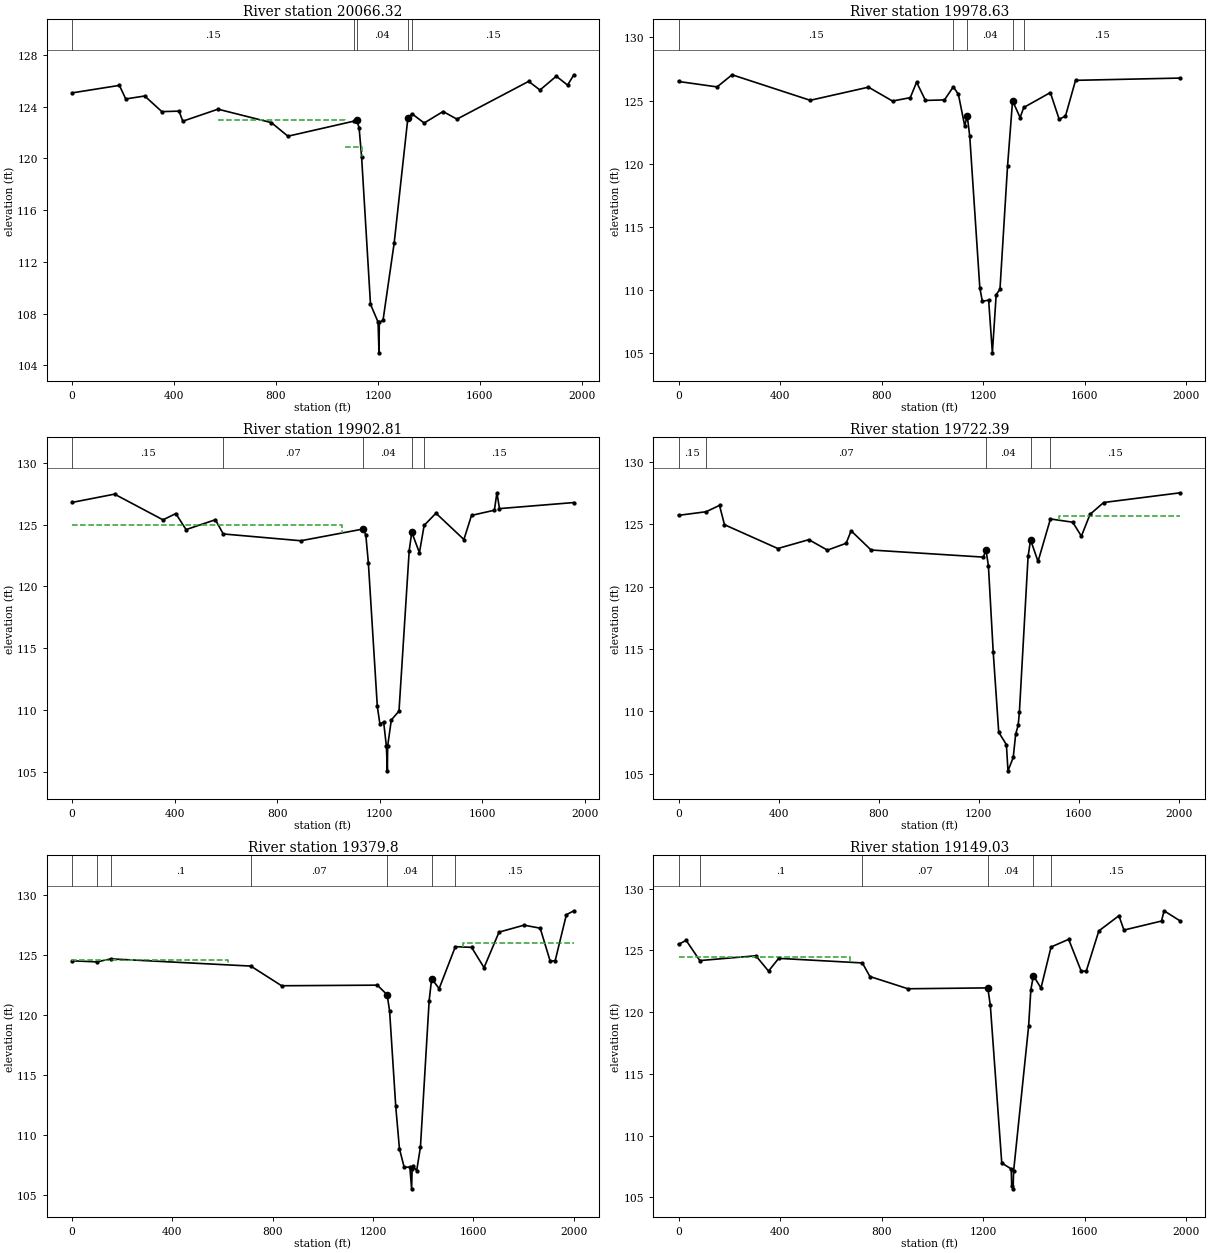
Type RM Length L Ch R = 1 ,20066.32,89.57,87.69,96.88
BEGIN DESCRIPTION:
Downstream Section (PINE FALLS ROAD)
END DESCRIPTION:
Node Name=T
XS GIS Cut Line= 6
3032054.5932237813889516.78675283032004.6116964413889417.2252722
3031914.9455371913889280.16419463031767.2361869413889128.1392362
 3030766.156496213888466.38596653030602.8599067813888237.9795992
#Sta/Elev= 30
       0  125.06  185.67  125.64  210.57  124.59   284.9  124.82  352.17  123.61
  419.72  123.65  434.28  122.87  572.45   123.8  781.95  122.76  846.79  121.71
 1104.65  122.87  1116.1  122.96 1126.03  122.38 1135.97  120.07 1170.74  108.71
 1200.44  107.34  1204.1  104.96 1205.31  107.31 1219.92  107.48 1263.76  113.47
 1317.33  123.11 1333.18  123.45 1381.29  122.73 1455.44  123.62 1509.81  123.03
  1791.2  125.95 1835.54  125.28 1899.57  126.35  1943.9  125.66 1968.53  126.46
#Mann= 5 ,-1 , 0
       0     .15       0 1104.65     .07       0  1116.1     .04       0
 1317.33     .07       0 1333.18     .15       0
#XS Ineff= 5 ,-1
       0  572.45   123.8  572.45 1071.25  122.97 1071.25 1135.97   120.9
 1305.58 1455.44   120.5 1455.44 1968.53  123.62
Permanent Ineff=
       F       F       F       F       F
Bank Sta=1116.1,1317.33
XS Rating Curve= 0 ,0
Exp/Cntr=0.5,0.3

Type RM Length L Ch R = 1 ,19978.63,74.51,75.82,74.17
XS GIS Cut Line= 6
 3032091.9999731 13889474.0000933032015.0001271113889310.0000929
3031821.9998569513889057.99994083031309.9998966913888710.9999786
3030821.9998884513888396.99995043030619.9999643613888205.0000063
#Sta/Elev= 30
       0  126.51   151.8  126.08  210.93  127.04  518.54  125.02  747.99  126.06
  842.76  124.96  912.59  125.23  937.53  126.45  972.45  125.01 1047.27  125.05
 1082.19  126.09 1102.14  125.49 1127.02     123 1136.94  123.79 1146.86  122.17
 1186.53  110.17 1196.45  109.11 1221.24   109.2 1235.97  105.03    1251  109.64
 1265.87  110.06 1295.63  119.79 1315.46  124.98 1345.22  123.65 1359.41  124.45
 1464.28  125.63 1499.01  123.52 1523.82  123.77 1563.51   126.6 1976.15  126.78
#Mann= 5 ,-1 , 0
       0     .15       0 1082.19     .07       0 1136.94     .04       0
 1315.46     .07       0 1359.41     .15       0
#XS Ineff= 2 ,-1
       0 1082.19  126.09 1464.28 1976.15  125.63
Permanent Ineff=
       F       F
Bank Sta=1136.94,1315.46
XS Rating Curve= 0 ,0
Exp/Cntr=0.3,0.1

Type RM Length L Ch R = 1 ,19902.81,177.04,180.42,177.43
XS GIS Cut Line= 6
 3032137.999881113889428.99985493032054.0000491113889263.9998569
3031861.0001070213889041.99997283031345.0001547813888645.0001106
3030856.0001485213888332.00008043030688.0001564513888153.0001104
#Sta/Elev= 30
       0   126.8  165.66  127.47  354.67  125.39  404.53   125.9  444.42   124.6
  558.83   125.4  589.45  124.25  891.81   123.7 1135.34  124.65  1145.3  124.17
 1155.25  121.92 1190.09  110.32 1200.05   108.9 1214.98  109.02 1225.53  107.08
 1229.37  105.09 1230.51   107.1 1244.85  109.21 1274.71  109.92 1314.53  122.91
 1324.49  124.39 1354.35  122.73 1372.74  124.94 1418.77  125.93 1527.74   123.8
 1557.46  125.75 1646.62  126.17 1656.53  127.58 1666.44   126.3 1956.51  126.79
#Mann= 5 ,-1 , 0
       0     .15       0  589.45     .07       0 1135.34     .04       0
 1324.49     .07       0 1372.74     .15       0
#XS Ineff= 2 ,-1
       0 1050.85     125 1418.77 1956.51  125.93
Permanent Ineff=
       F       F
Bank Sta=1135.34,1324.49
XS Rating Curve= 0 ,0
Exp/Cntr=0.3,0.1

Type RM Length L Ch R = 1 ,19722.39,315.19,342.58,349.38
XS GIS Cut Line= 6
3032306.9998711913889315.00008293032232.0000211913889142.0001009
3031932.9999630313888831.00006673031421.0000027713888484.0001045
3030945.9999685313888179.00005843030810.9999104413888028.0000323
#Sta/Elev= 30
       0  125.73  110.35  126.02  163.75  126.53   183.6  124.98  396.83  123.07
   520.8  123.78  595.18  122.94  669.86  123.49  689.81  124.49  769.62  122.95
 1218.53  122.38 1228.51  122.97 1238.49   121.7  1257.8  114.74  1279.8  108.33
 1310.37  107.34 1316.74  105.24 1337.67  106.31 1347.58  108.19  1357.5  108.89
 1362.46  109.98 1397.17  122.46 1407.09  123.76 1436.85  122.03 1486.39  125.44
 1575.45  125.18 1610.08  124.06 1644.71  125.81 1699.14  126.76 2005.58  127.54
#Mann= 5 ,-1 , 0
       0     .15       0  110.35     .07       0 1228.51     .04       0
 1407.09     .07       0 1486.39     .15       0
#XS Ineff= 2 ,-1
       0  689.81  124.49 1521.02 2005.58  125.67
Permanent Ineff=
       F       F
Bank Sta=1228.51,1407.09
XS Rating Curve= 0 ,0
Exp/Cntr=0.3,0.1

Type RM Length L Ch R = 1 ,19379.8 ,212.6,230.78,235.68
Node Name=S
XS GIS Cut Line= 6
3032434.9999432713889212.99995893031861.0001070213888456.0001605
3031694.0001129513888323.00009843031561.0000508613888179.0000584
3031240.0000366913887874.0000122 3031092.000004613887740.9999501
#Sta/Elev= 30
       0  124.52   98.22  124.43  155.18  124.68  712.86  124.08  835.61  122.44
 1217.41  122.49 1256.61  121.69 1266.42  120.33 1290.92  112.38 1305.62  108.86
 1324.55  107.31 1347.23  107.32 1354.23  105.51 1356.26  107.14 1358.67  107.42
 1374.45  107.03 1389.38  108.99  1424.2   121.2 1434.16  123.03 1464.01   122.2
 1528.68   125.7 1593.36  125.64 1643.11  123.95 1702.81  126.91 1802.32  127.49
 1866.99  127.24 1906.78   124.5 1926.68  124.52 1971.45  128.36  2001.3  128.69
#Mann= 7 ,-1 , 0
       0     .15       0   98.22     .07       0  155.18      .1       0
  712.86     .07       0 1256.61     .04       0 1434.16     .07       0
 1528.68     .15       0
#XS Ineff= 2 ,-1
       0  621.74  124.58 1558.53  2001.3  126.04
Permanent Ineff=
       F       F
Bank Sta=1256.61,1434.16
XS Rating Curve= 0 ,0
Exp/Cntr=0.3,0.1

Type RM Length L Ch R = 1 ,19149.03,1120.28,1140.16,1130.37
Node Name=R
XS GIS Cut Line= 5
3032457.9998972713889158.00006893031823.9998529413888165.0000864
3031670.0001609513887943.99987223031449.9999447813887722.9999861
3031294.99992669 13887570.999962
#Sta/Elev= 30
       0  125.48   29.95  125.81   83.78  124.17  304.52  124.56  354.44  123.32
  394.38  124.35  724.01  123.98  753.81  122.88  903.57  121.89 1218.04  121.96
 1228.02  120.56 1273.09  107.79 1310.44  107.31 1312.19  105.97 1317.85   105.7
 1319.63  107.11 1378.89  118.86 1387.64   121.8 1397.62  122.95 1427.55  121.95
  1467.3  125.27 1536.59  125.89 1586.09  123.31 1605.89  123.32 1655.39  126.57
 1734.58   127.8 1754.38  126.64 1902.41  127.37 1912.28   128.2 1976.42  127.37
#Mann= 6 ,-1 , 0
       0     .15       0   83.78      .1       0  724.01     .07       0
 1218.04     .04       0 1397.62     .07       0  1467.3     .15       0
#XS Ineff= 2 ,-1
       0  673.93   124.5 1536.59 1976.42  125.89
Permanent Ineff=
       F       F
Bank Sta=1218.04,1397.62
XS Rating Curve= 0 ,0
Exp/Cntr=0.3,0.1

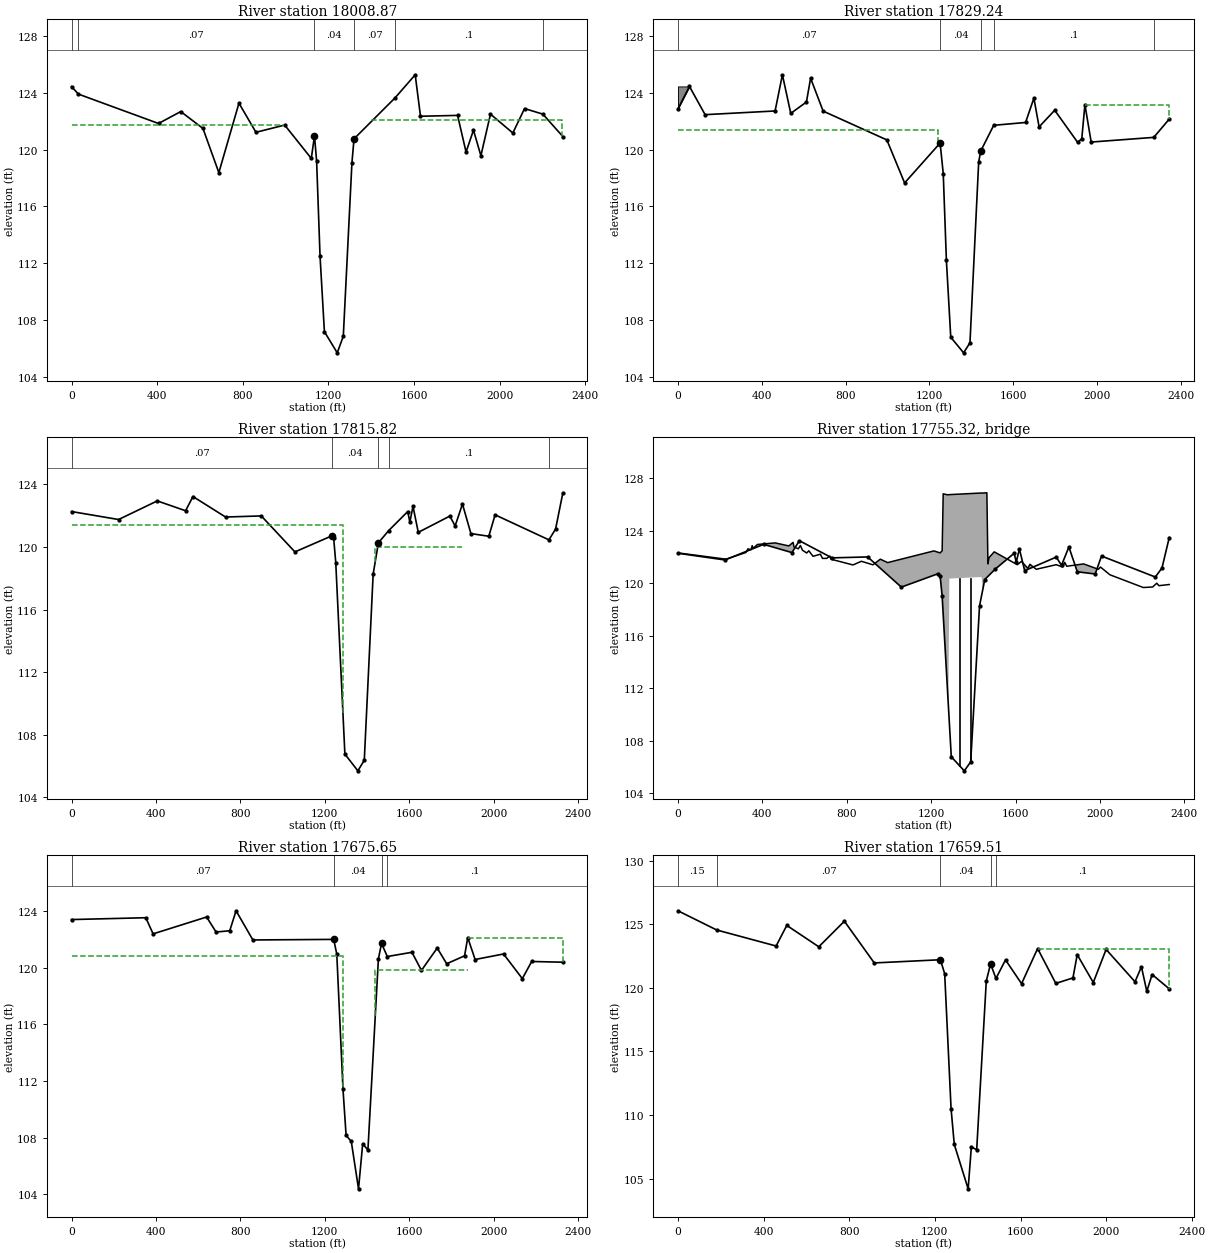
Type RM Length L Ch R = 1 ,18008.87,152.4,179.62,167.95
XS GIS Cut Line= 6
3033295.9998616913888570.99993053032746.99997544 13887554.999994
3032664.0001414413887423.99992793032609.9999213713887320.0001359
3032421.9999692713886878.0000357 3032197.000091213886562.0000115
#Sta/Elev= 30
       0  124.44   31.78  123.91  406.38  121.84  510.19  122.68  614.01  121.49
  688.16  118.38  782.09  123.27  861.57  121.22  995.79  121.73 1120.07  119.38
 1134.98  120.96 1144.93   119.2 1160.95   112.5 1181.31  107.18 1241.38  105.69
 1269.63  106.86 1309.96  119.08 1319.73  120.76 1511.78  123.65 1605.51  125.27
 1630.26  122.35 1803.52  122.41 1843.12  119.83 1877.77  121.37 1912.44  119.57
  1957.2   122.5 2061.64  121.17 2116.35  122.89 2201.89   122.5 2295.39  120.92
#Mann= 6 ,-1 , 0
       0     .15       0   31.78     .07       0 1134.98     .04       0
 1319.73     .07       0 1511.78      .1       0 2201.89     .15       0
#XS Ineff= 2 ,-1
       0  985.85  121.73 1402.73  2293.6  122.09
Permanent Ineff=
       F       F
#Block Obstruct= 2 , 0
       0                 2240.68       0  122.69
Bank Sta=1134.98,1319.73
XS Rating Curve= 0 ,0
Exp/Cntr=0.3,0.1

Type RM Length L Ch R = 1 ,17829.24,14.98,13.43,15.62
XS GIS Cut Line= 4
3033443.3532415313888570.26830473032874.3533952813887489.2684982
 3032730.3533552  13887205.268413032332.3534950313886505.2684977
#Sta/Elev= 30
       0  122.88   54.85  124.46  129.64  122.47  463.71  122.73  498.61  125.28
   538.5  122.56   613.3  123.36  633.24  125.04  693.07  122.72  997.23  120.69
    1082  117.66 1251.46  120.47 1266.39  118.32 1281.43   112.2 1302.25  106.79
 1363.66  105.69 1393.96   106.4 1435.55  119.14  1445.5  119.91 1507.23  121.72
 1659.32  121.92 1699.09  123.63 1723.94  121.61  1798.5  122.78 1907.85  120.52
 1927.74  120.78 1942.65  123.18 1972.47  120.54 2271.33  120.87 2345.27  122.16
#Mann= 5 ,-1 , 0
       0     .07       0 1251.46     .04       0  1445.5     .07       0
 1507.23      .1       0 2271.33     .15       0
#XS Ineff= 3 ,-1
       0 1240.98   121.4 1462.69 1942.65     120 1942.65 2345.27  123.18
Permanent Ineff=
       F       F       F
#Block Obstruct= 2 , 0
       0   54.85  124.46               0
Bank Sta=1251.46,1445.5
XS Rating Curve= 0 ,0
Exp/Cntr=0.5,0.3

Type RM Length L Ch R = 1 ,17815.82,143.91,140.16,150.28
BEGIN DESCRIPTION:
Upstream Section (SH 6)
END DESCRIPTION:
Node Name=Q
XS GIS Cut Line= 6
3033462.3075999513888548.77490933032894.7280264513887493.4358127
3032815.8164388513887346.52731393032739.7296487813887185.0368232
3032486.9899967813886709.19164633032358.0450446913886499.3403599
#Sta/Elev= 30
       0  122.27  223.01  121.76  406.38  122.95  540.51  122.32   575.4  123.23
  729.87  121.92   899.3  121.99 1058.76  119.69 1232.62  120.71 1242.43  120.56
 1252.24  119.01 1295.54  106.76 1357.06  105.69 1387.51  106.37 1429.51  118.27
  1454.3  120.27 1502.91  121.05 1593.45  122.27 1603.43   121.6  1618.4   122.6
 1643.34  120.94 1793.01  121.98 1817.95  121.35 1852.87  122.75 1892.78  120.86
 1977.59  120.69 2007.53  122.06 2262.53  120.46 2294.18  121.15 2328.66  123.47
#Mann= 5 ,-1 , 0
       0     .07       0 1232.62     .04       0  1454.3     .07       0
 1502.91      .1       0 2262.53     .15       0
#XS Ineff= 3 ,-1
       0 1286.57   121.4 1439.43 1852.87     120 1852.87 2328.66  122.75
Permanent Ineff=
       F       F       F
#Block Obstruct= 2 , 0
       0                 2175.95       0  120.78
Bank Sta=1232.62,1454.3
XS Rating Curve= 0 ,0
Exp/Cntr=0.5,0.3

Type RM Length L Ch R = 3 ,17755.32,,,
BEGIN DESCRIPTION:
SH 6
END DESCRIPTION:
Node Name=SH 6
Bridge Culvert--1,0,-1,-1, 0
Deck Dist Width WeirC Skew NumUp NumDn MinLoCord MaxHiCord MaxSubmerge Is_Ogee
16.5,115,2.6,0, 60, 60, , , 0.98, 0, 0,0,,
       0  227.97  322.13  332.04  346.91  351.86  356.82  376.64  460.89  525.56
   545.5  550.48  570.41  580.38  590.34  610.28  620.24  640.18  675.06  685.02
  704.96  719.91  724.89  829.53   869.4  924.21   959.1  993.98    1213 1242.43
 1252.24 1257.14 1276.76 1281.66 1286.57 1434.47 1439.43 1444.39 1464.22 1469.18
 1474.14 1498.93 1608.42 1628.37 1658.31 1668.28 1698.22 1793.01 1822.94 1832.92
 1842.89 1922.72 1992.56 2002.54 2047.44 2205.51 2249.84 2269.55  2279.4 2328.66
   122.3  121.82  122.33  122.61  122.54  122.85  122.65  122.94  123.06  122.83
   123.1  122.74  122.61  122.86   122.5  122.29  122.46  122.04   122.2  121.88
  121.88  122.06  121.82  121.38  121.66  121.39  121.82  121.56  122.45   122.3
  122.46   126.8  126.73  126.73  126.74  126.86  126.86  126.86  126.88  121.46
  121.93  122.38   121.4  121.65  121.12  121.43  121.05   121.4  121.22  121.58
  121.28  121.46  121.05  121.22  120.63  119.66   119.7  119.99   119.8  119.89
       0       0       0       0       0       0       0       0       0       0
       0       0       0       0       0       0       0       0       0       0
       0       0       0       0       0       0       0       0       0       0
       0       0       0   57.87  120.34  120.46  120.46       0       0       0
       0       0       0       0       0       0       0       0       0       0
       0       0       0       0       0       0       0       0       0       0
       0  227.97  322.13  332.04  346.91  351.86  356.82  376.64  460.89  525.56
   545.5  550.48  570.41  580.38  590.34  610.28  620.24  640.18  675.06  685.02
  704.96  719.91  724.89  829.53   869.4  924.21   959.1  993.98    1213 1242.43
 1252.24 1257.14 1276.76 1281.66 1286.57 1434.47 1439.43 1444.39 1464.22 1469.18
 1474.14 1498.93 1608.42 1628.37 1658.31 1668.28 1698.22 1793.01 1822.94 1832.92
 1842.89 1922.72 1992.56 2002.54 2047.44 2205.51 2249.84 2269.55  2279.4 2328.66
   122.3  121.82  122.33  122.61  122.54  122.85  122.65  122.94  123.06  122.83
   123.1  122.74  122.61  122.86   122.5  122.29  122.46  122.04   122.2  121.88
  121.88  122.06  121.82  121.38  121.66  121.39  121.82  121.56  122.45   122.3
  122.46   126.8  126.73  126.73  126.74  126.86  126.86  126.86  126.88  121.46
  121.93  122.38   121.4  121.65  121.12  121.43  121.05   121.4  121.22  121.58
  121.28  121.46  121.05  121.22  120.63  119.66   119.7  119.99   119.8  119.89
       0       0       0       0       0       0       0       0       0       0
       0       0       0       0       0       0       0       0       0       0
       0       0       0       0       0       0       0       0       0       0
       0       0       0   57.82  120.24  120.36  120.36       0       0       0
       0       0       0       0       0       0       0       0       0       0
       0       0       0       0       0       0       0       0       0       0
Pier Skew, UpSta & Num, DnSta & Num=  ,1334.94, 2 ,1334.94, 2 , 0 , 0 , 0 ,,
     1.4     1.4
  105.18  121.38
     1.4     1.4
  105.08  121.28
Pier Skew, UpSta & Num, DnSta & Num=  ,1386.94, 2 ,1386.94, 2 , 0 , 0 , 0 ,,
     1.4     1.4
  104.69  121.42
     1.4     1.4
  104.59  121.32
Abutment Skew #Up #Dn= , 2 , 2
 1285.55 1318.47
  120.34  106.75
 1285.55 1318.47
  120.24  106.65
Abutment Skew #Up #Dn= , 2 , 2
 1400.33 1442.01
  107.19  120.46
 1400.33 1442.01
  107.09  120.36
BR Coef=-1 , 1 , 1 ,0.9, 0 ,,,0.8,-1,1.2,0,
WSPro=,,,, 1 ,,,, 0 ,,,, 0 ,,,,-1 ,-1 ,-1 , 0 , 0 , 0 , 0 , 0
BC Design=,, 0 ,, 0 ,,,,,,
BC Use User HTab Curves=0
BC User HTab FreeFlow(D)= 0

Type RM Length L Ch R = 1 ,17675.65,15.34,16.15,13.88
BEGIN DESCRIPTION:
Downstream Section (SH 6)
END DESCRIPTION:
Node Name=P
XS GIS Cut Line= 6
3033553.7066953613888442.06252433032986.1271218713887386.7234277
3032907.2155342713887239.8149289 3032831.128744213887078.3244382
3032578.3890921913886602.47926133032449.4441401113886392.6279749
#Sta/Elev= 30
       0  123.39  351.86  123.52  386.56  122.38  640.18  123.57  685.02  122.51
   749.8   122.6   779.7  124.01  859.43  121.95 1242.43  121.99 1257.14  120.95
 1286.57  111.41 1301.28  108.15 1325.81  107.73 1360.14  104.38 1379.92  107.56
 1404.71  107.12  1454.3   120.6 1469.18  121.71 1496.46  120.78 1613.41  121.08
 1658.31   119.8 1733.14  121.38 1778.04  120.27 1862.85  120.83 1877.82  122.12
 1912.74  120.57 2047.44  120.96 2136.55  119.22 2180.88  120.43 2328.66  120.38
#Mann= 4 ,-1 , 0
       0     .07       0 1242.43     .04       0 1469.18     .07       0
 1496.46      .1       0
#XS Ineff= 3 ,-1
       0 1286.57   120.8 1439.43 1877.82   119.8 1877.82 2328.66  122.12
Permanent Ineff=
       F       F       F
#Block Obstruct= 2 , 0
       0                 2047.44       0  120.96
Bank Sta=1242.43,1469.18
XS Rating Curve= 0 ,0
Exp/Cntr=0.5,0.3

Type RM Length L Ch R = 1 ,17659.51,606.7,560.5,492.51
XS GIS Cut Line= 4
3033587.7112205313888406.31587673033000.0247318613887387.5971136
3032855.0246937713887103.59702543032487.13500962 13886393.392081
#Sta/Elev= 30
       0  126.05  180.96  124.54  458.47  123.28  508.31   124.9  657.81  123.22
  777.41  125.23  916.94  121.95  1225.9   122.2 1245.83   121.1 1275.73  110.48
 1290.68  107.68 1355.45  104.19 1370.39  107.49 1395.31  107.26 1440.15  120.52
 1460.08  121.88 1485.34  120.73 1529.95  122.19 1604.93  120.32 1679.92  123.08
  1764.9  120.34 1844.88  120.77 1864.88   122.6 1939.86  120.41 1999.85  123.01
 2134.82  120.47 2164.81  121.65 2189.81  119.72  2214.8  121.04 2294.79  119.91
#Mann= 5 ,-1 , 0
       0     .15       0  180.96     .07       0  1225.9     .04       0
 1460.08     .07       0 1485.34      .1       0
#XS Ineff= 3 ,-1
       0 1243.09   120.8  1474.2 1679.92   119.8 1679.92 2294.79  123.08
Permanent Ineff=
       F       F       F
#Block Obstruct= 2 , 0
       0                 2029.84       0  122.86
Bank Sta=1225.9,1460.08
XS Rating Curve= 0 ,0
Exp/Cntr=0.3,0.1