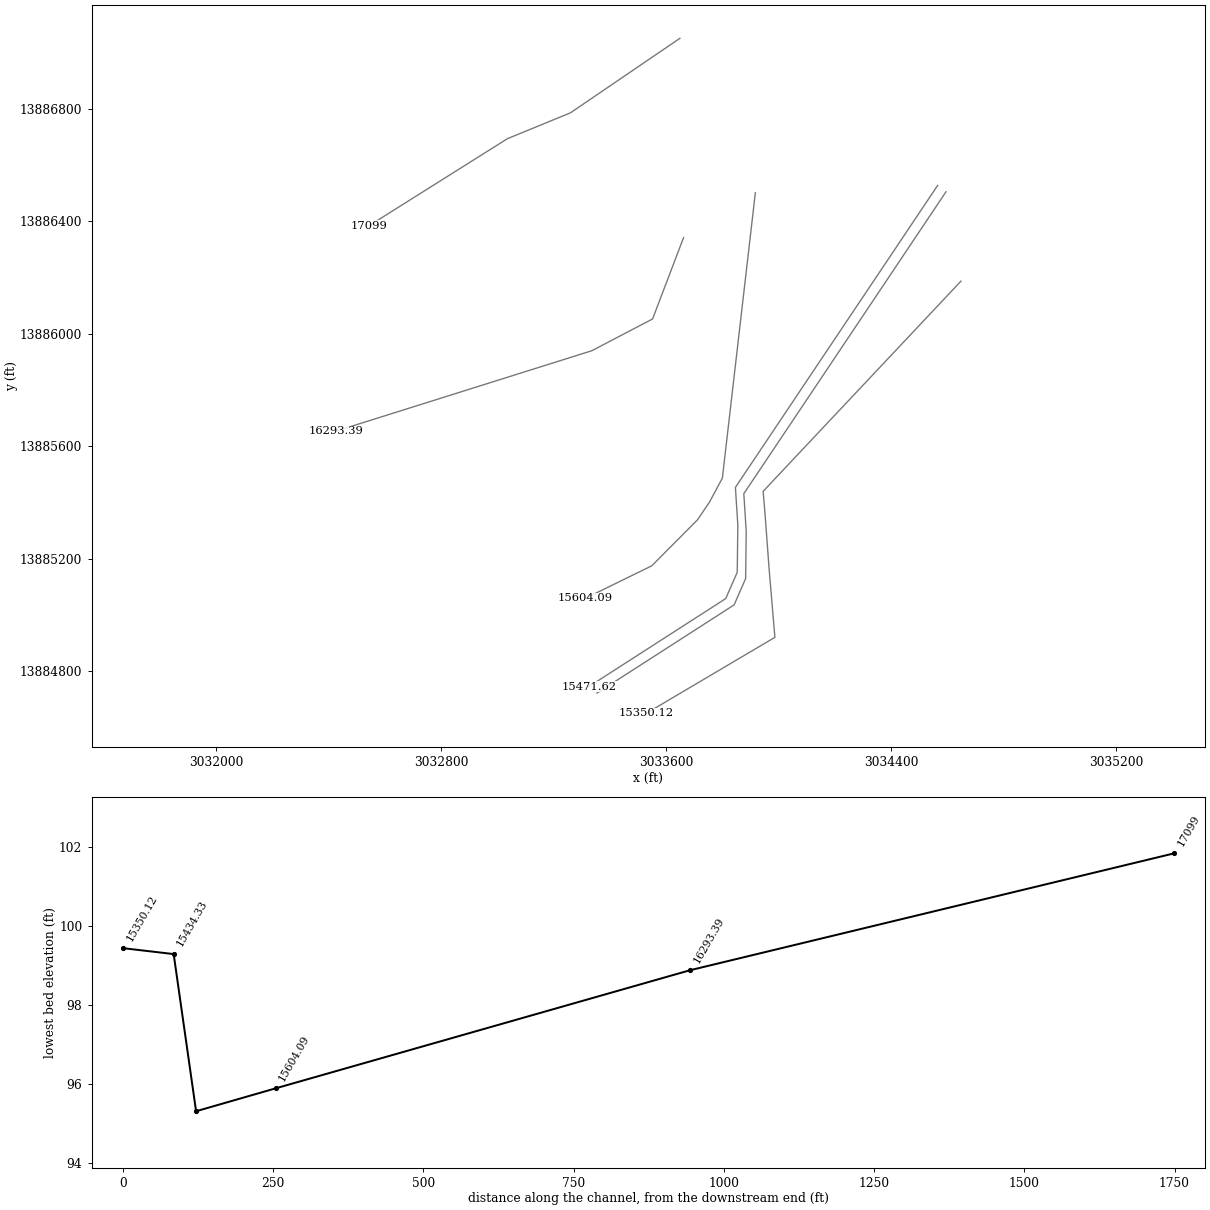
HEC-RAS study U106-00-00.prj: U106-00-00 2019 (Re-Study)

--- U106-00-00.g01 (geometry) --- (continued)

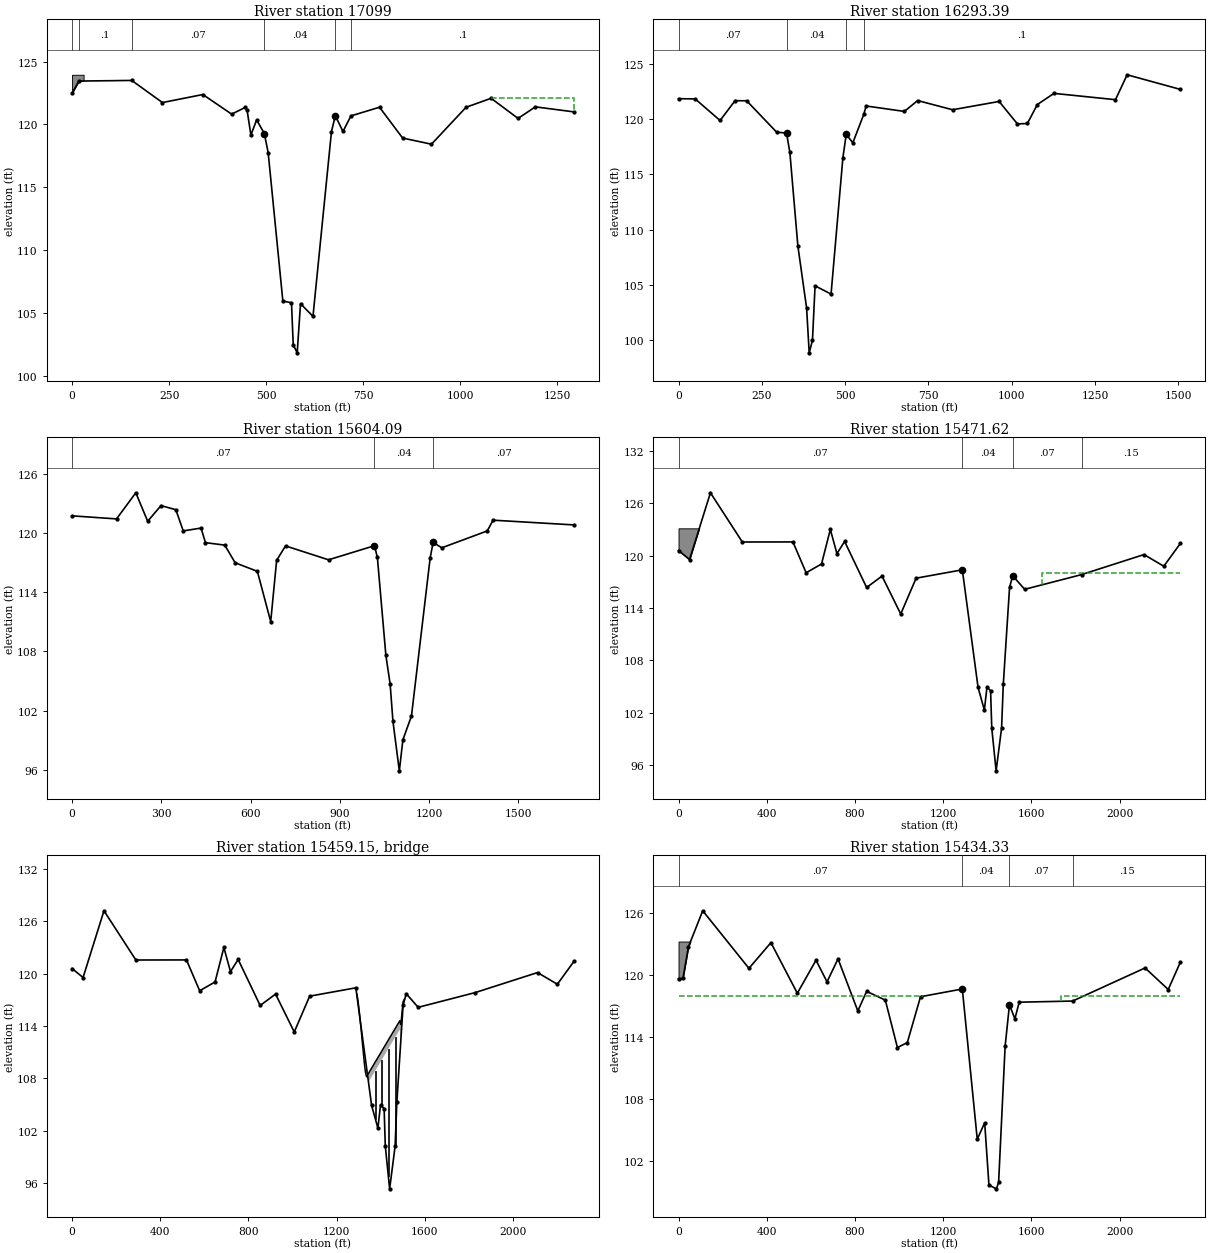
Type RM Length L Ch R = 1 ,17099   ,792,805.61,806.4
XS GIS Cut Line= 4
3033649.0001399413887050.00001983033259.9999336913886784.9998936
3033036.0000536113886693.00007763032545.0000513613886384.0000394
#Sta/Elev= 30
       0  122.48   17.49  123.45  153.76   123.5  232.87  121.74  336.91  122.38
  411.23  120.82  445.91  121.35  450.87  121.16  460.78  119.16  475.63  120.36
   495.4  119.28  505.28  117.76  543.14  105.96  565.39  105.82  569.84  102.49
  580.09  101.84  588.65  105.75  620.76  104.74  668.37  119.42  678.25   120.7
  698.02  119.44  718.56  120.68  792.18  121.37  851.68  118.92  926.06  118.43
 1015.31  121.37 1079.77  122.08 1149.19  120.48 1193.81   121.4 1292.98     121
#Mann= 6 ,-1 , 0
       0     .07       0   17.49      .1       0  153.76     .07       0
   495.4     .04       0  678.25     .07       0  718.56      .1       0
#XS Ineff= 3 ,-1
       0  336.91  122.38  792.18 1079.77  121.37 1079.77 1292.98  122.08
Permanent Ineff=
       F       F       F
#Block Obstruct= 2 , 0
       0   29.73  123.95 1114.48       0  121.56
Bank Sta=495.4,678.25
XS Rating Curve= 0 ,0
Exp/Cntr=0.3,0.1

Type RM Length L Ch R = 1 ,16293.39,509.34,689.3,715.92
XS GIS Cut Line= 4
3033662.0001139513886341.00012543033552.0000058613886052.0000473
3033336.0001097813885938.99994523032426.99995928 13885652.999861
#Sta/Elev= 30
       0  121.84   49.88  121.82  124.69  119.87  169.58  121.66  204.49  121.65
  294.26  118.82  324.15  118.73   334.1  116.99  358.07  108.55  384.36  102.93
  392.14   98.88  401.95  100.02  409.73  104.93  457.73  104.19   493.3  116.52
  503.25  118.61  523.15  117.86  556.14  120.44  562.98  121.18  677.73  120.69
  717.64  121.67  822.42  120.84  962.11  121.59 1016.99  119.56 1046.93   119.6
 1076.86  121.31 1126.75  122.32 1311.35  121.75 1346.28     124 1505.93  122.68
#Mann= 4 ,-1 , 0
       0     .07       0  324.15     .04       0  503.25     .07       0
  556.14      .1       0
#XS Ineff= 2 , 0
       0  204.49  121.65  962.11       0  121.59
Permanent Ineff=
       F       F
Bank Sta=324.15,503.25
XS Rating Curve= 0 ,0
Exp/Cntr=0.3,0.1

Type RM Length L Ch R = 1 ,15604.09,146.36,132.47,174
XS GIS Cut Line= 6
3033917.2249971913886500.78786363033799.9998379513885485.9998669
3033754.9999279413885402.00003493033712.0000139513885338.0001629
3033549.0000118613885174.00016293033314.0001537813885059.0000648
#Sta/Elev= 30
       0  121.76  149.49  121.45  214.27   124.1  254.14  121.21  298.99   122.8
  348.82  122.38  373.73  120.23  433.53  120.52  448.48  119.04  513.26  118.79
  548.14     117  622.89  116.13  667.74  111.03  687.67  117.25  717.57  118.71
  862.08   117.3 1016.55  118.73  1026.3  117.54 1054.89   107.6 1069.18   104.7
 1078.71   100.9  1100.1   95.89 1112.11   99.04 1140.92  101.46 1203.77   117.5
 1213.61  119.06 1243.13  118.52 1395.64  120.23 1415.32  121.32 1686.79  120.84
#Mann= 3 ,-1 , 0
       0     .07       0 1016.55     .04       0 1213.61     .07       0
#XS Ineff= 1 ,-1
       0  692.65  117.36
Permanent Ineff=
       F
Bank Sta=1016.55,1213.61
XS Rating Curve= 0 ,0
Exp/Cntr=0.4,0.2

Type RM Length L Ch R = 1 ,15471.62,37.8,37.29,32.21
BEGIN DESCRIPTION:
Upstream Section (12" PIPELINE)
END DESCRIPTION:
XS GIS Cut Line= 6
3034564.8601848613886526.62114533033846.4013199513885453.0452084
3033854.9360797713885318.31516293033852.8461889513885151.1320983
3033811.8521764413885057.43149833033324.9525596913884744.0246449
#Sta/Elev= 30
       0  120.59   49.88  119.56  144.64  127.22  289.28  121.57  518.72  121.58
  578.57  118.04  648.39  119.05   688.3  123.01  718.22  120.24  753.13  121.63
  852.89  116.35  922.71  117.66  1007.5  113.31 1077.33  117.42 1286.81  118.38
  1358.2  104.88 1386.77  102.28 1398.63  104.93 1414.99   104.5 1420.31  100.21
 1440.02   95.31 1464.83  100.21 1472.55  105.22 1501.02  116.38 1515.31   117.7
 1569.41  116.14 1827.67  117.83 2110.59  120.13 2200.44  118.79 2275.32   121.4
#Mann= 4 ,-1 , 0
       0     .07       0 1286.81     .04       0 1515.31     .07       0
 1827.67     .15       0
#XS Ineff= 2 ,-1
       0 1077.33  117.42 1647.57 2275.32  117.96
Permanent Ineff=
       F       F
#Block Obstruct= 2 , 0
       0   94.77  123.14 2260.34       0  121.58
Bank Sta=1286.81,1515.31
XS Rating Curve= 0 ,0
Exp/Cntr=0.4,0.2

Type RM Length L Ch R = 3 ,15459.15,,,
BEGIN DESCRIPTION:
12" PIPELINE
END DESCRIPTION:
Node Name=12" PIPELINE
Bridge Culvert--1,0,-1,-1, 0
Deck Dist Width WeirC Skew NumUp NumDn MinLoCord MaxHiCord MaxSubmerge Is_Ogee
12,1,2.6,0, 45, 45, , , 0.98, 0, 0,0,,
  1291.8 1296.62 1301.44 1306.26 1311.08 1315.91 1320.73 1325.55 1330.37 1335.19
 1340.01 1344.83 1349.66 1354.48  1359.3 1364.12 1368.94 1373.76 1378.58 1383.41
 1388.23 1393.05 1397.87 1402.69 1407.51 1412.33 1417.16 1421.98  1426.8 1431.72
 1436.63 1441.55 1446.47 1451.39  1456.3 1461.22 1466.14 1471.06 1475.97 1480.89
 1485.81 1490.73 1495.64 1500.56 1505.48
  117.64  116.87  115.84  114.67  113.55  112.17  110.95  109.65  108.68  108.18
  108.39  108.59   108.8     109  109.21  109.41  109.62  109.82  110.03  110.23
  110.44  110.64  110.85  111.05  111.26  111.46  111.67  111.87  112.08  112.29
   112.5  112.71  112.92  113.13  113.33  113.54  113.75  113.96  114.17  114.38
  114.59  114.17  115.42  116.73  117.02
       0       0       0       0       0       0       0       0       0  107.18
  107.39  107.59   107.8     108  108.21  108.41  108.62  108.82  109.03  109.23
  109.44  109.64  109.85  110.05  110.26  110.46  110.67  110.87  111.08  111.29
   111.5  111.71  111.92  112.13  112.33  112.54  112.75  112.96  113.17  113.38
  113.59       0       0       0       0
  1291.8 1296.62 1301.44 1306.26 1311.08 1315.91 1320.73 1325.55 1330.37 1335.19
 1340.01 1344.83 1349.66 1354.48  1359.3 1364.12 1368.94 1373.76 1378.58 1383.41
 1388.23 1393.05 1397.87 1402.69 1407.51 1412.33 1417.16 1421.98  1426.8 1431.72
 1436.63 1441.55 1446.47 1451.39  1456.3 1461.22 1466.14 1471.06 1475.97 1480.89
 1485.81 1490.73 1495.64 1500.56 1505.48
  117.64  116.87  115.84  114.67  113.55  112.17  110.95  109.65  108.68  108.18
  108.39  108.59   108.8     109  109.21  109.41  109.62  109.82  110.03  110.23
  110.44  110.64  110.85  111.05  111.26  111.46  111.67  111.87  112.08  112.29
   112.5  112.71  112.92  113.13  113.33  113.54  113.75  113.96  114.17  114.38
  114.59  114.17  115.42  116.73  117.02
       0       0       0       0       0       0       0       0       0  107.18
  107.39  107.59   107.8     108  108.21  108.41  108.62  108.82  109.03  109.23
  109.44  109.64  109.85  110.05  110.26  110.46  110.67  110.87  111.08  111.29
   111.5  111.71  111.92  112.13  112.33  112.54  112.75  112.96  113.17  113.38
  113.59       0       0       0       0
Pier Skew, UpSta & Num, DnSta & Num=  ,1343, 2 ,1343, 2 , 0 , 0 , 0 ,,
       4       4
      95   107.9
       4       4
      95   107.9
Pier Skew, UpSta & Num, DnSta & Num=  ,1375, 2 ,1375, 2 , 0 , 0 , 0 ,,
       4       4
      95   109.2
       4       4
      95   109.2
Pier Skew, UpSta & Num, DnSta & Num=  ,1405, 2 ,1405, 2 , 0 , 0 , 0 ,,
       4       4
      95   110.5
       4       4
      95   110.5
Pier Skew, UpSta & Num, DnSta & Num=  ,1434, 2 ,1434, 2 , 0 , 0 , 0 ,,
       4       4
      95   111.8
       4       4
      95   111.8
Pier Skew, UpSta & Num, DnSta & Num=  ,1465, 2 ,1465, 2 , 0 , 0 , 0 ,,
       4       4
      95  113.24
       4       4
      95  113.24
BR Coef=-1 , 1 , 1 ,0.9, 0 ,,,0.8,-1,1.2,0,
WSPro=,,,, 1 ,,,, 0 ,,,, 0 ,,,,-1 ,-1 ,-1 , 0 , 0 , 0 , 0 , 0
BC Design=,, 0 ,, 0 ,,,,,,
BC Use User HTab Curves=0
BC User HTab FreeFlow(D)= 0

Type RM Length L Ch R = 1 ,15434.33,71.37,84.22,95.76
BEGIN DESCRIPTION:
Downstream Section (12" PIPELINE)
END DESCRIPTION:
XS GIS Cut Line= 6
3034594.6914900213886504.24783043033876.2326251113885430.6718936
3033884.7673849513885295.94184813033882.6774941113885128.7587835
 3033841.683481613885035.05818353033354.78386486  13884721.65133
#Sta/Elev= 30
       0  119.65   19.95  119.68   44.89  122.75  109.73  126.24  319.21  120.66
  418.96  123.15  538.67  118.25  623.46  121.45  673.33  119.35  723.21  121.58
  812.99  116.53  852.89  118.43  937.68  117.58  992.54  112.98 1037.43  113.47
 1097.28  117.91 1286.81  118.66 1354.48   104.1 1388.23  105.69 1407.51   99.65
 1441.55   99.29 1451.39   99.93 1480.89  113.11 1500.56  117.12 1525.15  115.77
 1544.82  117.38 1786.87  117.49 2115.58   120.7 2220.41  118.61 2275.32  121.25
#Mann= 4 ,-1 , 0
       0     .07       0 1286.81     .04       0 1500.56     .07       0
 1786.87     .15       0
#XS Ineff= 2 ,-1
       0 1102.27  117.99  1736.2 2275.32     118
Permanent Ineff=
       F       F
#Block Obstruct= 2 , 0
       0   54.86  123.26               0
Bank Sta=1286.81,1500.56
XS Rating Curve= 0 ,0
Exp/Cntr=0.5,0.3

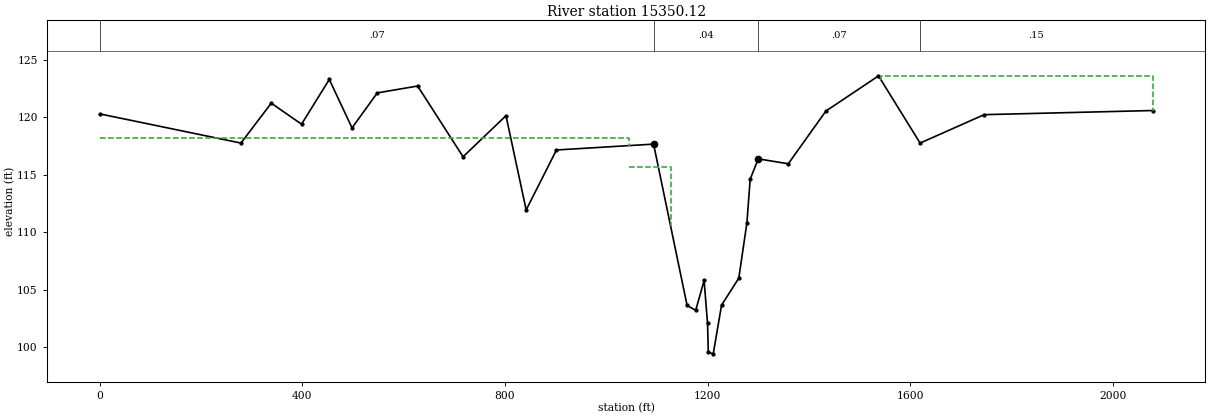
Type RM Length L Ch R = 1 ,15350.12,29.74,29.83,43.87
BEGIN DESCRIPTION:
Upstream Section (GOLF CART BRIDGE)
END DESCRIPTION:
XS GIS Cut Line= 6
3034647.8386934413886186.40889923033944.86798653 13885438.964856
3033951.3200733713885362.48174133033966.2472088613885161.2049129
3033986.7340445213884919.70441163033529.2831877813884649.2951755
#Sta/Elev= 30
       0   120.3  278.93  117.76  338.71  121.23  398.48   119.4  453.27  123.29
   498.1  119.08  547.91  122.12   627.6  122.72  717.26  116.57  801.94  120.14
  841.78  111.95  901.56  117.16 1093.24  117.67 1159.38  103.65 1176.39  103.22
 1192.97  105.82 1199.75  102.08 1201.23   99.58 1211.01   99.44 1227.39  103.67
 1261.45  106.02 1277.45  110.83 1283.88  114.62 1299.83  116.39 1359.07  115.96
 1433.27  120.54 1537.14   123.6 1619.27  117.76 1745.68  120.23 2078.42  120.59
#Mann= 4 ,-1 , 0
       0     .07       0 1093.24     .04       0 1299.83     .07       0
 1619.27     .15       0
#XS Ineff= 4 ,-1
       0 1045.27  118.23 1045.27 1126.73  115.66 1309.61 1542.09  115.74
 1542.09 2078.42  123.61
Permanent Ineff=
       F       F       F       F
Bank Sta=1093.24,1299.83
XS Rating Curve= 0 ,0
Exp/Cntr=0.5,0.3