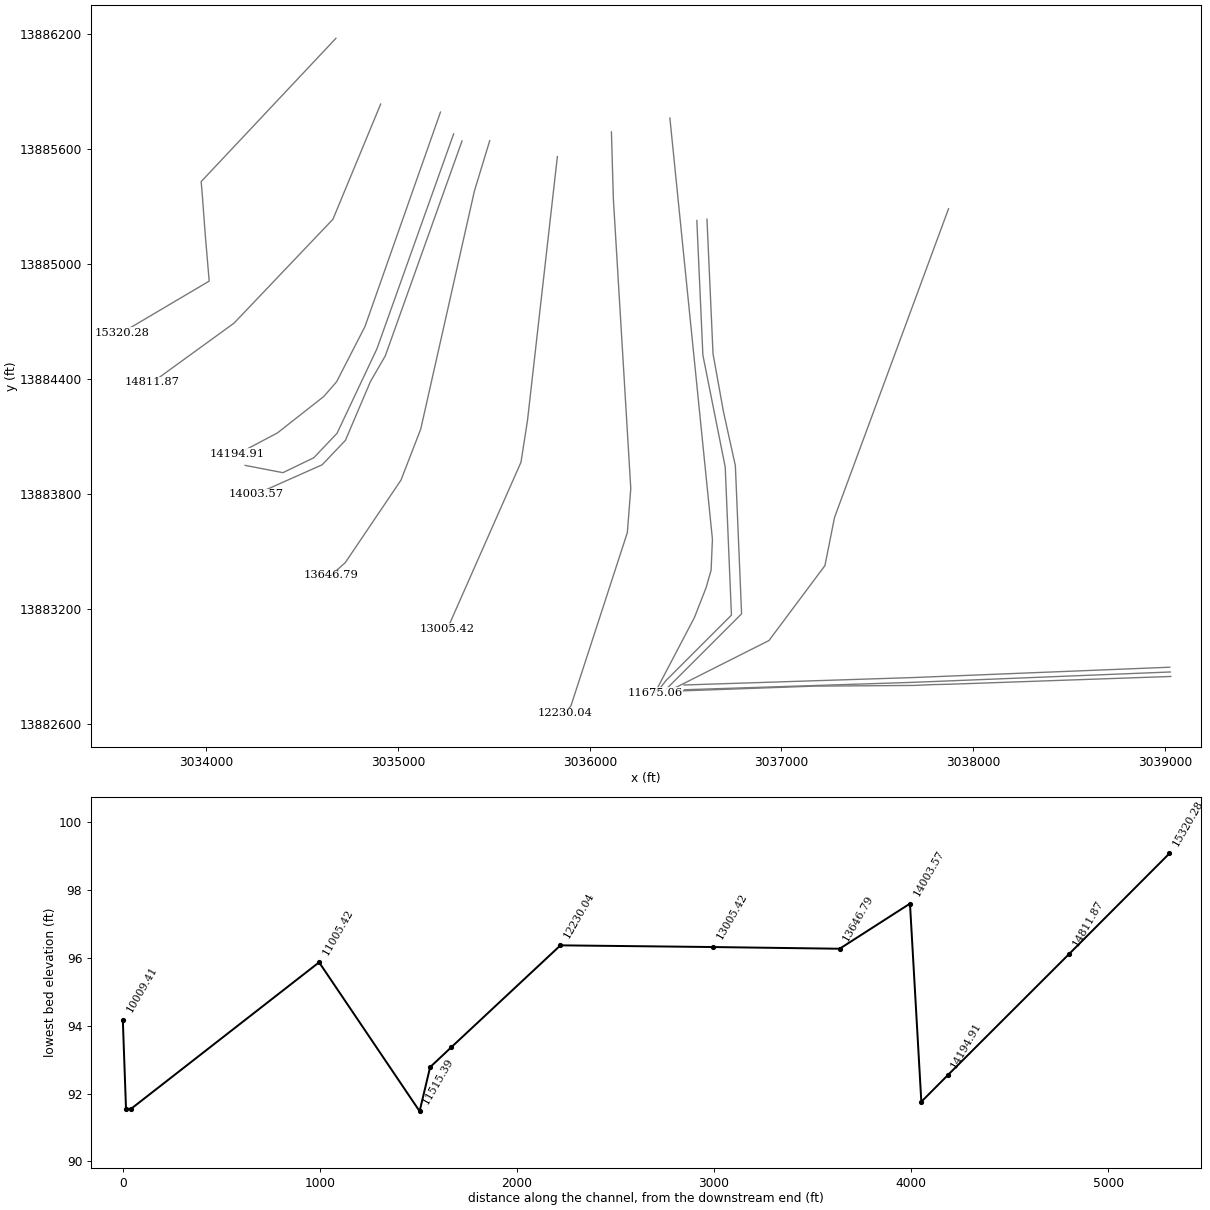
HEC-RAS study U106-00-00.prj: U106-00-00 2019 (Re-Study)

--- U106-00-00.g01 (geometry) --- (continued)

Type RM Length L Ch R = 3 ,15330.55,,,
BEGIN DESCRIPTION:
GOLF CART BRIDGE
END DESCRIPTION:
Node Name=GOLF CART BRIDGE
Bridge Culvert--1,0,-1,-1, 0
Deck Dist Width WeirC Skew NumUp NumDn MinLoCord MaxHiCord MaxSubmerge Is_Ogee
13.5,14,2.6,0, 48, 48, , , 0.98, 0, 0,0,,
 1102.83 1107.61 1112.39 1117.17 1121.95 1126.73 1131.51 1136.29 1141.07 1145.85
 1150.64 1155.42  1160.2 1164.98 1169.76 1174.54 1179.32  1184.1 1188.88 1193.66
 1198.44 1203.22    1208 1212.83 1217.66  1222.5 1227.33 1232.16    1237 1241.83
 1246.66  1251.5 1256.33 1261.16    1266 1270.83 1275.66  1280.5 1285.33 1290.16
    1295 1299.83 1304.66 1309.61 1314.56  1319.5 1324.45  1329.4
  115.44   115.7  119.36  119.37  119.38  119.38  119.39   119.4  119.41  119.41
  119.42  119.43  119.43  119.44  119.44  119.45  119.46  119.46  119.47  119.48
  119.48  119.49   119.5   119.5  119.49  119.49  119.48  119.47  119.47  119.46
  119.45  119.45  119.44  119.43  119.42  119.42  119.41  119.41   119.4  119.39
  119.38  119.38  119.37  119.36  119.35  119.35  119.34  116.23
       0       0       0       0   69.54  116.34  116.35  116.36  116.37  116.37
  116.38  116.39  116.39   116.4   116.4  116.41  116.42  116.42  116.43  116.44
  116.44  116.45  116.46  116.46  116.45  116.45  116.44  116.43  116.43  116.42
  116.41  116.41   116.4  116.39  116.38  116.38  116.37  116.37  116.36  116.35
  116.34  116.34  116.33  116.32       0       0       0       0
 1102.83 1107.61 1112.39 1117.17 1121.95 1126.73 1131.51 1136.29 1141.07 1145.85
 1150.64 1155.42  1160.2 1164.98 1169.76 1174.54 1179.32  1184.1 1188.88 1193.66
 1198.44 1203.22    1208 1212.83 1217.66  1222.5 1227.33 1232.16    1237 1241.83
 1246.66  1251.5 1256.33 1261.16    1266 1270.83 1275.66  1280.5 1285.33 1290.16
    1295 1299.83 1304.66 1309.61 1314.56  1319.5 1324.45  1329.4
  115.44   115.7  119.36  119.37  119.38  119.38  119.39   119.4  119.41  119.41
  119.42  119.43  119.43  119.44  119.44  119.45  119.46  119.46  119.47  119.48
  119.48  119.49   119.5   119.5  119.49  119.49  119.48  119.47  119.47  119.46
  119.45  119.45  119.44  119.43  119.42  119.42  119.41  119.41   119.4  119.39
  119.38  119.38  119.37  119.36  119.35  119.35  119.34  116.23
       0       0       0       0   69.48  116.24  116.25  116.26  116.27  116.27
  116.28  116.29  116.29   116.3   116.3  116.31  116.32  116.32  116.33  116.34
  116.34  116.35  116.36  116.36  116.35  116.35  116.34  116.33  116.33  116.32
  116.31  116.31   116.3  116.29  116.28  116.28  116.27  116.27  116.26  116.25
  116.24  116.24  116.23  116.22       0       0       0       0
Pier Skew, UpSta & Num, DnSta & Num=  ,1137.25, 2 ,1137.25, 2 , 0 , 0 , 0 ,,
     1.4     1.4
      90   117.4
     1.4     1.4
      90   117.4
Pier Skew, UpSta & Num, DnSta & Num=  ,1151.55, 2 ,1151.55, 2 , 0 , 0 , 0 ,,
     1.4     1.4
      90   117.4
     1.4     1.4
      90   117.4
Pier Skew, UpSta & Num, DnSta & Num=  ,1166.35, 2 ,1166.35, 2 , 0 , 0 , 0 ,,
     1.4     1.4
      90   117.4
     1.4     1.4
      90   117.4
Pier Skew, UpSta & Num, DnSta & Num=  ,1181.15, 2 ,1181.15, 2 , 0 , 0 , 0 ,,
     1.4     1.4
      90   117.4
     1.4     1.4
      90   117.4
Pier Skew, UpSta & Num, DnSta & Num=  ,1196.35, 2 ,1196.35, 2 , 0 , 0 , 0 ,,
     1.4     1.4
      90   117.4
     1.4     1.4
      90   117.4
Pier Skew, UpSta & Num, DnSta & Num=  ,1211.35, 2 ,1211.35, 2 , 0 , 0 , 0 ,,
     1.4     1.4
      90   117.4
     1.4     1.4
      90   117.4
Pier Skew, UpSta & Num, DnSta & Num=  ,1227.05, 2 ,1227.05, 2 , 0 , 0 , 0 ,,
     1.4     1.4
      90   117.4
     1.4     1.4
      90   117.4
Pier Skew, UpSta & Num, DnSta & Num=  ,1241.05, 2 ,1241.05, 2 , 0 , 0 , 0 ,,
     1.4     1.4
      90   117.4
     1.4     1.4
      90   117.4
Pier Skew, UpSta & Num, DnSta & Num=  ,1255.25, 2 ,1255.25, 2 , 0 , 0 , 0 ,,
     1.4     1.4
      90   117.4
     1.4     1.4
      90   117.4
Pier Skew, UpSta & Num, DnSta & Num=  ,1269.15, 2 ,1269.15, 2 , 0 , 0 , 0 ,,
     1.4     1.4
      90   117.4
     1.4     1.4
      90   117.4
Pier Skew, UpSta & Num, DnSta & Num=  ,1284.95, 2 ,1284.95, 2 , 0 , 0 , 0 ,,
     1.4     1.4
      90   117.4
     1.4     1.4
      90   117.4
Pier Skew, UpSta & Num, DnSta & Num=  ,1298.05, 2 ,1298.05, 2 , 0 , 0 , 0 ,,
     1.4     1.4
      90   117.4
     1.4     1.4
      90   117.4
BR Coef=-1 , 1 , 1 ,0.9, 0 ,,,0.8,-1,1.2,0,
WSPro=,,,, 1 ,,,, 0 ,,,, 0 ,,,,-1 ,-1 ,-1 , 0 , 0 , 0 , 0 , 0
BC Design=,, 0 ,, 0 ,,,,,,
BC Use User HTab Curves=0
BC User HTab FreeFlow(D)= 0

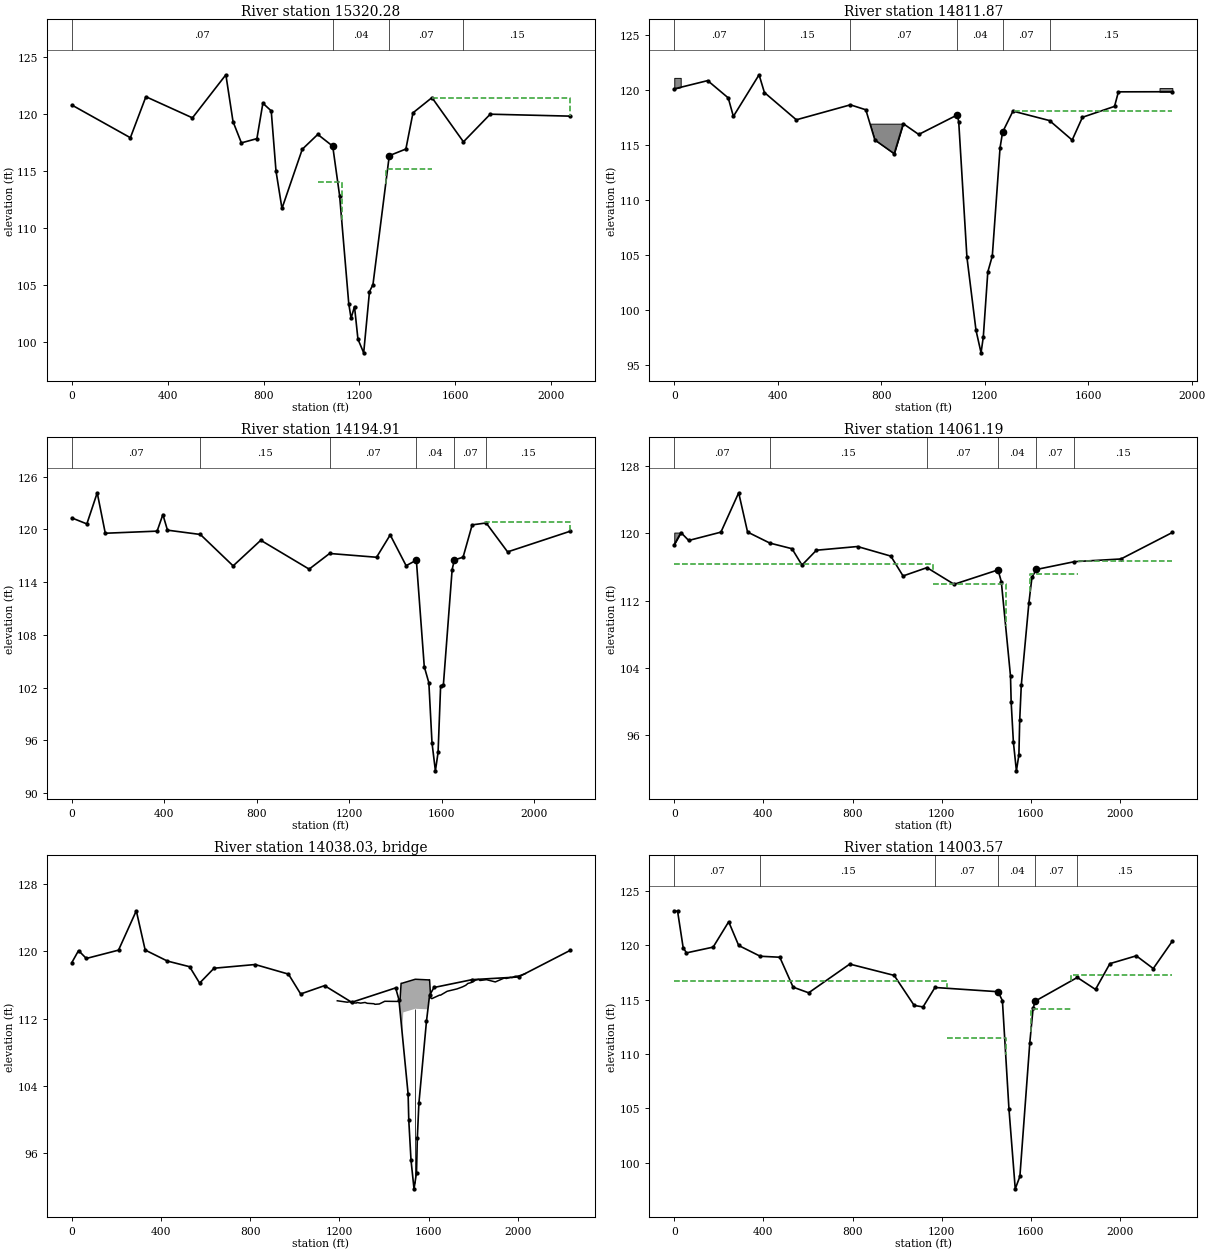
Type RM Length L Ch R = 1 ,15320.28,666.27,508.41,435.95
BEGIN DESCRIPTION:
Downstream Section (GOLF CART BRIDGE)
END DESCRIPTION:
Node Name=O
XS GIS Cut Line= 6
3034675.3931002813886174.96896143033972.4223933713885427.5249183
3033978.8744801913885351.0418035 3033993.801615713885149.7649751
3034014.2884513613884908.26447393033556.8375946113884637.8552378
#Sta/Elev= 30
       0  120.77  244.07  117.91  308.82   121.5  503.08  119.65  642.55  123.42
  672.43  119.32   707.3  117.46  772.05  117.83  796.96  120.93  831.82  120.26
  851.75  114.99  876.65  111.72  961.33   116.9 1026.08   118.2 1088.44  117.17
 1117.17  112.84 1155.42  103.37 1164.98  102.11 1179.32  103.13 1193.66  100.28
 1217.66   99.08 1241.83  104.44 1256.33  105.05 1324.45  116.34  1393.7  116.92
 1423.37  120.09 1502.52  121.42 1633.89  117.55 1745.68  119.97 2078.42   119.8
#Mann= 4 ,-1 , 0
       0     .07       0 1088.44     .04       0 1324.45     .07       0
 1633.89     .15       0
#XS Ineff= 4 ,-1
       0 1026.08   118.2 1026.08 1126.73     114 1309.61 1502.52   115.2
 1502.52 2078.42  121.42
Permanent Ineff=
       F       F       F       F
Bank Sta=1088.44,1324.45
XS Rating Curve= 0 ,0
Exp/Cntr=0.5,0.3

Type RM Length L Ch R = 1 ,14811.87,611.9,616.96,610.97
XS GIS Cut Line= 5
3034908.9999165213885832.00015923034660.0000864413885231.0000488
 3034144.000134213884689.00014863033718.0000019413884380.0001104
3033718.0000019413884380.0001104
#Sta/Elev= 30
       0   120.1  129.11  120.85  208.57  119.28  228.43   117.6  327.75  121.38
  348.36  119.77  471.77  117.29  680.82  118.65  740.34   118.2  775.26  115.46
   850.1  114.21  885.02  116.94  944.89  115.96 1094.56  117.74 1099.55  117.06
 1131.13  104.81 1166.21   98.17 1185.78   96.12 1194.47   97.57 1211.85  103.47
 1229.26  104.92 1259.19  114.76 1269.17  116.18 1309.08  118.08 1450.39  117.22
  1537.9  115.45 1577.61  117.52 1701.73  118.51 1716.63  119.83 1925.15  119.84
#Mann= 6 ,-1 , 0
       0     .07       0  348.36     .15       0  680.82     .07       0
 1094.56     .04       0 1269.17     .07       0 1450.39     .15       0
#XS Ineff= 2 ,-1
       0 1094.56  117.74 1314.07 1925.15  118.09
Permanent Ineff=
       F       F
#Block Obstruct= 3 ,-1
       0   24.83   121.1  740.34  885.02  116.94  1875.5 1925.15  120.17
Bank Sta=1094.56,1269.17
XS Rating Curve= 0 ,0
Exp/Cntr=0.3,0.1

Type RM Length L Ch R = 1 ,14194.91,119.09,133.72,161.32
XS GIS Cut Line= 6
 3035220.999948713885789.99991513034827.0000805313884670.9998565
3034679.0000484413884383.00010443034611.9998543613884305.9999304
3034370.0000102813884115.9999823 3034162.000098213884005.9998742
#Sta/Elev= 30
       0  121.29    64.8  120.61  109.66  124.15  144.55  119.55  368.86  119.79
  393.78  121.67  413.72   119.9  556.03  119.41  697.85  115.84  817.48  118.75
 1026.83  115.47 1115.37  117.25 1318.57  116.82 1377.62  119.36 1446.52  115.86
 1490.81  116.49 1525.08  104.38 1544.92  102.55 1558.54   95.73 1573.25   92.54
 1584.81   94.63 1595.85  102.19 1607.71  102.28  1645.7  115.42 1655.17  116.51
 1693.04  116.83  1732.4   120.5 1792.86  120.72 1885.71  117.43 2155.63  119.77
#Mann= 6 ,-1 , 0
       0     .07       0  556.03     .15       0 1115.37     .07       0
 1490.81     .04       0 1655.17     .07       0 1792.86     .15       0
#XS Ineff= 2 ,-1
       0 1377.62  119.36  1786.8 2155.63  120.86
Permanent Ineff=
       F       F
Bank Sta=1490.81,1655.17
XS Rating Curve= 0 ,0
Exp/Cntr=0.5,0.3

Type RM Length L Ch R = 1 ,14061.19,57.89,57.62,60.73
BEGIN DESCRIPTION:
Upstream Section (TRAILSIDE DR)
END DESCRIPTION:
Node Name=N
XS GIS Cut Line= 6
 3035289.746202313885676.3420059 3034889.380861313884554.8714799
 3034681.3668416 13884114.243096  3034559.955339 13883986.605556
 3034399.111172513883908.7776277    3034201.9165  13883946.82079
#Sta/Elev= 30
       0  118.67   29.89  120.09   64.77  119.15  209.26  120.14  288.98  124.82
  328.84  120.15  428.67  118.84  528.13  118.17  572.98  116.22  637.75  117.99
  822.09  118.43  971.57  117.29 1026.37  114.93 1133.66  115.92 1255.46  113.94
 1452.55  115.65 1467.21  114.26 1508.49  103.02 1511.45   99.92 1521.45   95.17
 1534.95   91.76 1546.11   93.66 1549.76   97.77 1556.77  101.91 1590.79  111.68
  1604.8  114.78 1624.54   115.7 1795.41  116.63 2003.91  116.95 2234.61   120.1
#Mann= 6 ,-1 , 0
       0     .07       0  428.67     .15       0 1133.66     .07       0
 1452.55     .04       0 1624.54     .07       0 1795.41     .15       0
#XS Ineff= 4 ,-1
       0  1160.9  116.39  1160.9 1486.76  113.94 1596.99 1810.96  115.12
 1810.96 2234.61  116.74
Permanent Ineff=
       F       F       F       F
#Block Obstruct= 2 , 0
       0   29.89  120.09               0
Bank Sta=1452.55,1624.54
XS Rating Curve= 0 ,0
Exp/Cntr=0.5,0.3

Type RM Length L Ch R = 3 ,14038.03,,,
BEGIN DESCRIPTION:
TRAILSIDE DR
END DESCRIPTION:
Node Name=TRAILSIDE DR
Bridge Culvert--1,0,-1,-1, 0
Deck Dist Width WeirC Skew NumUp NumDn MinLoCord MaxHiCord MaxSubmerge Is_Ogee
5.5,45,2.6,0, 45, 45, , , 0.98, 0, 0,0,,
 1190.79 1235.56 1245.51 1250.49 1275.36 1280.34 1295.26 1315.16 1325.11 1354.79
 1359.67 1379.23 1403.67 1462.32  1472.1 1476.99 1481.88 1486.76 1540.63 1594.93
 1599.86  1604.8 1609.74 1614.67 1649.23 1654.16 1683.74 1727.78 1752.24 1766.92
 1776.71 1791.39 1810.96 1820.75 1825.64 1830.54 1859.97 1899.68 1939.38 1949.31
 1969.16 1974.13 1989.02 2003.91 2034.61
  114.12  113.95  114.01  113.92  113.85  113.91  113.84  113.92  113.82  113.77
   113.7  113.74  114.06  114.04  114.15   116.2  116.21  116.25  116.68  116.61
   116.6  116.62  114.46  114.37  114.79  114.79  115.25  115.53  115.77  115.96
  116.18  116.28  116.57  116.64  116.66  116.53  116.63  116.36  116.82  116.77
  116.91  116.87  117.04  117.06  117.35
       0       0       0       0       0       0       0       0       0       0
       0       0       0       0       0   45.79  105.82  112.74  113.17   113.1
  108.46       0       0       0       0       0       0       0       0       0
       0       0       0       0       0       0       0       0       0       0
       0       0       0       0       0
 1190.79 1235.56 1245.51 1250.49 1275.36 1280.34 1295.26 1315.16 1325.11 1354.79
 1359.67 1379.23 1403.67 1462.32  1472.1 1476.99 1481.88 1486.76 1540.63 1594.93
 1599.86  1604.8 1609.74 1614.67 1649.23 1654.16 1683.74 1727.78 1752.24 1766.92
 1776.71 1791.39 1810.96 1820.75 1825.64 1830.54 1859.97 1899.68 1939.38 1949.31
 1969.16 1974.13 1989.02 2003.91 2034.61
  114.12  113.95  114.01  113.92  113.85  113.91  113.84  113.92  113.82  113.77
   113.7  113.74  114.06  114.04  114.15   116.2  116.21  116.25  116.68  116.61
   116.6  116.62  114.46  114.37  114.79  114.79  115.25  115.53  115.77  115.96
  116.18  116.28  116.57  116.64  116.66  116.53  116.63  116.36  116.82  116.77
  116.91  116.87  117.04  117.06  117.35
       0       0       0       0       0       0       0       0       0       0
       0       0       0       0       0   45.72  105.67  112.58  113.01  112.94
  108.31       0       0       0       0       0       0       0       0       0
       0       0       0       0       0       0       0       0       0       0
       0       0       0       0       0
Pier Skew, UpSta & Num, DnSta & Num=  ,1539.35, 2 ,1539.35, 2 , 0 , 0 , 0 ,,
     1.3     1.3
   96.78  114.17
     1.3     1.3
   96.62  114.01
Abutment Skew #Up #Dn= , 3 , 3
 1592.55 1599.84    1600
  110.93  113.09  113.09
 1592.55 1599.84    1600
  110.77  112.93  112.93
BR Coef=-1 , 1 , 1 ,0.9, 0 ,,,0.8,-1,1.2,0,
WSPro=,,,, 1 ,,,, 0 ,,,, 0 ,,,,-1 ,-1 ,-1 , 0 , 0 , 0 , 0 , 0
BC Design=,, 0 ,, 0 ,,,,,,
BC Use User HTab Curves=0
BC User HTab FreeFlow(D)= 0

Type RM Length L Ch R = 1 ,14003.57,346.79,356.77,361.23
BEGIN DESCRIPTION:
Downstream Section (TRAILSIDE DR)
END DESCRIPTION:
Node Name=M
XS GIS Cut Line= 6
 3035333.459041413885639.6189823 3034933.093700413884518.1484562
 3034855.830731513884384.6808753 3034725.079680713884077.5200724
 3034603.668178113883949.8825324   3034257.01067  13883795.65134
#Sta/Elev= 30
       0  123.16   14.95  123.11   39.86  119.77   54.81  119.29  174.38  119.82
  244.14  122.15  288.98  119.97  385.66  118.98  473.33  118.89  533.12  116.14
  602.87  115.62  787.22  118.26  986.51  117.22  1076.2  114.46 1116.06  114.32
 1169.55  116.11 1452.55  115.72  1472.1   114.9 1501.43  104.96 1529.69    97.6
  1550.5   98.74 1594.93  111.02 1609.74  114.19 1619.61  114.86 1808.13  117.03
 1889.75  115.93 1954.27   118.3 2072.69  119.02 2148.85  117.85 2234.53  120.37
#Mann= 6 ,-1 , 0
       0     .07       0  385.66     .15       0 1169.55     .07       0
 1452.55     .04       0 1619.61     .07       0 1808.13     .15       0
#XS Ineff= 4 ,-1
       0 1225.62  116.69 1225.62 1486.76   111.5 1599.77  1781.6   114.1
  1781.6 2234.53  117.23
Permanent Ineff=
       F       F       F       F
Bank Sta=1452.55,1619.61
XS Rating Curve= 0 ,0
Exp/Cntr=0.5,0.3

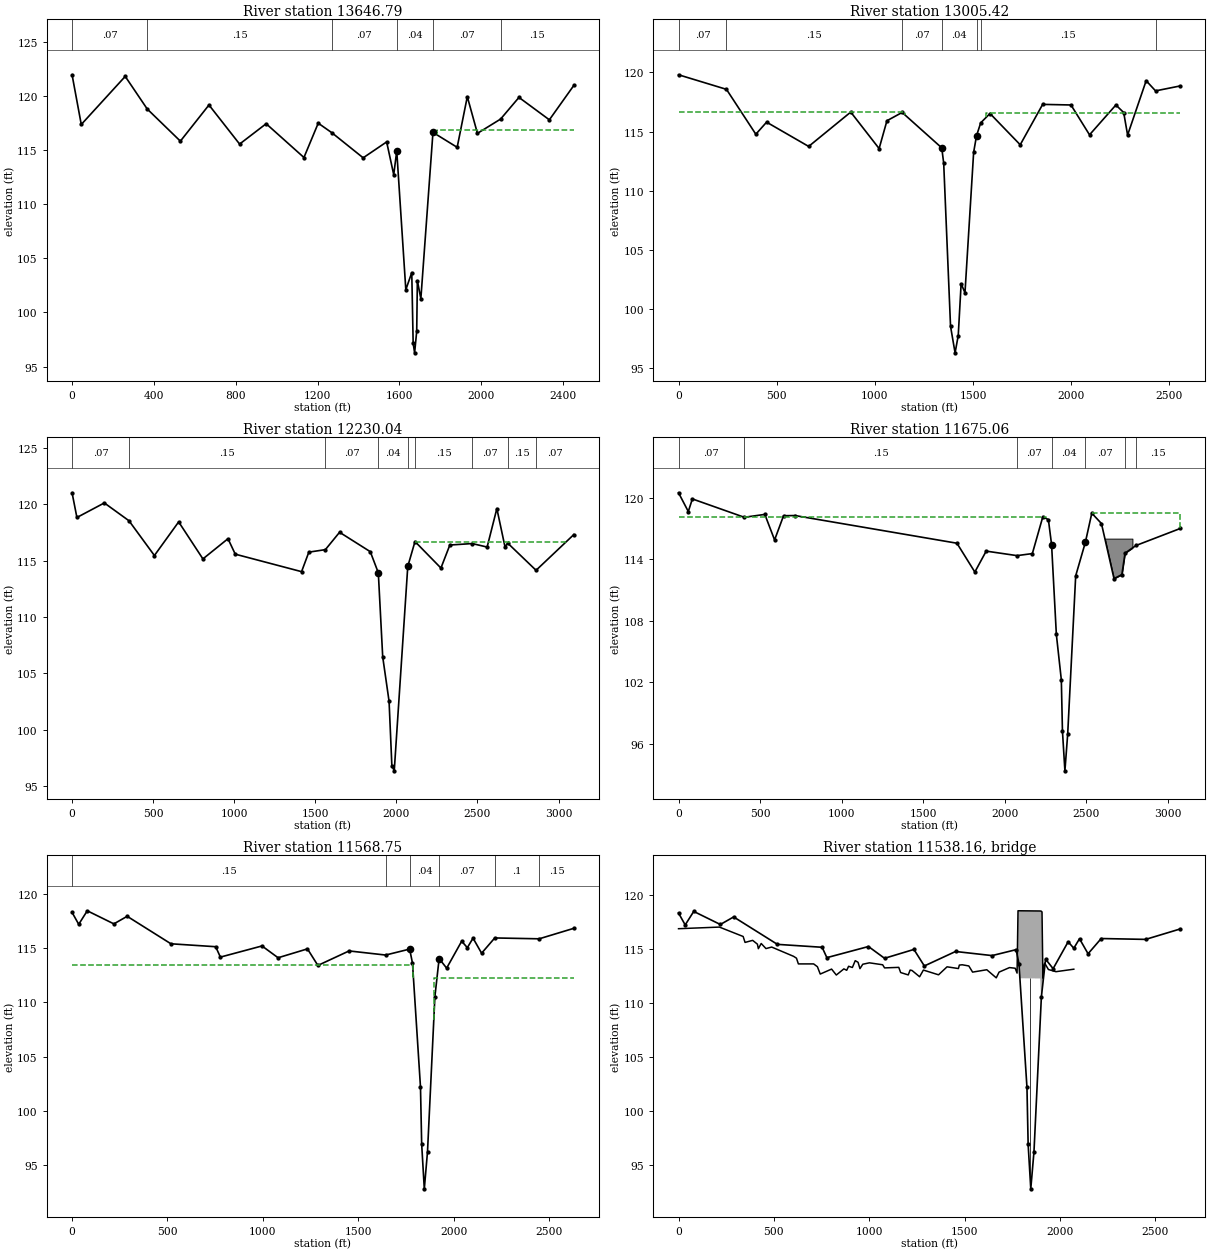
Type RM Length L Ch R = 1 ,13646.79,610.1,641.37,645.17
XS GIS Cut Line= 6
 3035478.0000909 13885640.999885 3035397.999922813885378.0000829
 3035118.000154713884135.9999423 3035015.000032613883870.0001462
 3034723.999958413883439.0000239   3034649.31545  13883372.50022
#Sta/Elev= 30
       0  121.95   44.98  117.36   259.9   121.8  367.45  118.79  529.53  115.82
  669.33  119.16  819.12  115.55  948.93  117.43 1133.67  114.31 1203.56  117.48
 1270.77  116.59 1423.25  114.28 1538.08  115.75 1572.66  112.72 1587.41  114.92
 1631.77   102.1 1660.84  103.68 1667.67   97.15 1674.73   96.27 1685.01   98.26
 1688.21  102.94 1705.25  101.26 1764.46  116.63 1882.84  115.25 1932.37  119.93
  1981.9  116.54 2095.17  117.86 2184.96  119.86 2333.55  117.79 2453.35  120.97
#Mann= 6 ,-1 , 0
       0     .07       0  367.45     .15       0 1270.77     .07       0
 1587.41     .04       0 1764.46     .07       0 2095.17     .15       0
#XS Ineff= 2 ,-1
       0 1203.56  117.48 1784.13 2453.35  116.88
Permanent Ineff=
       F       F
Bank Sta=1587.41,1764.46
XS Rating Curve= 0 ,0
Exp/Cntr=0.3,0.1

Type RM Length L Ch R = 1 ,13005.42,746.64,775.39,766.47
XS GIS Cut Line= 4
3035831.00004102 13885558.0000513035675.0000249413884180.9998523
3035641.0000929413883962.99996023035256.9998766913883094.0000578
#Sta/Elev= 30
       0   119.8  244.16  118.57  393.81  114.78  448.64   115.8  662.99  113.75
  877.35  116.65 1021.91  113.57 1061.79  115.92 1139.34  116.62 1340.94  113.63
 1350.91  112.34 1385.81   98.56 1408.93   96.32 1425.03   97.78 1439.74  102.16
 1459.35  101.39 1503.48  113.25 1518.19  114.65 1539.48  115.74 1586.83  116.53
 1740.75  113.89 1855.15   117.3  1999.4  117.25 2093.91  114.73 2228.21  117.25
 2268.01  116.61  2287.9  114.71 2382.41   119.3 2430.29  118.44 2556.51  118.86
#Mann= 7 ,-1 , 0
       0     .07       0  244.16     .15       0 1139.34     .07       0
 1340.94     .04       0 1518.19     .07       0 1539.48     .15       0
 2430.29     .07       0
#XS Ineff= 2 ,-1
       0 1151.52  116.66 1567.22 2556.51  116.59
Permanent Ineff=
       F       F
Bank Sta=1340.94,1518.19
XS Rating Curve= 0 ,0
Exp/Cntr=0.3,0.1

Type RM Length L Ch R = 1 ,12230.04,564.02,554.97,538.81
Node Name=L
XS GIS Cut Line= 6
 3036113.000133213885687.0001211 3036123.000113213885339.0001609
 3036213.999931213883825.9999061 3036195.9999672 13883596.000038
  3035901.99989913882692.9998755   3035872.13858  13882652.89624
#Sta/Elev= 30
       0  121.01   29.84  118.82  198.94  120.11  350.98  118.53  507.69  115.45
  657.27  118.43  806.85  115.15  961.42  116.94 1006.29  115.57 1415.14  114.02
 1460.01  115.75 1561.87  115.97 1649.48  117.51 1838.95  115.79 1888.42  113.92
  1915.5  106.47 1954.77  102.53 1971.95   96.84 1986.63   96.37 2070.04  114.48
 2114.57  116.69 2274.51  114.34 2329.49  116.38 2467.51  116.51 2559.41   116.2
 2619.39  119.61 2669.37  116.23 2686.97  116.54 2861.14  114.14 3094.21  117.31
#Mann= 9 ,-1 , 0
       0     .07       0  350.98     .15       0 1561.87     .07       0
 1888.42     .04       0 2070.04     .07       0 2114.57     .15       0
 2467.51     .07       0 2686.97     .15       0 2861.14     .07       0
#XS Ineff= 2 ,-1
       0 1649.48  117.51 2114.57 3044.23  116.69
Permanent Ineff=
       F       F
Bank Sta=1888.42,2070.04
XS Rating Curve= 0 ,0
Exp/Cntr=0.3,0.1

Type RM Length L Ch R = 1 ,11675.06,99.8,106.31,122.89
XS GIS Cut Line= 6
 3036417.999851313885758.9999771 3036640.0000635 13883561.000108
 3036633.000077413883400.0001019 3036607.000129513883308.9999558
 3036545.999923413883152.9999398   3036339.70908  13882759.75884
#Sta/Elev= 30
       0  120.48    59.9  118.65   84.85  119.88  403.04  118.09  529.08  118.37
  588.98  115.88  643.88  118.24  713.76  118.26 1707.03  115.56 1816.83  112.75
 1886.37  114.79  2075.5  114.35 2169.46  114.55 2233.61  118.14  2267.8  117.86
 2287.33  115.43 2316.63  106.66  2347.1  102.24 2353.96   97.25 2369.04   93.36
 2386.19   96.96 2435.18  112.38 2494.55  115.65 2533.96  118.49 2593.08  117.48
 2670.07  112.11  2718.4   112.5 2737.62  114.59 2805.22  115.34 3076.76     117
#Mann= 7 ,-1 , 0
       0     .07       0  403.04     .15       0  2075.5     .07       0
 2287.33     .04       0 2494.55     .07       0 2737.62      .1       0
 2805.22     .15       0
#XS Ineff= 2 ,-1
       0 2253.15  118.16 2533.96 3076.76  118.49
Permanent Ineff=
       F       F
#Block Obstruct= 1 ,-1
 2533.96 2783.02  116.01
Bank Sta=2287.33,2494.55
XS Rating Curve= 0 ,0
Exp/Cntr=0.5,0.3

Type RM Length L Ch R = 1 ,11568.75,55.03,53.36,54.79
BEGIN DESCRIPTION:
Upstream Section (HUFFMEISTER ROAD)
END DESCRIPTION:
Node Name=K
XS GIS Cut Line= 6
 3036558.586840513885224.3711251 3036590.192748413884521.9565194
 3036706.695796213883938.2841303 3036739.180639413883165.5041799
 3036397.304354613882823.7335379   3036351.31104  13882764.49153
#Sta/Elev= 30
       0  118.32   34.87  117.22    79.7  118.47  219.17  117.26   288.9  117.96
  518.26  115.42  752.77  115.15  777.55  114.19  995.61  115.22    1080  114.13
 1233.95  114.95 1288.57  113.42 1452.25  114.76 1643.62  114.38 1769.67  114.93
 1784.55  113.63 1826.46  102.19 1832.74   96.89 1846.51   92.78 1863.27   96.21
 1902.05  110.55 1924.19  114.05 1963.63  113.17  2042.5  115.66 2072.08  115.06
 2101.98  115.94 2146.84  114.55 2215.77  115.96 2448.63  115.88 2630.49  116.85
#Mann= 6 ,-1 , 0
       0     .15       0 1643.62     .07       0 1769.67     .04       0
 1924.19     .07       0 2215.77      .1       0 2448.63     .15       0
#XS Ineff= 2 ,-1
       0 1789.51  113.42 1896.11 2630.49  112.29
Permanent Ineff=
       F       F
Bank Sta=1769.67,1924.19
XS Rating Curve= 0 ,0
Exp/Cntr=0.5,0.3

Type RM Length L Ch R = 3 ,11538.16,,,
BEGIN DESCRIPTION:
HUFFMEISTER ROAD
END DESCRIPTION:
Node Name=HUFFMEISTER ROAD
Bridge Culvert--1,0,-1,-1, 0
Deck Dist Width WeirC Skew NumUp NumDn MinLoCord MaxHiCord MaxSubmerge Is_Ogee
10.5,34,2.6,0, 60, 60, , , 0.98, 0, 0,0,,
       0  214.19  338.71  348.68  388.52  413.43  418.41  433.35  458.28  488.27
  603.24  618.23  628.23  708.16  727.99  742.86  802.33  827.11  866.76  881.62
  891.53  911.36  926.23   941.1  951.01  965.88 1000.57 1070.07    1080 1154.49
 1164.42 1204.15 1214.08 1224.01 1263.74 1283.61 1362.98 1407.62 1467.13 1472.09
 1486.97 1521.69 1541.53 1615.92 1665.52  1680.4 1734.95 1764.71 1774.63 1779.59
 1789.51 1896.11 1900.79 1905.47 1910.15 1914.83 1919.51 1938.98 1978.42 2072.08
  116.87  117.02  116.15   115.6  115.79  115.44  115.02   115.5  115.03  115.17
  114.31  114.14  113.61  113.61  113.35  112.67  113.13  112.58  113.15  113.02
  113.39  113.28  113.91  113.76  113.17  113.58  113.71  113.53  113.24  113.29
  112.81  112.59  113.04     113  112.42  113.04   112.6  113.34  113.18   113.5
  113.53  113.42  112.85  113.07  112.32  112.85  113.27  113.21  112.76  118.53
  118.53  118.51   118.5  118.42  112.29  113.32  113.68  113.09  112.89  113.12
       0       0       0       0       0       0       0       0       0       0
       0       0       0       0       0       0       0       0       0       0
       0       0       0       0       0       0       0       0       0       0
       0       0       0       0       0       0       0       0       0       0
       0       0       0       0       0       0       0       0       0   31.04
  112.28  112.26   93.71   43.36       0       0       0       0       0       0
       0  214.19  338.71  348.68  388.52  413.43  418.41  433.35  458.28  488.27
  603.24  618.23  628.23  708.16  727.99  742.86  802.33  827.11  866.76  881.62
  891.53  911.36  926.23   941.1  951.01  965.88 1000.57 1070.07    1080 1154.49
 1164.42 1204.15 1214.08 1224.01 1263.74 1283.61 1362.98 1407.62 1467.13 1472.09
 1486.97 1521.69 1541.53 1615.92 1665.52  1680.4 1734.95 1764.71 1774.63 1779.59
 1789.51 1896.11 1900.79 1905.47 1910.15 1914.83 1919.51 1938.98 1978.42 2072.08
  116.87  117.02  116.15   115.6  115.79  115.44  115.02   115.5  115.03  115.17
  114.31  114.14  113.61  113.61  113.35  112.67  113.13  112.58  113.15  113.02
  113.39  113.28  113.91  113.76  113.17  113.58  113.71  113.53  113.24  113.29
  112.81  112.59  113.04     113  112.42  113.04   112.6  113.34  113.18   113.5
  113.53  113.42  112.85  113.07  112.32  112.85  113.27  113.21  112.76  118.53
  118.53  118.51   118.5  118.42  112.29  113.32  113.68  113.09  112.89  113.12
       0       0       0       0       0       0       0       0       0       0
       0       0       0       0       0       0       0       0       0       0
       0       0       0       0       0       0       0       0       0       0
       0       0       0       0       0       0       0       0       0       0
       0       0       0       0       0       0       0       0       0   31.01
  112.18  112.16   93.63   43.32       0       0       0       0       0       0
Pier Skew, UpSta & Num, DnSta & Num=  ,1842.91, 2 ,1842.91, 2 , 0 , 0 , 0 ,,
     1.3     1.3
   91.91  113.09
     1.3     1.3
   91.81  112.99
Abutment Skew #Up #Dn= , 2 , 2
 1785.71 1790.21
   112.3  110.56
 1785.71 1790.21
   112.2  110.46
BR Coef=-1 , 1 , 1 ,0.9, 0 ,,,0.8,-1,1.2,0,
WSPro=,,,, 1 ,,,, 0 ,,,, 0 ,,,,-1 ,-1 ,-1 , 0 , 0 , 0 , 0 , 0
BC Design=,, 0 ,, 0 ,,,,,,
BC Use User HTab Curves=0
BC User HTab FreeFlow(D)= 0

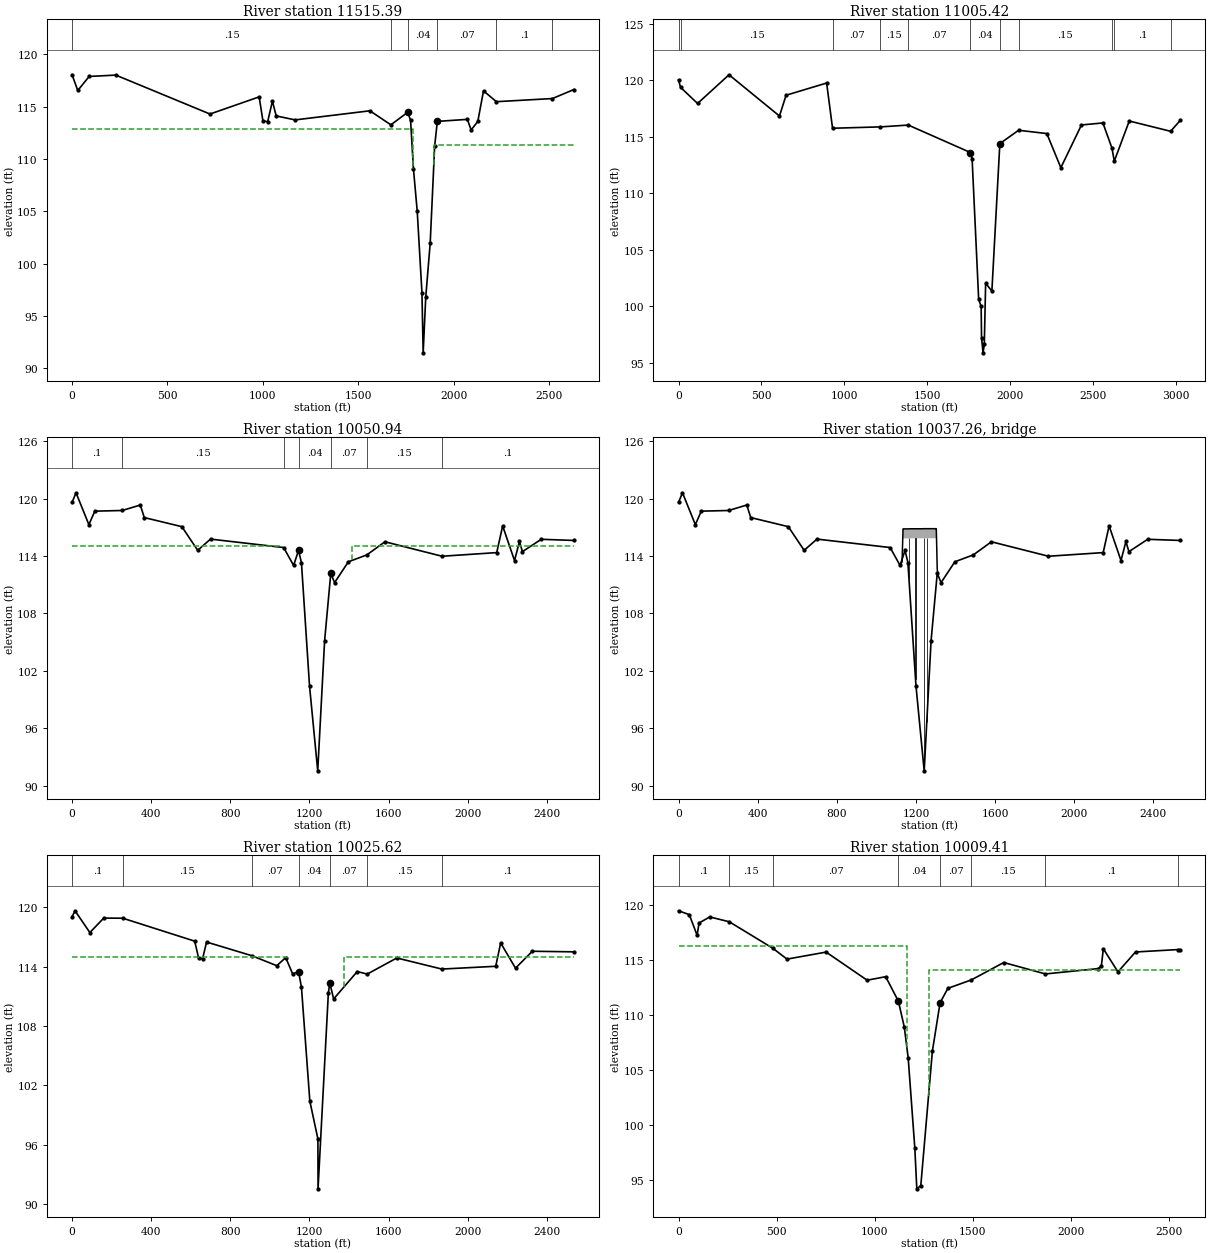
Type RM Length L Ch R = 1 ,11515.39,545.34,509.97,491.61
BEGIN DESCRIPTION:
Downstream Section (HUFFMEISTER ROAD)
END DESCRIPTION:
Node Name=J
XS GIS Cut Line= 6
 3036611.497823913885231.2982766 3036643.103731813884528.8836709
 3036697.6584127  13884226.49484 3036759.606779613883945.2112819
 3036792.091622813883172.4313314   3036397.17413  13882777.63588
#Sta/Elev= 30
       0  118.04   29.89  116.54   89.66  117.88  229.13  118.01  723.03  114.29
  980.74  115.93 1000.57  113.63 1025.38  113.56 1050.21  115.52 1070.07  114.11
 1169.39  113.73 1561.36   114.6 1671.12  113.26 1759.75  114.46 1774.63  113.68
 1789.51  109.06 1809.35  105.02 1834.14   97.23 1840.54   91.48 1853.98   96.78
 1877.39  101.97 1900.79  111.24 1914.83  113.59 2072.08  113.78 2092.02  112.77
  2126.9  113.58  2156.8   116.5  2224.5  115.47 2518.18  115.77 2630.48  116.63
#Mann= 6 ,-1 , 0
       0     .15       0 1671.12     .07       0 1759.75     .04       0
 1914.83     .07       0  2224.5      .1       0 2518.18     .15       0
#XS Ineff= 2 ,-1
       0 1789.51   112.9 1896.11 2630.48   111.3
Permanent Ineff=
       F       F
Bank Sta=1759.75,1914.83
XS Rating Curve= 0 ,0
Exp/Cntr=0.5,0.3

Type RM Length L Ch R = 1 ,11005.42,1026.36,954.48,822.41
XS GIS Cut Line= 5
3037871.9998960213885285.99993883037277.00010177  13883674.99988
 3037226.999873713883424.00005393036935.0001296113883032.9998517
3036429.0001573613882778.0000336
#Sta/Elev= 30
       0  120.01   12.09  119.36  114.82  117.93  304.53  120.47  609.07  116.82
     649  118.66  893.63  119.74  929.38  115.74 1218.27  115.86 1386.54  116.02
 1761.66  113.59 1771.51  113.03 1811.06  100.61 1826.07   99.97 1828.42    97.2
 1837.57   95.87 1845.06   96.62 1853.14  102.03 1890.79  101.33 1938.85  114.38
 2052.05  115.56 2222.28  115.27 2306.94  112.25 2431.43  116.03 2560.71  116.21
 2615.26  113.99 2629.49  112.83 2719.77  116.38 2969.43  115.47 3027.93  116.44
#Mann= 11 ,-1 , 0
       0     .07       0   12.09     .15       0  929.38     .07       0
 1218.27     .15       0 1386.54     .07       0 1761.66     .04       0
 1938.85     .07       0 2052.05     .15       0 2615.26     .07       0
 2629.49      .1       0 2969.43     .15       0
#XS Ineff= 2 ,-1
       0 1273.05     115 2222.28 3027.93     115
Permanent Ineff=
       F       F
Bank Sta=1761.66,1938.85
XS Rating Curve= 0 ,0
Exp/Cntr=0.4,0.2

Type RM Length L Ch R = 1 ,10050.94,24.95,25.32,30.66
BEGIN DESCRIPTION:
Upstream Section (12" PIPELINE)
END DESCRIPTION:
Node Name=I
XS GIS Cut Line= 5
 3039026.3112357 13882893.7219153037877.2653054413882847.4382149
3037786.7910769413882843.79386533037690.6390382813882839.9208415
3036491.27037403 13882801.001628
#Sta/Elev= 30
       0   119.6      20   120.6      85  117.27     115  118.68  253.55  118.75
  344.99  119.32  364.99  118.01  554.99  117.06  634.99  114.59  699.99  115.76
 1069.53  114.88 1119.98  113.01 1144.98  114.58 1159.51  113.31 1200.45  100.41
 1241.88   91.55 1276.71  105.15 1307.89  112.19 1327.13  111.21 1396.75  113.39
 1490.21  114.11 1581.76  115.48  1870.2  113.97 2146.76  114.35 2176.76  117.14
 2236.76  113.52 2261.76  115.51 2276.76  114.45 2371.76  115.74 2536.76  115.62
#Mann= 7 ,-1 , 0
       0      .1       0  253.55     .15       0 1069.53     .07       0
 1144.98     .04       0 1307.89     .07       0 1490.21     .15       0
  1870.2      .1       0
#XS Ineff= 2 ,-1
       0 1054.79     115 1415.23 2536.76     115
Permanent Ineff=
       F       F
Bank Sta=1144.98,1307.89
XS Rating Curve= 0 ,0
Exp/Cntr=0.4,0.2

Type RM Length L Ch R = 3 ,10037.26,,,
BEGIN DESCRIPTION:
12" PIPELINE
END DESCRIPTION:
Node Name=12" PIPELINE
Bridge Culvert--1,0,-1,-1, 0
Deck Dist Width WeirC Skew NumUp NumDn MinLoCord MaxHiCord MaxSubmerge Is_Ogee
11.5,1,2.6,0, 38, 38, , , 0.98, 0, 0,0,,
 1124.98 1129.98 1134.98 1139.98 1144.98 1149.98 1154.74 1159.51 1164.27 1169.04
 1173.81 1178.57 1183.34  1188.1 1192.87 1197.63  1202.4 1207.16 1211.93  1216.7
 1221.46 1226.23 1230.99 1240.52 1250.15 1254.96 1259.77 1264.58 1269.39  1274.2
 1279.02 1283.83 1288.64 1293.45 1298.26 1303.07 1307.89  1312.7
   113.2  113.37  116.83  116.83  116.83  116.83  116.83  116.83  116.83  116.84
  116.84  116.84  116.84  116.84  116.84  116.84  116.84  116.84  116.84  116.84
  116.84  116.84  116.84  116.85  116.85  116.85  116.85  116.85  116.85  116.85
  116.85  116.85  116.85  116.85  116.85  116.85  112.54  112.08
       0       0  115.83  115.83  115.83  115.83  115.83  115.83  115.83  115.84
  115.84  115.84  115.84  115.84  115.84  115.84  115.84  115.84  115.84  115.84
  115.84  115.84  115.84  115.85  115.85  115.85  115.85  115.85  115.85  115.85
  115.85  115.85  115.85  115.85  115.85  115.85       0       0
 1124.98 1129.98 1134.98 1139.98 1144.98 1149.98 1154.74 1159.51 1164.27 1169.04
 1173.81 1178.57 1183.34  1188.1 1192.87 1197.63  1202.4 1207.16 1211.93  1216.7
 1221.46 1226.23 1230.99 1240.52 1250.15 1254.96 1259.77 1264.58 1269.39  1274.2
 1279.02 1283.83 1288.64 1293.45 1298.26 1303.07 1307.89  1312.7
   113.2  113.37  116.83  116.83  116.83  116.83  116.83  116.83  116.83  116.84
  116.84  116.84  116.84  116.84  116.84  116.84  116.84  116.84  116.84  116.84
  116.84  116.84  116.84  116.85  116.85  116.85  116.85  116.85  116.85  116.85
  116.85  116.85  116.85  116.85  116.85  116.85  112.54  112.08
       0       0  115.83  115.83  115.83  115.83  115.83  115.83  115.83  115.84
  115.84  115.84  115.84  115.84  115.84  115.84  115.84  115.84  115.84  115.84
  115.84  115.84  115.84  115.85  115.85  115.85  115.85  115.85  115.85  115.85
  115.85  115.85  115.85  115.85  115.85  115.85       0       0
Pier Skew, UpSta & Num, DnSta & Num=  ,1129, 2 ,1129, 2 , 0 , 0 , 0 ,,
     1.6     1.6
      90   116.3
     1.6     1.6
      90   116.3
Pier Skew, UpSta & Num, DnSta & Num=  ,1165, 2 ,1165, 2 , 0 , 0 , 0 ,,
     1.6     1.6
      90   116.3
     1.6     1.6
      90   116.3
Pier Skew, UpSta & Num, DnSta & Num=  ,1198, 2 ,1198, 2 , 0 , 0 , 0 ,,
     1.6     1.6
      90   116.3
     1.6     1.6
      90   116.3
Pier Skew, UpSta & Num, DnSta & Num=  ,1240, 2 ,1240, 2 , 0 , 0 , 0 ,,
     1.6     1.6
      90   116.3
     1.6     1.6
      90   116.3
Pier Skew, UpSta & Num, DnSta & Num=  ,1255, 2 ,1255, 2 , 0 , 0 , 0 ,,
     1.6     1.6
      90   116.3
     1.6     1.6
      90   116.3
Pier Skew, UpSta & Num, DnSta & Num=  ,1305, 2 ,1305, 2 , 0 , 0 , 0 ,,
     1.6     1.6
      90   116.3
     1.6     1.6
      90   116.3
BR Coef=-1 , 1 , 1 ,0.9, 0 ,,,0.8,-1,1.2,0,
WSPro=,,,, 1 ,,,, 0 ,,,, 0 ,,,,-1 ,-1 ,-1 , 0 , 0 , 0 , 0 , 0
BC Design=,, 0 ,, 0 ,,,,,,
BC Use User HTab Curves=0
BC User HTab FreeFlow(D)= 0

Type RM Length L Ch R = 1 ,10025.62,17.57,16.21,19.37
BEGIN DESCRIPTION:
Downstream Section (12" PIPELINE)
END DESCRIPTION:
XS GIS Cut Line= 5
3039028.9250756113882868.88666293037879.8791453513882822.6029628
3037789.4049168713882818.95861313037693.2528781913882815.0855893
3036493.8842139413882776.1663758
#Sta/Elev= 30
       0  119.04      15  119.65      90  117.45     160  118.91  256.17   118.9
  619.99  116.58  639.99  114.84  659.99  114.82  679.99  116.49  907.25  115.12
 1034.98   114.1 1079.98  114.92 1114.98  113.28 1144.98   113.5 1159.51  111.95
 1202.06  100.41 1242.85   96.59 1243.49   91.55 1295.77  111.38 1303.07  112.34
 1322.32  110.74 1441.75  113.51 1491.96  113.25 1641.76  114.88 1869.43  113.76
 2141.76  114.04 2166.76   116.4 2241.76  113.85 2326.76  115.56 2536.76   115.5
#Mann= 7 ,-1 , 0
       0      .1       0  256.17     .15       0  907.25     .07       0
 1144.98     .04       0 1303.07     .07       0 1491.96     .15       0
 1869.43      .1       0
#XS Ineff= 2 ,-1
       0 1085.84     115 1374.52 2536.76     115
Permanent Ineff=
       F       F
Bank Sta=1144.98,1303.07
XS Rating Curve= 0 ,0
Exp/Cntr=0.5,0.3

Type RM Length L Ch R = 1 ,10009.41,130.54,130.5,133.41
BEGIN DESCRIPTION:
Upstream Section (FREEMAN (FM 529))
END DESCRIPTION:
XS GIS Cut Line= 6
 3039031.4096507 13882845.4621693037875.7538255313882804.8477489
3037791.4124587813882803.04755573037693.3939540213882798.7558976
3037168.7578641913882794.98261123036473.4026276213882770.0476217
#Sta/Elev= 30
       0  119.48   54.83  119.13    94.7  117.25  104.67  118.37   159.5  118.92
   258.6  118.48  479.94  116.08  553.26  115.08  752.64  115.72  961.98  113.16
 1056.68  113.48 1121.48  111.24 1151.39   108.9 1171.26   106.1 1205.09   97.89
 1215.26   94.17 1235.66   94.47 1294.69   106.7 1333.94  111.11 1373.82  112.42
 1493.67  113.19 1658.63  114.77 1870.97  113.73 2141.81  114.22 2156.72  114.49
 2166.66  116.02 2241.21  113.92 2330.67  115.73 2548.45  115.95 2559.29  115.89
#Mann= 8 ,-1 , 0
       0      .1       0   258.6     .15       0  479.94     .07       0
 1121.48     .04       0 1333.94     .07       0 1493.67     .15       0
 1870.97      .1       0 2548.45     .15       0
#XS Ineff= 2 ,-1
       0  1166.3   116.3 1275.07 2559.29  114.11
Permanent Ineff=
       F       F
Bank Sta=1121.48,1333.94
XS Rating Curve= 0 ,0
Exp/Cntr=0.5,0.3