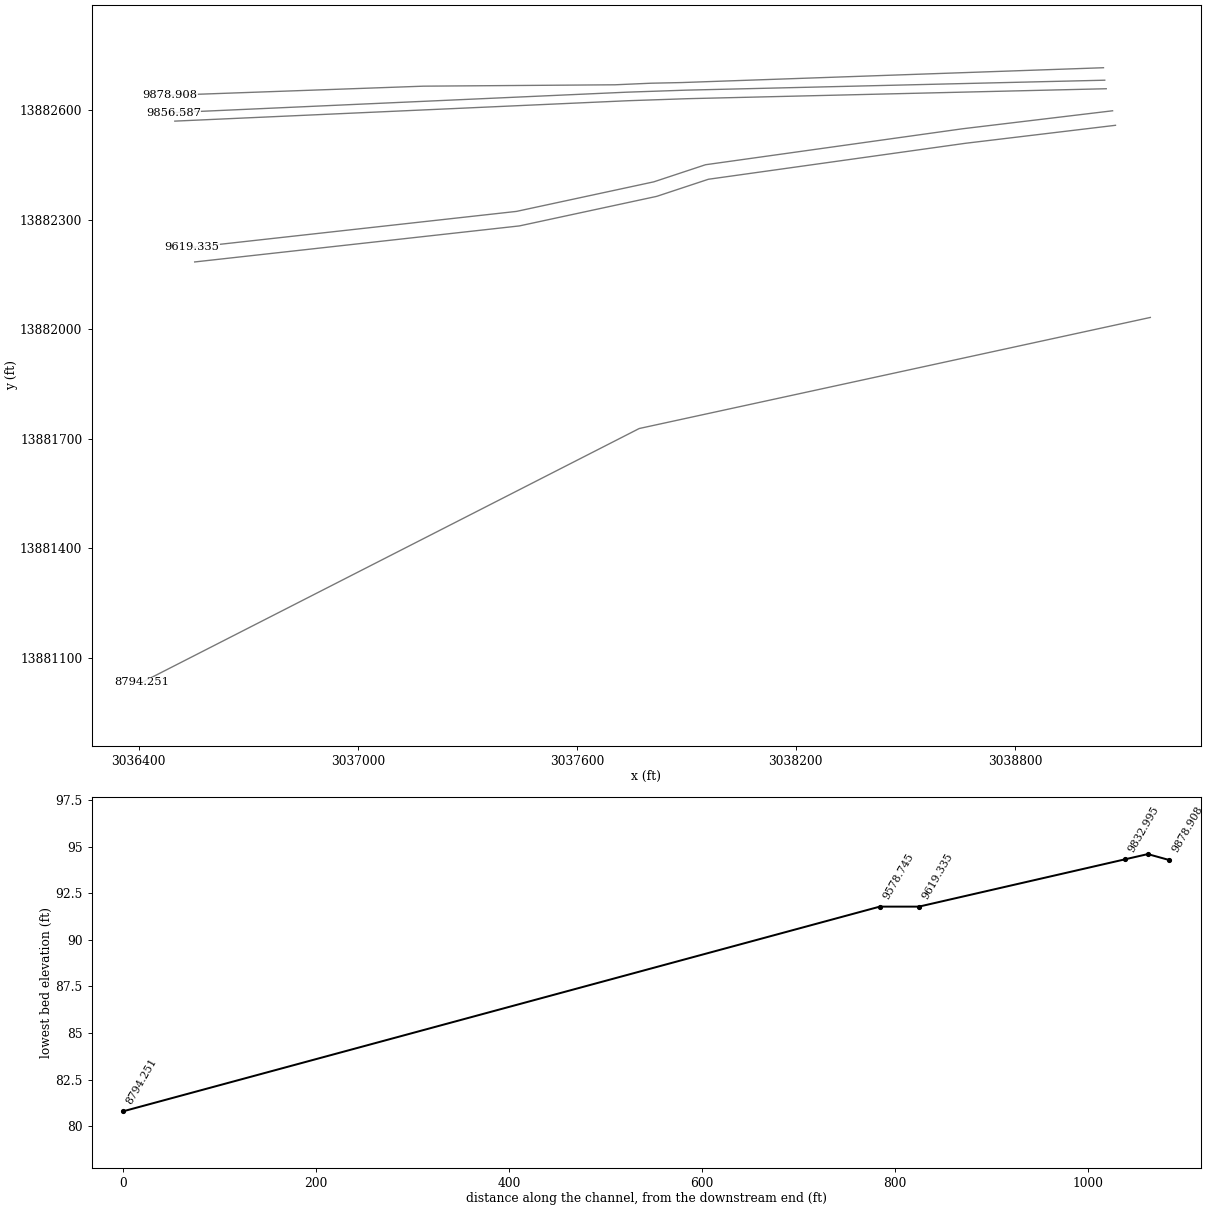
HEC-RAS study U106-00-00.prj: U106-00-00 2019 (Re-Study)

--- U106-00-00.g01 (geometry) --- (continued)

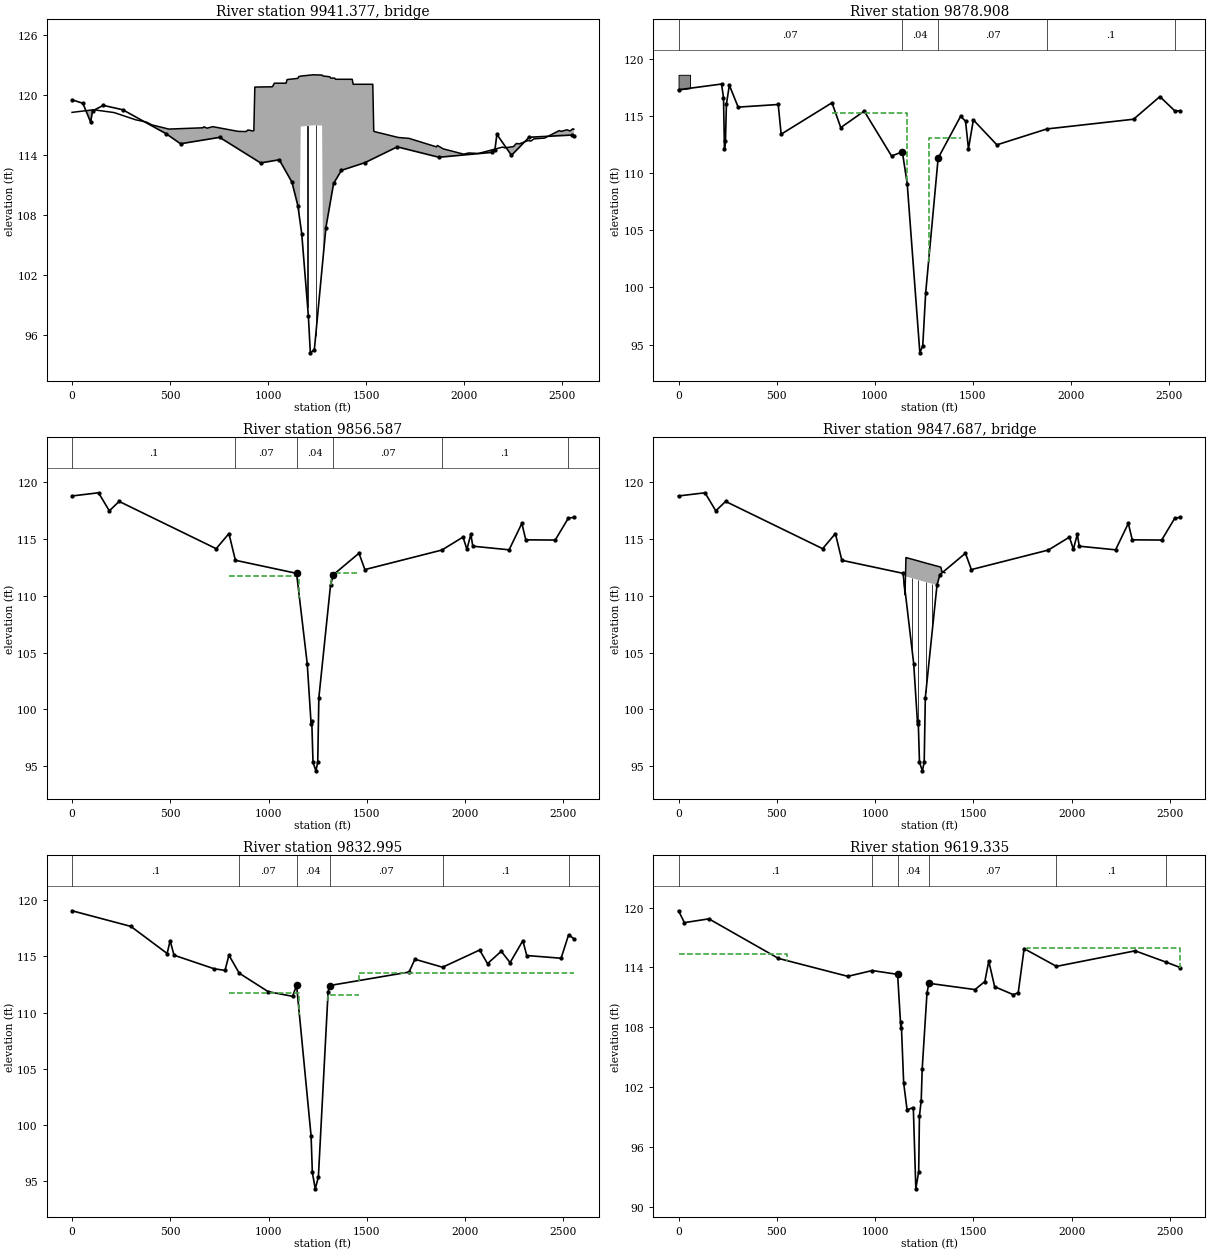
Type RM Length L Ch R = 3 ,9941.377,,,
BEGIN DESCRIPTION:
FREEMAN (FM 529)
END DESCRIPTION:
Node Name=FREEMAN (FM 529)
Bridge Culvert--1,0,-1,-1, 0
Deck Dist Width WeirC Skew NumUp NumDn MinLoCord MaxHiCord MaxSubmerge Is_Ogee
11.5,107,2.6,0, 60, 60, , , 0.98, 0, 0,0,,
       0  109.66  214.33  323.98  378.81  408.72  493.45   667.9  672.89  687.84
  717.75  847.34  887.22  897.18  922.11  927.09  932.07 1021.79 1031.76 1091.57
 1096.56 1151.39 1156.37 1161.33  1166.3 1230.81 1275.07 1279.98 1314.32 1319.22
 1338.84 1343.84 1428.78 1433.78 1533.71 1538.71 1543.71 1663.63 1718.59 1858.49
 1863.49 1893.31 1997.68 2022.53 2072.23 2196.48 2206.42 2251.15 2266.06 2280.97
  2325.7 2340.61 2355.52 2410.19 2484.74 2494.68  2524.5 2539.41 2554.32 2559.29
  118.22  118.48   118.2  117.48  117.25  116.96  116.55  116.68  116.78  116.64
  116.79  116.32   116.3  116.46  116.36   116.4  120.75  120.78  121.14  121.14
   121.5  121.62  121.81  121.81  121.85  121.98  121.95  121.86  121.78  121.65
  121.65  121.53  121.53  121.03  121.03  116.35  116.29  115.71  115.62  114.77
  114.91  114.57  114.04  114.16  114.11  114.75  114.67   114.8  115.11  115.07
   115.4  115.35  115.57  115.65   116.4  116.32  116.48  116.36  116.58  116.53
       0       0       0       0       0       0       0       0       0       0
       0       0       0       0       0       0       0       0       0       0
       0       0       0       0   116.8  116.93   116.9       0       0       0
       0       0       0       0       0       0       0       0       0       0
       0       0       0       0       0       0       0       0       0       0
       0       0       0       0       0       0       0       0       0       0
       0  109.66  214.33  323.98  378.81  408.72  493.45   667.9  672.89  687.84
  717.75  847.34  887.22  897.18  922.11  927.09  932.07 1021.79 1031.76 1091.57
 1096.56 1151.39 1156.37 1161.33  1166.3 1230.81 1275.07 1279.98 1314.32 1319.22
 1338.84 1343.84 1428.78 1433.78 1533.71 1538.71 1543.71 1663.63 1718.59 1858.49
 1863.49 1893.31 1997.68 2022.53 2072.23 2196.48 2206.42 2251.15 2266.06 2280.97
  2325.7 2340.61 2355.52 2410.19 2484.74 2494.68  2524.5 2539.41 2554.32 2559.29
  118.22  118.48   118.2  117.48  117.25  116.96  116.55  116.68  116.78  116.64
  116.79  116.32   116.3  116.46  116.36   116.4  120.75  120.78  121.14  121.14
   121.5  121.62  121.81  121.81  121.85  121.98  121.95  121.86  121.78  121.65
  121.65  121.53  121.53  121.03  121.03  116.35  116.29  115.71  115.62  114.77
  114.91  114.57  114.04  114.16  114.11  114.75  114.67   114.8  115.11  115.07
   115.4  115.35  115.57  115.65   116.4  116.32  116.48  116.36  116.58  116.53
       0       0       0       0       0       0       0       0       0       0
       0       0       0       0       0       0       0       0       0       0
       0       0       0       0   116.7  116.83   116.8       0       0       0
       0       0       0       0       0       0       0       0       0       0
       0       0       0       0       0       0       0       0       0       0
       0       0       0       0       0       0       0       0       0       0
Pier Skew, UpSta & Num, DnSta & Num=  ,1201.36, 2 ,1201.36, 2 , 0 , 0 , 0 ,,
     1.4     1.4
      90   117.9
     1.4     1.4
      90   117.9
Pier Skew, UpSta & Num, DnSta & Num=  ,1242.36, 2 ,1242.36, 2 , 0 , 0 , 0 ,,
     1.4     1.4
      90   117.9
     1.4     1.4
      90   117.9
Abutment Skew #Up #Dn= , 2 , 2
  1165.8  1167.8
   116.8  109.34
  1165.8  1167.8
   116.7  109.24
BR Coef=-1 , 1 , 1 ,0.9, 0 ,,,0.8,-1,1.2,0,
WSPro=,,,, 1 ,,,, 0 ,,,, 0 ,,,,-1 ,-1 ,-1 , 0 , 0 , 0 , 0 , 0
BC Design=,, 0 ,, 0 ,,,,,,
BC Use User HTab Curves=0
BC User HTab FreeFlow(D)= 0

Type RM Length L Ch R = 1 ,9878.908,30.88,22.32,22.55
BEGIN DESCRIPTION:
Downstream Section (FREEMAN (FM 529))
END DESCRIPTION:
Node Name=H
XS GIS Cut Line= 6
3039042.6671741213882715.55068343037887.0113489513882674.9362634
3037802.6699821913882673.13607013037704.65147744 13882668.844412
3037180.0153876113882665.07112563036484.6601510213882640.1361361
#Sta/Elev= 30
       0   117.3  219.31   117.8  229.28  116.62  234.26  112.12  239.25   112.8
  244.23  116.04  259.19   117.7  304.05  115.78   508.4  116.01  523.36  113.41
  782.54  116.16   827.4  113.99  947.03  115.43 1086.59   111.5 1141.42  111.87
  1166.3  109.08 1230.81   94.28 1245.64   94.91 1260.35    99.5 1324.13  111.32
 1438.78  114.98 1463.76  114.55 1478.75  112.13 1503.73  114.66 1623.65  112.48
 1878.61  113.87 2320.73  114.72 2454.92   116.7 2531.37  115.45 2559.29  115.45
#Mann= 5 ,-1 , 0
       0     .07       0 1141.42     .04       0 1324.13     .07       0
 1878.61      .1       0 2531.37     .07       0
#XS Ineff= 4 ,-1
       0  782.54  116.16  782.54  1166.3   115.3 1275.07 1438.78  113.11
 1438.78 2559.29  114.98
Permanent Ineff=
       F       F       F       F
#Block Obstruct= 2 , 0
       0   58.81  118.61 2454.92       0   116.7
Bank Sta=1141.42,1324.13
XS Rating Curve= 0 ,0
Exp/Cntr=0.5,0.3

Type RM Length L Ch R = 1 ,9856.587,27.69,23.59,27.09
BEGIN DESCRIPTION:
Upstream Section (20" PIPELINE)
END DESCRIPTION:
XS GIS Cut Line= 5
3039046.1750411113882681.39294343037899.1868495213882654.1571054
3037805.9058681113882650.96715123037736.46440594 13882648.592484
3036494.6853934413882592.7467952
#Sta/Elev= 30
       0  118.79  134.68  119.07  189.56  117.48  239.44  118.31  733.28  114.15
  798.13  115.48  830.89  113.13 1142.32  111.98 1196.54  104.03 1216.46   98.68
 1219.66   98.96 1225.96   95.34 1240.84    94.6 1249.95   95.37 1255.69  101.04
 1315.12  110.95  1330.1  111.87 1459.89  113.75 1489.85  112.31 1881.49  114.03
 1989.05  115.17 2009.02   114.1 2028.99  115.42 2038.98  114.37 2223.68  114.05
 2288.58  116.38 2308.55  114.93 2458.31  114.91 2524.72  116.83 2553.16  116.91
#Mann= 6 ,-1 , 0
       0      .1       0  830.89     .07       0 1142.32     .04       0
  1330.1     .07       0 1881.49      .1       0 2524.72     .07       0
#XS Ineff= 4 ,-1
       0  798.13  115.48  798.13 1157.14  111.71 1315.12 1459.89  112.03
 1459.89 2553.16  113.75
Permanent Ineff=
       F       F       F       F
Bank Sta=1142.32,1330.1
XS Rating Curve= 0 ,0
Exp/Cntr=0.4,0.2

Type RM Length L Ch R = 3 ,9847.687,,,
BEGIN DESCRIPTION:
20" PIPELINE
END DESCRIPTION:
Node Name=20" PIPELINE
Bridge Culvert--1,0,-1,-1, 0
Deck Dist Width WeirC Skew NumUp NumDn MinLoCord MaxHiCord MaxSubmerge Is_Ogee
6,1.6,2.6,0, 42, 42, , , 0.98, 0, 0,0,,
 1147.31 1152.22 1157.14 1162.05 1166.96 1171.87 1176.79  1181.7 1186.61 1191.52
 1196.44 1201.35 1206.26 1211.17 1216.09    1221 1225.91 1230.82 1235.74 1240.65
 1245.61 1250.57 1255.54  1260.5 1265.46 1270.43 1275.39 1280.35 1285.32 1290.28
 1295.24  1300.2 1305.17 1310.13 1315.12 1320.11 1325.11  1330.1 1335.09 1340.08
 1345.07 1355.06
  111.24   110.1  113.37  113.35  113.32   113.3  113.28  113.25  113.23  113.21
  113.18  113.16  113.14  113.11  113.09  113.07  113.04  113.02  112.99  112.97
  112.95  112.92   112.9  112.87  112.85  112.83   112.8  112.78  112.76  112.74
  112.71  112.69  112.66  112.64  112.62   112.6  112.57  112.55  112.52  112.12
  112.09  112.03
       0       0   111.7  111.68  111.65  111.63  111.61  111.58  111.56  111.54
  111.51  111.49  111.47  111.44  111.42   111.4  111.37  111.35  111.32   111.3
  111.28  111.25  111.23   111.2  111.18  111.16  111.13  111.11  111.09  111.07
  111.04  111.02  110.99  110.97  110.95  110.93   110.9  110.88  110.85       0
       0       0
 1147.31 1152.22 1157.14 1162.05 1166.96 1171.87 1176.79  1181.7 1186.61 1191.52
 1196.44 1201.35 1206.26 1211.17 1216.09    1221 1225.91 1230.82 1235.74 1240.65
 1245.61 1250.57 1255.54  1260.5 1265.46 1270.43 1275.39 1280.35 1285.32 1290.28
 1295.24  1300.2 1305.17 1310.13 1315.12 1320.11 1325.11  1330.1 1335.09 1340.08
 1345.07 1355.06
  111.24   110.1  113.37  113.35  113.32   113.3  113.28  113.25  113.23  113.21
  113.18  113.16  113.14  113.11  113.09  113.07  113.04  113.02  112.99  112.97
  112.95  112.92   112.9  112.87  112.85  112.83   112.8  112.78  112.76  112.74
  112.71  112.69  112.66  112.64  112.62   112.6  112.57  112.55  112.52  112.12
  112.09  112.03
       0       0   111.7  111.68  111.65  111.63  111.61  111.58  111.56  111.54
  111.51  111.49  111.47  111.44  111.42   111.4  111.37  111.35  111.32   111.3
  111.28  111.25  111.23   111.2  111.18  111.16  111.13  111.11  111.09  111.07
  111.04  111.02  110.99  110.97  110.95  110.93   110.9  110.88  110.85       0
       0       0
Pier Skew, UpSta & Num, DnSta & Num=  ,1156.14, 2 ,1156.14, 2 , 0 , 0 , 0 ,,
     1.4     1.4
      90   112.5
     1.4     1.4
      90   112.5
Pier Skew, UpSta & Num, DnSta & Num=  ,1187.84, 2 ,1187.84, 2 , 0 , 0 , 0 ,,
     1.4     1.4
      90   112.5
     1.4     1.4
      90   112.5
Pier Skew, UpSta & Num, DnSta & Num=  ,1219.34, 2 ,1219.34, 2 , 0 , 0 , 0 ,,
     1.4     1.4
      90   112.5
     1.4     1.4
      90   112.5
Pier Skew, UpSta & Num, DnSta & Num=  ,1258.64, 2 ,1258.64, 2 , 0 , 0 , 0 ,,
     1.4     1.4
      90   112.5
     1.4     1.4
      90   112.5
Pier Skew, UpSta & Num, DnSta & Num=  ,1291.34, 2 ,1291.34, 2 , 0 , 0 , 0 ,,
     1.4     1.4
      90   112.5
     1.4     1.4
      90   112.5
BR Coef=-1 , 1 , 1 ,0.9, 0 ,,,0.8,-1,1.2,0,
WSPro=,,,, 1 ,,,, 0 ,,,, 0 ,,,,-1 ,-1 ,-1 , 0 , 0 , 0 , 0 , 0
BC Design=,, 0 ,, 0 ,,,,,,
BC Use User HTab Curves=0
BC User HTab FreeFlow(D)= 0

Type RM Length L Ch R = 1 ,9832.995,192.07,213.66,231.44
BEGIN DESCRIPTION:
Downstream Section (20" PIPELINE)
END DESCRIPTION:
XS GIS Cut Line= 5
3039050.2609909513882658.03964363037903.2731274413882630.8038057
3037809.9918179413882627.61385143037740.5503557813882625.2391843
3036498.7716713513882569.3934954
#Sta/Elev= 30
       0  119.05   299.3  117.66  483.87  115.25  498.83   116.4  518.78   115.1
  723.31  113.89  778.18  113.75  798.13   115.1  850.46   113.5  997.66  111.86
 1122.37  111.44 1142.32  112.43  1216.2   99.01 1222.55   95.78 1237.37   94.32
 1253.24   95.37  1302.6  111.82 1310.13   112.4 1714.49   113.6 1744.44  114.74
 1885.14  114.03 2073.92  115.56 2113.86  114.35 2183.75  115.45 2228.67  114.44
 2293.57  116.39 2313.54  115.07 2488.26  114.83 2526.49  116.92 2553.16  116.56
#Mann= 6 ,-1 , 0
       0      .1       0  850.46     .07       0 1142.32     .04       0
 1310.13     .07       0 1885.14      .1       0 2526.49     .15       0
#XS Ineff= 4 ,-1
       0  798.13   115.1  798.13 1157.14  111.71  1300.2 1459.89   111.6
 1459.89 2553.16  113.51
Permanent Ineff=
       F       F       F       F
Bank Sta=1142.32,1310.13
XS Rating Curve= 0 ,0
Exp/Cntr=0.4,0.2

Type RM Length L Ch R = 1 ,9619.335,41.42,40.59,43.31
BEGIN DESCRIPTION:
Upstream Section (8.6" PIPELINE)
END DESCRIPTION:
XS GIS Cut Line= 6
3039067.6044601913882597.6959323 3038656.721423713882548.4732617
3037952.5010473613882449.99183133037810.9058581113882403.1933685
3037434.7573321913882322.28736243036545.2436912813882223.6504205
#Sta/Elev= 30
       0  119.69   29.91   118.5  154.56  118.88   508.3  114.91  861.35  113.11
  985.55  113.69 1114.95  113.31 1131.44  107.88 1133.52  108.48  1145.7  102.42
 1163.08   99.71 1194.84   99.94 1207.67   91.78 1222.21   93.52 1225.95   99.08
 1235.03  100.62 1240.06  103.81 1264.36  111.42 1274.02  112.41 1508.87  111.78
 1558.84  112.59 1578.83  114.63 1608.81  112.07 1703.77  111.27 1728.77  111.47
 1758.77  115.89 1923.32  114.11 2323.75  115.67 2483.33  114.52 2553.74  113.99
#Mann= 6 ,-1 , 0
       0      .1       0  985.55     .07       0 1114.95     .04       0
 1274.02     .07       0 1923.32      .1       0 2483.33     .15       0
#XS Ineff= 2 ,-1
       0  553.05  115.37 1773.77 2553.74  115.94
Permanent Ineff=
       F       F
Bank Sta=1114.95,1274.02
XS Rating Curve= 0 ,0
Exp/Cntr=0.4,0.2

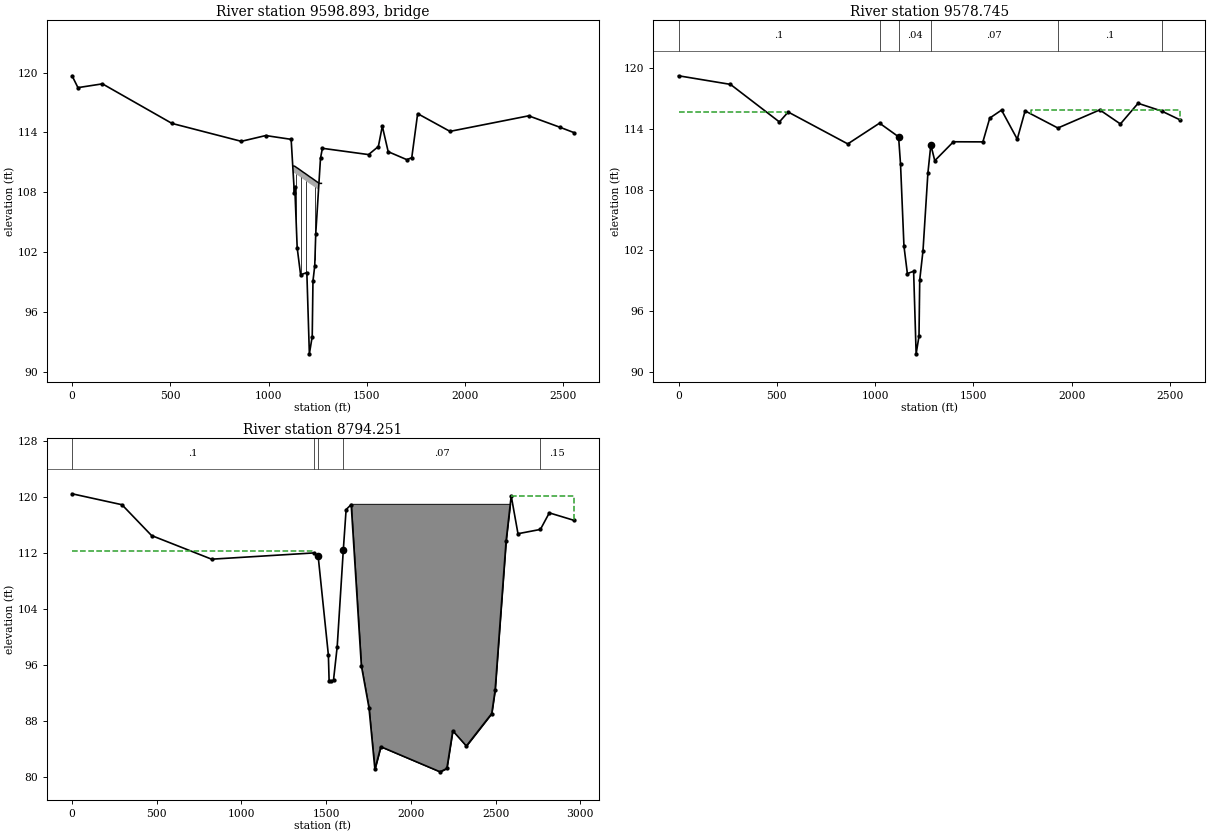
Type RM Length L Ch R = 3 ,9598.893,,,
BEGIN DESCRIPTION:
8.6" PIPELINE
END DESCRIPTION:
Node Name=8.6" PIPELINE
Bridge Culvert--1,0,-1,-1, 0
Deck Dist Width WeirC Skew NumUp NumDn MinLoCord MaxHiCord MaxSubmerge Is_Ogee
18.5,8.6,2.6,0, 30, 30, , , 0.98, 0, 0,0,,
  1124.9 1129.86 1134.82 1139.78 1144.74  1149.7 1154.66 1159.62 1164.58 1169.54
  1174.5 1179.46 1184.42 1189.38 1194.34  1199.3 1204.26 1209.22 1214.19 1219.17
 1224.16 1229.14 1234.13 1239.12  1244.1 1249.09 1254.08 1259.06 1264.05 1269.04
  110.63  110.63  110.59  110.52  110.45  110.39  110.32  110.25  110.18  110.11
  110.04  109.97  109.91  109.84  109.77   109.7  109.63  109.56  109.49  109.43
  109.36  109.29  109.22  109.15  109.08  109.01  108.94  108.89  108.89  108.89
  109.93  109.93  109.89  109.82  109.75  109.69  109.62  109.55  109.48  109.41
  109.34  109.27  109.21  109.14  109.07     109  108.93  108.86  108.79  108.73
  108.66  108.59  108.52  108.45  108.38  108.31  108.24  108.19  108.19  108.19
  1124.9 1129.86 1134.82 1139.78 1144.74  1149.7 1154.66 1159.62 1164.58 1169.54
  1174.5 1179.46 1184.42 1189.38 1194.34  1199.3 1204.26 1209.22 1214.19 1219.17
 1224.16 1229.14 1234.13 1239.12  1244.1 1249.09 1254.08 1259.06 1264.05 1269.04
  110.63  110.63  110.59  110.52  110.45  110.39  110.32  110.25  110.18  110.11
  110.04  109.97  109.91  109.84  109.77   109.7  109.63  109.56  109.49  109.43
  109.36  109.29  109.22  109.15  109.08  109.01  108.94  108.89  108.89  108.89
  109.93  109.93  109.89  109.82  109.75  109.69  109.62  109.55  109.48  109.41
  109.34  109.27  109.21  109.14  109.07     109  108.93  108.86  108.79  108.73
  108.66  108.59  108.52  108.45  108.38  108.31  108.24  108.19  108.19  108.19
Pier Skew, UpSta & Num, DnSta & Num=  ,1140, 2 ,1140, 2 , 0 , 0 , 0 ,,
      .7      .7
      90   109.8
      .7      .7
      90   109.8
Pier Skew, UpSta & Num, DnSta & Num=  ,1164, 2 ,1164, 2 , 0 , 0 , 0 ,,
      .7      .7
      90   109.8
      .7      .7
      90   109.8
Pier Skew, UpSta & Num, DnSta & Num=  ,1190, 2 ,1190, 2 , 0 , 0 , 0 ,,
      .7      .7
      90   109.8
      .7      .7
      90   109.8
Pier Skew, UpSta & Num, DnSta & Num=  ,1236, 2 ,1236, 2 , 0 , 0 , 0 ,,
      .7      .7
      90   109.8
      .7      .7
      90   109.8
BR Coef=-1 , 1 , 1 ,0.9, 0 ,,,0.8,-1,1.2,0,
WSPro=,,,, 1 ,,,, 0 ,,,, 0 ,,,,-1 ,-1 ,-1 , 0 , 0 , 0 , 0 , 0
BC Design=,, 0 ,, 0 ,,,,,,
BC Use User HTab Curves=0
BC User HTab FreeFlow(D)= 0

Type RM Length L Ch R = 1 ,9578.745,770.09,784.49,793.12
BEGIN DESCRIPTION:
Downstream Section (8.6" PIPELINE)
END DESCRIPTION:
Node Name=G
XS GIS Cut Line= 6
3039075.5811502813882557.95716663038664.69811378 13882508.734496
3037960.4777374413882410.2530657 3037818.882548213882363.4546029
3037442.7340222713882282.54859673036553.2203813613882183.9116549
#Sta/Elev= 30
       0  119.25  264.25   118.4  513.27  114.69  558.02  115.67  861.35  112.52
 1023.09  114.57 1119.92  113.22 1129.86  110.49 1147.23  102.42 1164.62   99.71
 1196.38   99.94  1209.2   91.78 1223.74   93.52 1227.48   99.08  1244.1  101.96
 1269.04  109.63 1284.02  112.43    1304  110.86 1398.94  112.73 1548.85  112.72
 1583.82  115.07 1643.78  115.86 1723.77  112.99 1763.77  115.78 1930.59  114.09
 2143.76  115.88 2248.75  114.49 2338.75  116.53 2458.02  115.77 2553.74  114.88
#Mann= 6 ,-1 , 0
       0      .1       0 1023.09     .07       0 1119.92     .04       0
 1284.02     .07       0 1930.59      .1       0 2458.02     .15       0
#XS Ineff= 2 ,-1
       0  548.08   115.7 1793.77 2553.74   115.9
Permanent Ineff=
       F       F
Bank Sta=1119.92,1284.02
XS Rating Curve= 0 ,0
Exp/Cntr=0.4,0.2

Type RM Length L Ch R = 1 ,8794.251,656.72,630.5,614.91
XS GIS Cut Line= 3
3039170.9999226913882031.99988523037771.00009802 13881727.999837
3036408.7807096113881033.1633002
#Sta/Elev= 30
       0  120.41  294.51  118.85  469.22  114.46  823.63  111.09 1425.56  111.98
 1452.62  111.49 1512.89   97.43 1517.14    93.8 1530.61   93.68 1543.16   93.86
 1564.96   98.64 1600.98   112.4 1617.53  118.16 1647.51  118.87 1707.48   95.92
 1752.46   89.92 1787.44   81.15 1822.42   84.37 2172.24   80.79 2212.22   81.28
  2247.2   86.64 2327.15   84.47 2477.07    89.1 2497.06   92.43 2562.03  113.73
 2592.01  120.11 2631.99  114.72 2764.29  115.33 2816.89  117.69 2961.81  116.63
#Mann= 5 ,-1 , 0
       0      .1       0 1425.56     .07       0 1452.62     .04       0
 1600.98     .07       0 2764.29     .15       0
#XS Ineff= 2 ,-1
       0 1417.65  112.23 2592.01 2961.81  120.11
Permanent Ineff=
       F       F
#Block Obstruct= 1 ,-1
 1642.52 2592.01  118.98
Bank Sta=1452.62,1600.98
XS Rating Curve= 0 ,0
Exp/Cntr=0.3,0.1