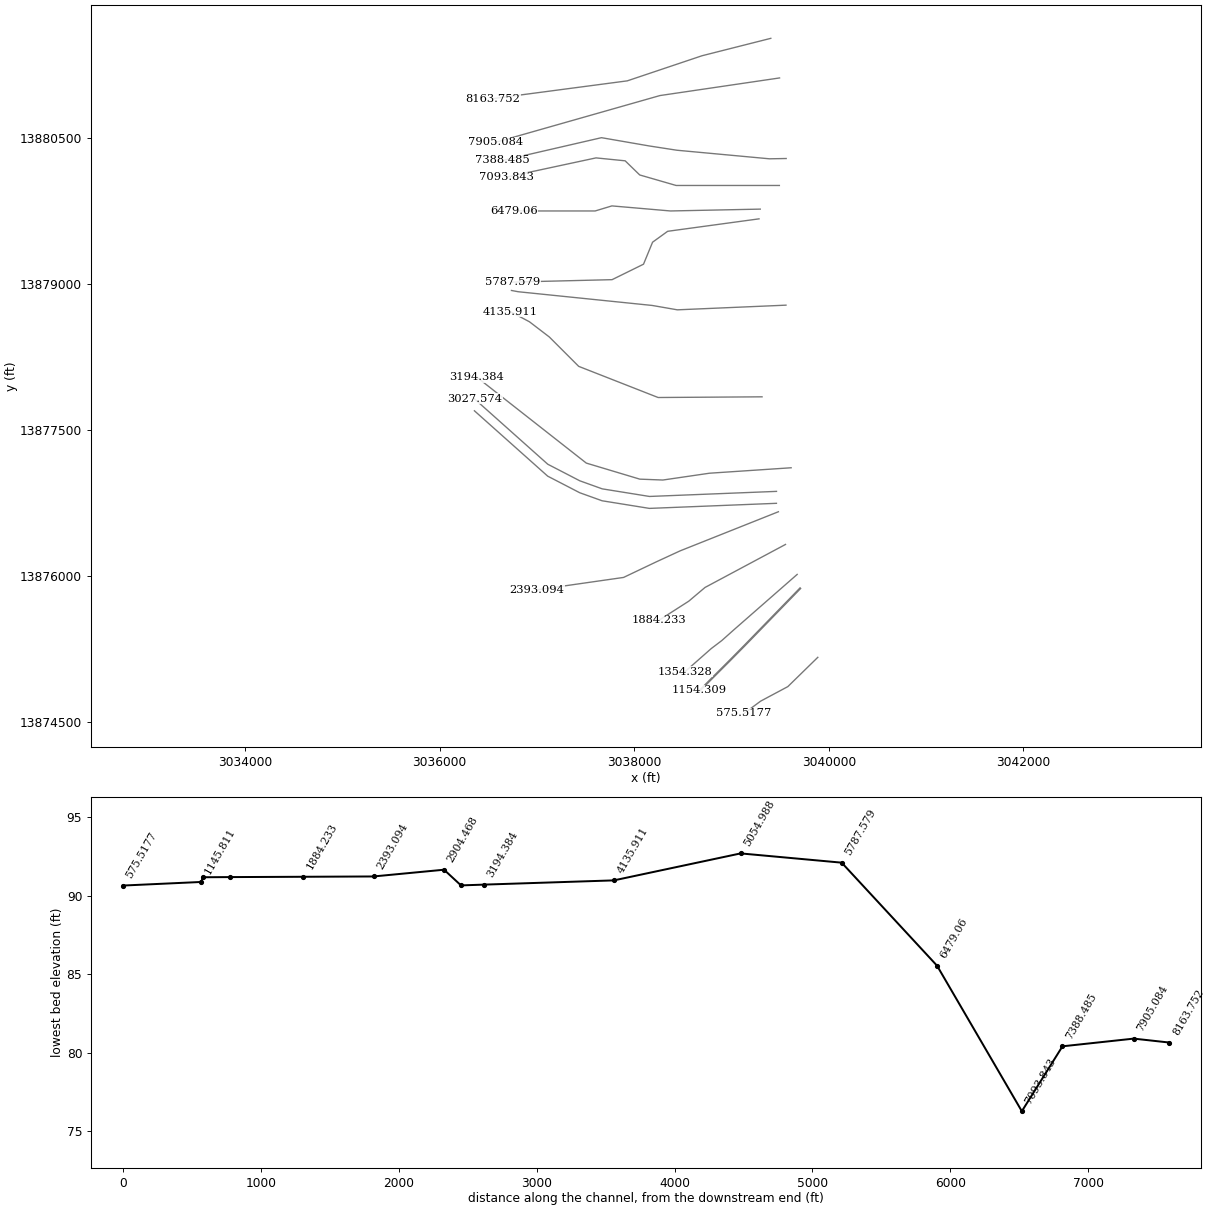
HEC-RAS study U106-00-00.prj: U106-00-00 2019 (Re-Study)

--- U106-00-00.g01 (geometry) --- (continued)

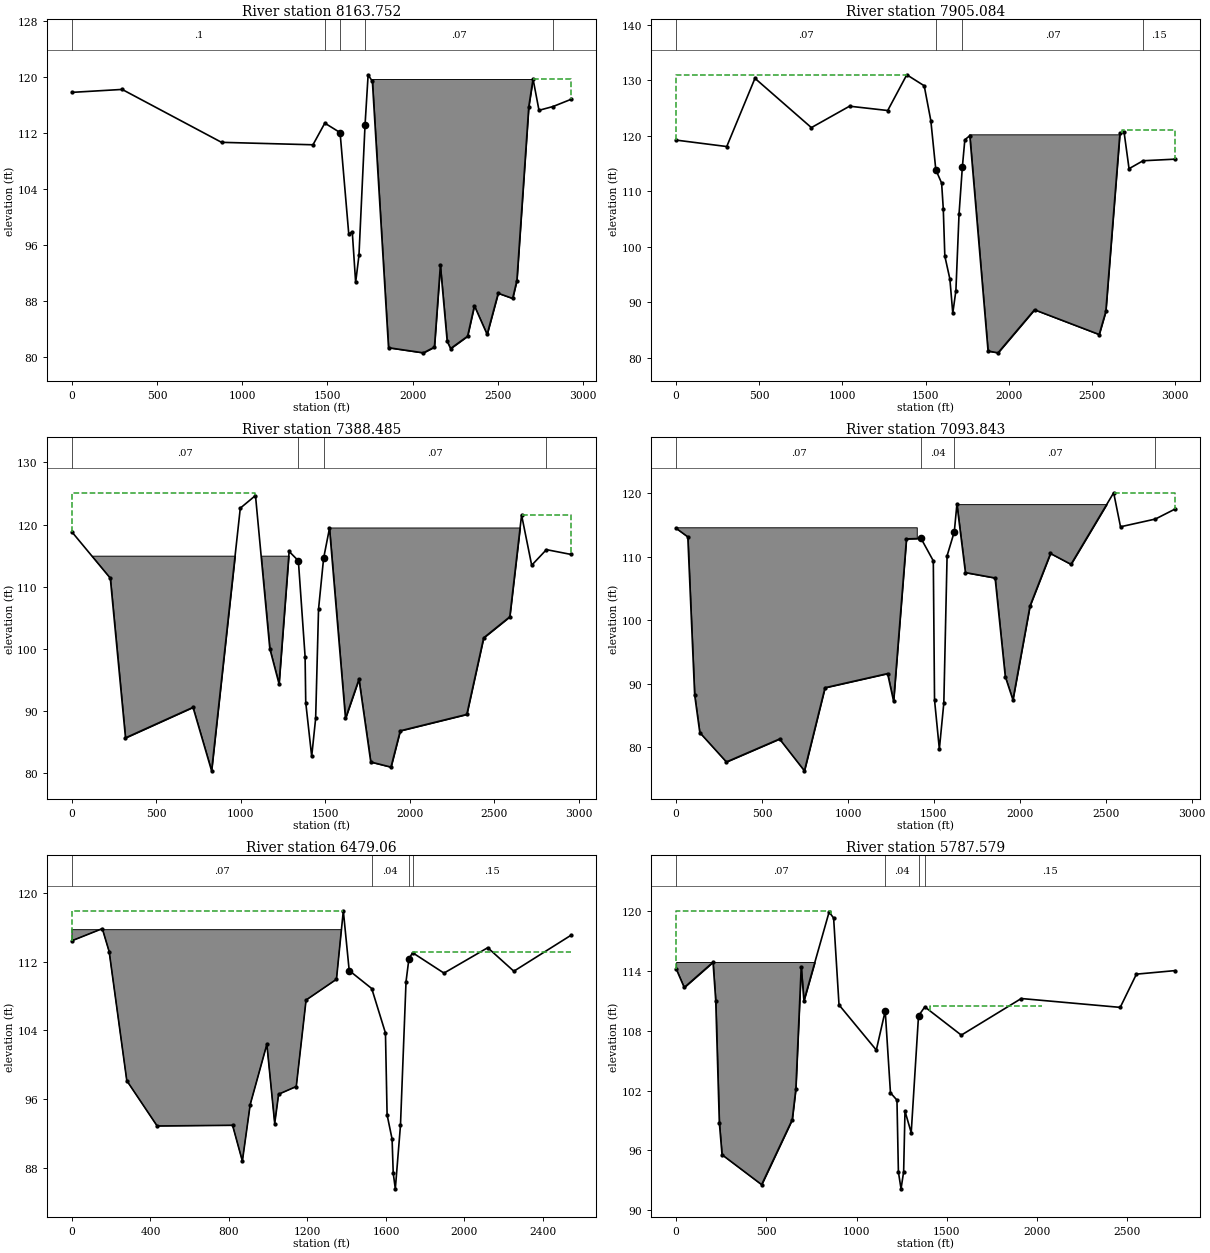
Type RM Length L Ch R = 1 ,8163.752,250.12,258.67,265.46
XS GIS Cut Line= 4
3039404.0001128613881520.99992293038696.9998864413881341.9999529
 3037929.000110113881084.00014083036548.3857453613880901.5103483
#Sta/Elev= 30
       0  117.82  294.72  118.24  878.42  110.69 1415.23  110.34 1484.81  113.43
 1574.43  112.08 1625.44   97.59 1645.98   97.93 1665.83    90.7 1685.28   94.55
 1720.86  113.11 1739.15  120.33  1764.1  119.38 1858.94   81.38 2063.59   80.65
 2128.48   81.47 2163.42   93.13 2203.35    82.3 2223.32   81.26 2323.15   83.02
 2363.08   87.37 2437.95   83.28 2502.84   89.15 2587.69   88.41 2612.65   90.97
 2682.53   115.8 2707.49  119.73 2742.43  115.26 2824.85   115.8  2932.1  116.84
#Mann= 5 ,-1 , 0
       0      .1       0 1484.81     .07       0 1574.43     .04       0
 1720.86     .07       0 2824.85     .15       0
#XS Ineff= 2 , 0
       0 1484.81  113.43 2707.49       0  119.73
Permanent Ineff=
       F       F
#Block Obstruct= 1 ,-1
 1759.11 2707.49  119.73
Bank Sta=1574.43,1720.86
XS Rating Curve= 0 ,0
Exp/Cntr=0.3,0.1

Type RM Length L Ch R = 1 ,7905.084,541.96,516.6,487.17
Node Name=F
XS GIS Cut Line= 3
3039493.9999328613881114.00008083038265.0000942813880933.0001147
3036571.9270368713880451.2829023
#Sta/Elev= 30
       0  119.23  304.33  118.07  473.95  130.36   813.2  121.48  1042.7  125.34
 1272.18  124.56 1386.87     131 1491.59  129.02 1531.48  122.73  1561.4  113.88
  1596.3  111.49 1606.28  106.87 1615.64   98.33  1645.9   94.21 1663.43   88.04
 1682.22   92.13 1701.02  105.87 1720.97  114.36 1735.93  119.29 1765.85  120.03
 1875.56   81.23 1935.39    80.9  2154.8   88.66 2543.76    84.2 2583.65   88.35
 2668.42  120.46 2693.35  120.68 2723.27  114.08 2807.43  115.51 3002.52   115.8
#Mann= 4 ,-1 , 0
       0     .07       0  1561.4     .04       0 1720.97     .07       0
 2807.43     .15       0
#XS Ineff= 2 , 0
       0 1386.87     131 2683.38       0  121.04
Permanent Ineff=
       F       F
#Block Obstruct= 1 ,-1
 1760.86 2678.39  120.27
Bank Sta=1561.4,1720.97
XS Rating Curve= 0 ,0
Exp/Cntr=0.3,0.1

Type RM Length L Ch R = 1 ,7388.485,319.44,294.64,244.01
XS GIS Cut Line= 6
3039562.0001249513880286.00009643039390.0001408613880283.0001024
3038440.0000723613880370.99992643038154.9999861913880414.9998384
3037663.9537241913880500.08857893036648.4360701913880265.8951497
#Sta/Elev= 30
       0  118.81  226.98  111.38  316.89   85.71   716.5   90.62  826.39   80.41
  996.22  122.64 1086.14  124.67 1170.85  100.06 1225.54   94.39  1285.2  115.68
 1339.89  114.18 1379.67   98.79 1383.54   91.39 1418.73   82.73 1442.14   88.84
 1459.33  106.42 1489.23  114.58 1524.11  119.41  1618.8   88.83 1698.54   95.15
 1768.31   81.83 1887.92   81.01 1942.76   86.84 2336.69   89.48 2436.42  101.79
    2591  105.17 2660.81  121.53 2720.64  113.46  2807.8  115.97 2955.01  115.19
#Mann= 4 ,-1 , 0
       0     .07       0 1339.89     .04       0 1489.23     .07       0
  2807.8     .15       0
#XS Ineff= 2 , 0
       0 1081.14  125.11 2660.81       0  121.53
Permanent Ineff=
       F       F
#Block Obstruct= 3 ,-1
       0 1016.21     115 1081.14 1305.09     115 1519.13 2660.81  119.53
Bank Sta=1339.89,1489.23
XS Rating Curve= 0 ,0
Exp/Cntr=0.3,0.1

Type RM Length L Ch R = 1 ,7093.843,544.54,614.78,760.11
XS GIS Cut Line= 6
3039491.9999368613880008.99999423038431.0000903613880008.9999942
3038056.9998541213880117.00010633037907.3055996913880262.3439757
3037607.7445190313880292.37902063036689.6334943613880095.2206223
#Sta/Elev= 30
       0   114.5   67.93  113.15  107.85   88.22   137.8   82.29   292.5   77.67
  601.89   81.29  746.61   76.27  866.38   89.37 1230.69    91.6 1265.62   87.24
 1340.49  112.83 1425.33   112.9 1496.65  109.37 1503.83   87.43 1531.83    79.7
 1557.88   86.97 1576.88  110.17 1618.87  113.96 1634.09  118.31 1683.61  107.52
 1856.35  106.67 1915.57   91.12 1959.99   87.46 2059.38  102.26 2178.63  110.53
 2297.89  108.82 2546.35   120.1 2586.16  114.74 2789.07  115.96 2906.07  117.57
#Mann= 4 ,-1 , 0
       0     .07       0 1425.33     .04       0 1618.87     .07       0
 2789.07     .15       0
#XS Ineff= 2 , 0
       0                 2546.35       0   120.1
Permanent Ineff=
       F       F
#Block Obstruct= 2 ,-1
       0 1400.38  114.66 1634.09 2546.35  118.31
Bank Sta=1425.33,1618.87
XS Rating Curve= 0 ,0
Exp/Cntr=0.3,0.1

Type RM Length L Ch R = 1 ,6479.06 ,603.47,691.48,738.79
Node Name=E
XS GIS Cut Line= 6
3039296.0000007713879766.00015213038372.99987827 13879746.999862
3037771.0000980213879799.00008613037599.00011395 13879746.999862
3036862.99994552 13879746.9998623036762.00014752 13879749.999856
#Sta/Elev= 30
       0  114.45   154.7  115.86  189.63  113.18  279.45   98.15  434.15   92.87
   818.4   92.95   868.3   88.78  908.23   95.37  993.11  102.38 1033.06   93.16
 1053.03   96.57 1142.92   97.47 1192.86  107.54 1347.66  109.96 1382.62  117.94
 1412.58  110.98 1527.44  108.88 1597.31   103.7 1605.69   94.17 1631.08   91.35
 1636.89   87.39 1647.55   85.55 1673.78   92.94 1702.13  109.69 1717.03  112.38
 1735.96  113.05 1895.43  110.68 2118.43  113.64 2251.43   110.9 2544.16  115.11
#Mann= 4 ,-1 , 0
       0     .07       0 1527.44     .04       0 1717.03     .07       0
 1735.96     .15       0
#XS Ineff= 2 , 0
       0 1382.62  117.94 1736.86       0  113.11
Permanent Ineff=
       F       F
#Block Obstruct= 1 ,-1
       0 1372.63  115.74
Bank Sta=1412.58,1717.03
XS Rating Curve= 0 ,0
Exp/Cntr=0.3,0.1

Type RM Length L Ch R = 1 ,5787.579,805.55,732.59,596.32
XS GIS Cut Line= 6
3039283.00002678 13879666.0000243038343.9999362813879537.9999519
3038188.9999181913879425.99984793038096.0001041913879199.9999718
3037773.0000940313879040.99996173036748.9998454513879016.0000117
#Sta/Elev= 30
       0  114.24   44.89  112.36   204.5   114.9  219.46  111.03  239.41   98.78
  254.38   95.55  473.84   92.54  643.43   99.07  663.38  102.14  693.31  114.43
  708.27  111.02  847.93  119.95  872.87  119.34  902.79  110.61 1109.49  106.07
 1158.86  110.01 1187.96  101.77 1223.92  101.04 1231.89   93.82 1246.52   92.12
 1260.96   93.84 1268.43   99.93 1302.95   97.76  1343.4  109.51 1378.31  110.41
 1580.57  107.57 1912.86  111.25 2461.36  110.36 2551.12   113.7 2767.67  114.06
#Mann= 4 ,-1 , 0
       0     .07       0 1158.86     .04       0  1343.4     .07       0
 1378.31     .15       0
#XS Ineff= 3 ,-1
       0   857.9  120.07   857.9 1158.86  110.01 1407.96 2027.54  110.48
Permanent Ineff=
       F       F       F
#Block Obstruct= 1 ,-1
       0  768.12  114.92
Bank Sta=1158.86,1343.4
XS Rating Curve= 0 ,0
Exp/Cntr=0.3,0.1

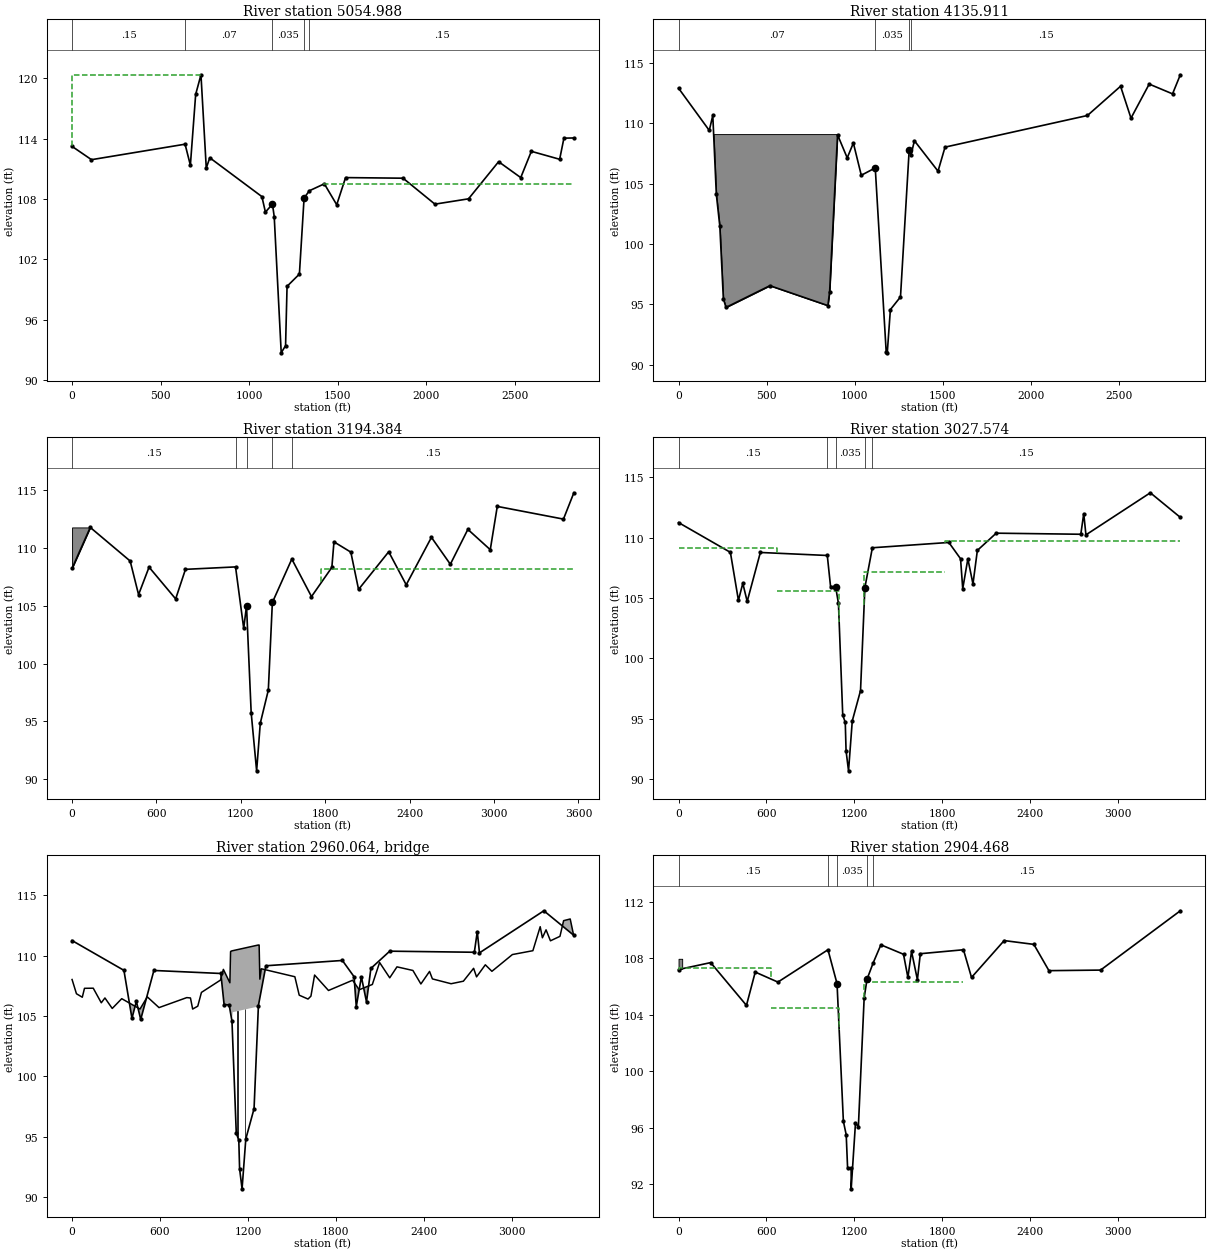
Type RM Length L Ch R = 1 ,5054.988,929.88,919.08,907.71
Node Name=D
XS GIS Cut Line= 5
3039560.0001289413878779.00015763038444.0000643613878730.9999255
3038184.9999261913878776.00016363036808.0000555213878916.9998816
3036738.9998654413878929.9998556
#Sta/Elev= 30
       0  113.23  109.71  111.91   638.3  113.45  668.22  111.36  698.14   118.4
  728.07  120.35  757.99  111.08  777.93   112.1 1072.15  108.24  1092.1   106.7
 1131.91  107.49 1141.83  106.25 1181.36   92.71 1205.94   93.43 1214.32   99.32
 1284.09  100.54 1310.47  108.09 1339.97  108.82 1424.89  109.51 1494.85  107.43
 1544.82  110.13 1869.63  110.07 2049.52  107.49 2239.41  108.02 2409.31  111.71
 2534.24  110.13  2594.2  112.74 2754.11  111.95 2778.14  114.05 2834.31  114.07
#Mann= 5 ,-1 , 0
       0     .15       0   638.3     .07       0 1131.91    .035       0
 1310.47     .07       0 1339.97     .15       0
#XS Ineff= 2 , 0
       0  728.07  120.35 1419.89       0  109.54
Permanent Ineff=
       F       F
Bank Sta=1131.91,1310.47
XS Rating Curve= 0 ,0
Exp/Cntr=0.3,0.1

Type RM Length L Ch R = 1 ,4135.911,875.76,941.53,968.83
XS GIS Cut Line= 6
3039313.9999647713877837.00007313038246.0001322813877830.0000871
3037430.0001238613878150.00010333037128.0000716913878452.0001554
 3036924.000151613878607.99984343036728.9998854413878711.9999635
#Sta/Elev= 30
       0   112.9  174.68   109.4  194.64  110.65   214.6  104.12  234.57  101.46
  254.53   95.48   269.5   94.75  519.04   96.55  848.43    94.9  858.41   96.05
  903.33  109.04  958.23  107.13  993.16  108.36 1038.08  105.69 1117.45   106.3
 1179.68   91.05 1185.72   90.99 1203.42   94.57 1260.85   95.62  1310.2  107.78
 1321.24  107.41 1339.86  108.55 1474.06  106.03 1513.86  108.02 2323.02  110.64
 2510.96  113.06 2570.23  110.42 2673.69  113.24 2806.29  112.43 2850.49  114.01
#Mann= 4 ,-1 , 0
       0     .07       0 1117.45    .035       0  1310.2     .07       0
 1321.24     .15       0
#XS Ineff= 2 , 0
       0  993.16  108.36 1339.86       0  108.55
Permanent Ineff=
       F       F
#Block Obstruct= 1 ,-1
  194.64  908.32   109.1
Bank Sta=1117.45,1310.2
XS Rating Curve= 0 ,0
Exp/Cntr=0.3,0.1

Type RM Length L Ch R = 1 ,3194.384,174.64,166.81,171.86
XS GIS Cut Line= 6
3039613.0000229513877107.99989073038774.0000605313877052.0000027
3038295.0000342713876982.00014273038057.9998521113876991.0001247
3037507.9999678613877156.00012283036382.9999212813878038.9999972
#Sta/Elev= 30
       0  108.25  129.36   111.8  412.97  108.89  472.68  105.98  547.31  108.36
  736.38  105.61  806.04  108.17 1162.03  108.38 1220.15  103.06 1240.11  105.01
 1273.22   95.75 1311.95   90.72 1337.92   94.84  1395.1   97.71 1423.77   105.3
 1562.12  109.06 1701.93  105.81 1846.74  108.34 1861.72  110.55 1981.55  109.66
 2036.48  106.43 2250.86  109.69 2375.34  106.83 2554.58  110.94 2689.02  108.61
 2813.49  111.63 2972.82  109.87 3022.61  113.62 3493.05  112.52 3567.03   114.8
#Mann= 5 ,-1 , 0
       0     .15       0 1162.03     .07       0 1240.11    .035       0
 1423.77     .07       0 1562.12     .15       0
#XS Ineff= 2 ,-1
       0  925.71     108 1771.84 3567.03  108.16
Permanent Ineff=
       F       F
#Block Obstruct= 2 , 0
       0  129.36   111.8               0
Bank Sta=1240.11,1423.77
XS Rating Curve= 0 ,0
Exp/Cntr=0.5,0.3

Type RM Length L Ch R = 1 ,3027.574,122.87,123.11,123.28
BEGIN DESCRIPTION:
Upstream Section (WEST LITTLE YORK)
END DESCRIPTION:
Node Name=C
XS GIS Cut Line= 6
 3039462.459969713876865.3297724 3038157.415335713876813.1313859
3037671.2913079413876891.37729243037441.2067943713876974.0080327
3037111.9157862813877144.42829553036358.9090901913877816.0972278
#Sta/Elev= 30
       0  111.26  353.86  108.79  408.69  104.81  438.59  106.22  468.52  104.72
  558.35  108.78 1015.16  108.53  1037.5  105.95 1072.07  105.92  1091.3  104.56
 1120.57   95.29 1137.83   94.69 1143.25   92.33 1160.09   90.67 1185.64   94.81
 1241.91   97.32 1271.65  105.87 1322.75  109.17 1844.65  109.61 1924.48  108.26
 1939.45  105.78 1974.37  108.25 2009.29  106.17 2039.23  108.95 2167.81  110.38
 2745.22  110.29 2765.19     112 2780.17  110.24 3219.59  113.73 3424.32  111.69
#Mann= 5 ,-1 , 0
       0     .15       0 1015.16     .07       0 1072.07    .035       0
 1271.65     .07       0 1322.75     .15       0
#XS Ineff= 4 ,-1
       0  673.15  109.16  673.15 1096.11  105.58 1266.72  1819.7  107.18
  1819.7 3424.32  109.73
Permanent Ineff=
       F       F       F       F
#Block Obstruct= 2 , 0
       0                 3289.49       0  113.69
Bank Sta=1072.07,1271.65
XS Rating Curve= 0 ,0
Exp/Cntr=0.5,0.3

Type RM Length L Ch R = 3 ,2960.064,,,
BEGIN DESCRIPTION:
WEST LITTLE YORK
END DESCRIPTION:
Node Name=WEST LITTLE YORK
Bridge Culvert--1,0,-1,-1, 0
Deck Dist Width WeirC Skew NumUp NumDn MinLoCord MaxHiCord MaxSubmerge Is_Ogee
18,92,2.6,0, 60, 60, , , 0.98, 0, 0,0,,
       0    29.9   69.78   84.73  144.54  199.36  224.28  274.12  338.91  463.52
  513.43  593.29  782.95  807.91  822.88  857.82  882.78 1012.54 1032.51 1076.88
 1081.69  1086.5 1096.11 1266.72 1271.65 1276.58 1281.51 1291.37  1520.3 1550.18
 1610.08 1630.04    1655 1749.84  1914.5  1959.4 2049.16  2098.6 2167.81 2217.25
 2326.01 2380.39 2439.48 2459.07 2586.39 2670.32 2740.23  2760.2 2820.12 2865.06
 3004.87 3144.69 3194.62  3209.6 3234.57 3264.53 3329.44 3354.41 3399.35 3424.32
  108.03  106.85  106.56   107.3  107.31   106.1   106.5  105.63  106.44  105.58
  106.59   105.7  106.53   106.5  105.58  105.82  106.96  107.98  108.87  107.76
  110.35  110.39  110.42  110.88  110.89  110.89  108.06  108.92  108.26  106.73
  106.41  106.65   108.4  107.12  107.97  107.18  107.62  109.44  108.17  109.08
  108.78  107.66   108.7  108.08  107.68  107.89  108.96  108.25  109.25  108.71
   110.1  110.42  112.41  111.49  112.15  111.24  111.61  112.91  113.05  111.61
       0       0       0       0       0       0       0       0       0       0
       0       0       0       0       0       0       0       0       0       0
       0       0  105.32  105.78       0       0       0       0       0       0
       0       0       0       0       0       0       0       0       0       0
       0       0       0       0       0       0       0       0       0       0
       0       0       0       0       0       0       0       0       0       0
       0    29.9   69.78   84.73  144.54  199.36  224.28  274.12  338.91  463.52
  513.43  593.29  782.95  807.91  822.88  857.82  882.78 1012.54 1032.51 1076.88
 1081.69  1086.5 1096.11 1266.72 1271.65 1276.58 1281.51 1291.37  1520.3 1550.18
 1610.08 1630.04    1655 1749.84  1914.5  1959.4 2049.16  2098.6 2167.81 2217.25
 2326.01 2380.39 2439.48 2459.07 2586.39 2670.32 2740.23  2760.2 2820.12 2865.06
 3004.87 3144.69 3194.62  3209.6 3234.57 3264.53 3329.44 3354.41 3399.35 3424.32
  108.03  106.85  106.56   107.3  107.31   106.1   106.5  105.63  106.44  105.58
  106.59   105.7  106.53   106.5  105.58  105.82  106.96  107.98  108.87  107.76
  110.35  110.39  110.42  110.88  110.89  110.89  108.06  108.92  108.26  106.73
  106.41  106.65   108.4  107.12  107.97  107.18  107.62  109.44  108.17  109.08
  108.78  107.66   108.7  108.08  107.68  107.89  108.96  108.25  109.25  108.71
   110.1  110.42  112.41  111.49  112.15  111.24  111.61  112.91  113.05  111.61
       0       0       0       0       0       0       0       0       0       0
       0       0       0       0       0       0       0       0       0       0
       0       0  105.22  105.68       0       0       0       0       0       0
       0       0       0       0       0       0       0       0       0       0
       0       0       0       0       0       0       0       0       0       0
       0       0       0       0       0       0       0       0       0       0
Pier Skew, UpSta & Num, DnSta & Num=  ,1129.29, 2 ,1129.29, 2 , 0 , 0 , 0 ,,
     1.4     1.4
      90   106.7
     1.4     1.4
      90   106.7
Pier Skew, UpSta & Num, DnSta & Num=  ,1182.29, 2 ,1182.29, 2 , 0 , 0 , 0 ,,
     1.4     1.4
      90   106.7
     1.4     1.4
      90   106.7
Abutment Skew #Up #Dn= , 2 , 2
 1089.89 1092.29
  105.31  104.39
 1089.89 1092.29
  105.21  104.29
Abutment Skew #Up #Dn= , 2 , 2
 1265.89 1268.28
  104.71  105.79
 1265.89 1268.28
  104.61  105.69
BR Coef=-1 , 1 , 1 ,0.9, 0 ,,,0.8,-1,1.2,0,
WSPro=,,,, 1 ,,,, 0 ,,,, 0 ,,,,-1 ,-1 ,-1 , 0 , 0 , 0 , 0 , 0
BC Design=,, 0 ,, 0 ,,,,,,
BC Use User HTab Curves=0
BC User HTab FreeFlow(D)= 0

Type RM Length L Ch R = 1 ,2904.468,480.96,511.37,549.69
BEGIN DESCRIPTION:
Downstream Section (WEST LITTLE YORK)
END DESCRIPTION:
Node Name=B
XS GIS Cut Line= 6
 3039461.794616713876742.6469468 3038156.749982713876690.4485604
3037670.6259549413876768.69446693037440.5414413713876851.3252072
3037111.25043328  13877021.745473036358.2437371913877693.4144023
#Sta/Elev= 30
       0   107.2  219.29  107.69  463.52  104.66  523.42  107.02  678.14  106.31
 1019.75   108.6 1081.69   106.2 1124.96   96.45  1144.2    95.5 1153.81   93.12
 1177.97   93.16 1178.13   91.67 1207.56   96.33 1227.28   96.07 1266.72  105.19
 1286.44  106.52 1328.31  107.67 1380.86  108.95 1535.24  108.28 1565.16  106.64
 1590.11  108.48 1630.04  106.48 1650.01  108.32 1944.44   108.6 1999.32  106.64
 2222.19  109.25 2424.79  108.98 2527.63  107.12 2880.04  107.16 3424.32  111.36
#Mann= 5 ,-1 , 0
       0     .15       0 1019.75     .07       0 1081.69    .035       0
 1286.44     .07       0 1328.31     .15       0
#XS Ineff= 4 ,-1
       0  628.23  107.32  628.23 1096.11   104.5 1266.72 1944.44   106.3
 1944.44 3424.32   108.6
Permanent Ineff=
       F       F       F       F
#Block Obstruct= 2 , 0
       0   24.82  107.96               0
Bank Sta=1081.69,1286.44
XS Rating Curve= 0 ,0
Exp/Cntr=0.5,0.3

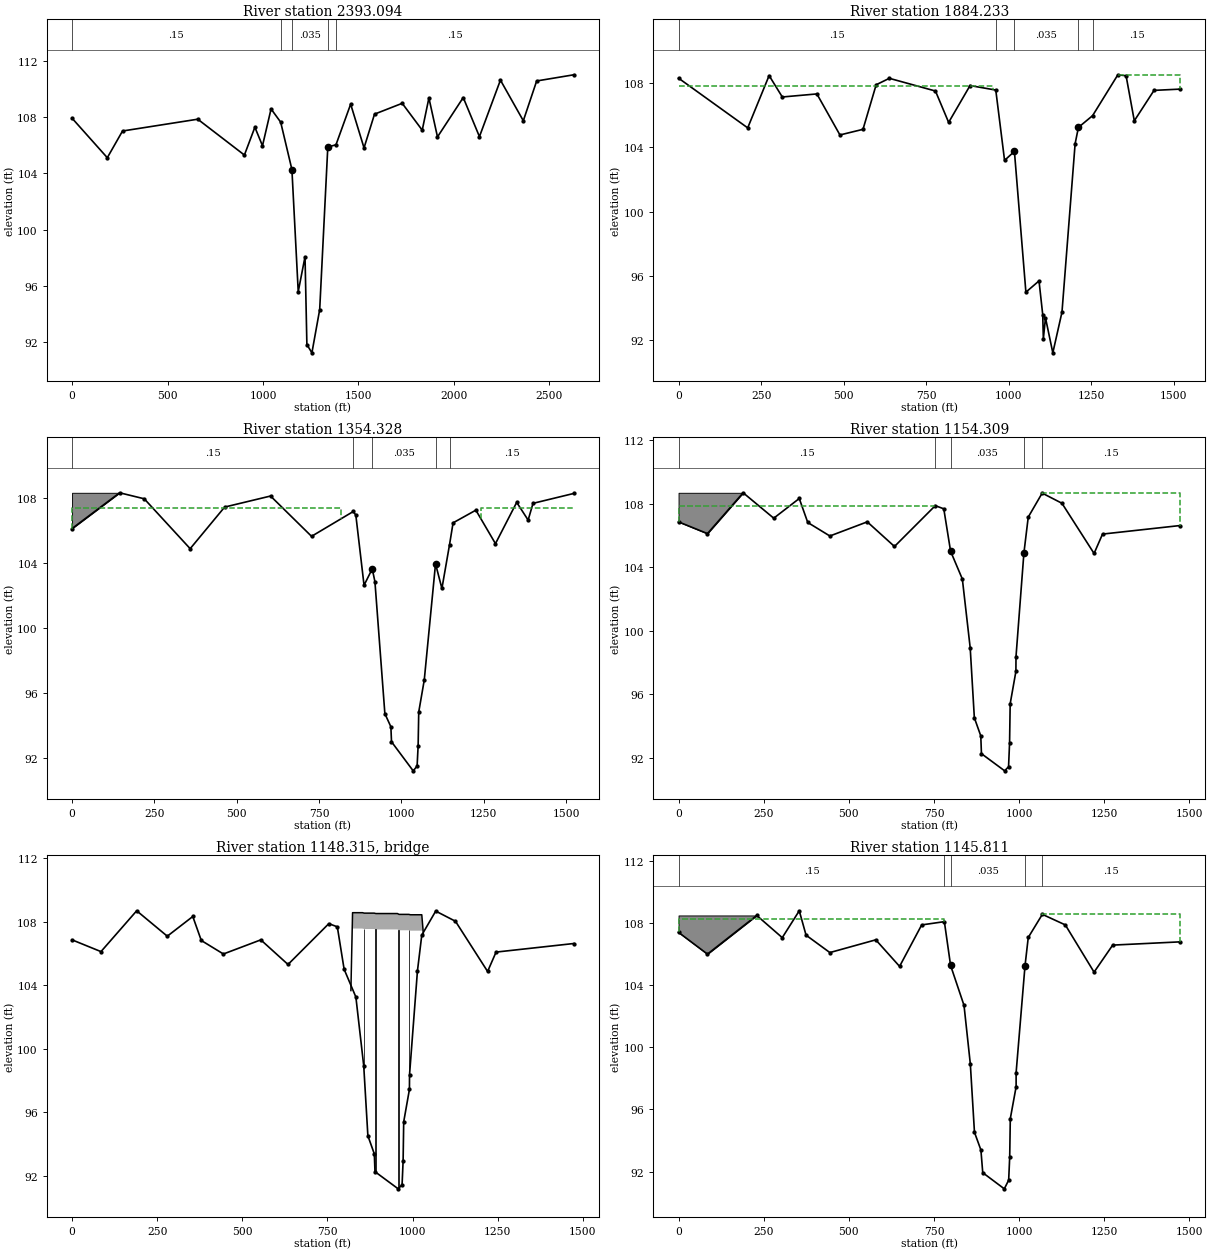
Type RM Length L Ch R = 1 ,2393.094,476.3,508.86,516.57
XS GIS Cut Line= 5
3039481.9999568613876656.00013853038472.0000083613876253.9999583
3038224.9998461913876139.99985823037890.9998580213875980.9998481
3037001.08201845 13875853.464342
#Sta/Elev= 30
       0  107.93   184.5  105.12  264.29  107.02  658.22  107.86  902.56  105.31
  957.41  107.29   997.3  105.97 1042.18  108.59 1092.56  107.65 1151.36  104.28
 1184.47   95.59 1220.06   98.08  1229.8   91.83 1256.11   91.24 1296.89   94.32
 1339.31  105.88 1382.15  106.04 1459.07  108.93 1529.06  105.82 1584.05  108.22
 1729.01  108.99  1833.9  107.08 1868.86  109.37 1913.81   106.6 2048.66   109.4
 2133.57  106.62 2243.44  110.64 2363.31  107.75 2433.23  110.58 2628.02  111.02
#Mann= 5 ,-1 , 0
       0     .15       0 1092.56     .07       0 1151.36    .035       0
 1339.31     .07       0 1382.15     .15       0
#XS Ineff= 2 ,-1
       0  658.22  107.86 2048.66 2628.02   109.4
Permanent Ineff=
       F       F
Bank Sta=1151.36,1339.31
XS Rating Curve= 0 ,0
Exp/Cntr=0.3,0.1

Type RM Length L Ch R = 1 ,1884.233,528.92,529.91,533.51
XS GIS Cut Line= 4
3039555.0001389413876320.00015433038728.0001525313875878.0000541
3038561.00015844 13875737.0000083038255.0001142813875541.0000719
#Sta/Elev= 30
       0  108.29  209.49   105.2  274.33  108.45  314.23  107.12  418.98  107.31
   488.8  104.76  558.63  105.11  598.54  107.88  638.44  108.28   778.1  107.49
     818  105.54  882.84  107.83  960.75  107.55  987.38  103.18 1017.18  103.74
 1051.96   94.99 1091.69   95.69  1102.9    93.6 1104.85   92.09 1111.29    93.4
  1133.5   91.22 1161.25   93.75 1201.07  104.22 1211.03  105.23 1253.96  105.96
  1330.5   108.5 1355.39  108.44 1380.28  105.64 1440.01  107.53 1519.66  107.61
#Mann= 5 ,-1 , 0
       0     .15       0  960.75     .07       0 1017.18    .035       0
 1211.03     .07       0 1253.96     .15       0
#XS Ineff= 2 , 0
       0  952.61  107.82  1330.5       0   108.5
Permanent Ineff=
       F       F
Bank Sta=1017.18,1211.03
XS Rating Curve= 0 ,0
Exp/Cntr=0.3,0.1

Type RM Length L Ch R = 1 ,1354.328,191.5,200.02,207.37
XS GIS Cut Line= 5
3039674.9998989413876012.00011423039018.9998986113875437.9999499
3038900.0001366113875332.00016193038792.0000245313875249.9999978
3038523.9999043613875014.0001417
#Sta/Elev= 30
       0  106.11  144.45  108.31  219.16  107.94  358.63  104.87  463.23  107.43
   602.7  108.11  727.22  105.63   854.1  107.16  861.71  106.93  886.61  102.62
  911.51  103.63  919.66  102.84  949.85   94.72  968.12   93.91  969.98   92.99
 1035.82    91.2 1047.74   91.49 1050.87   92.75  1052.7   94.82 1069.49   96.79
 1103.68  103.94 1123.05  102.42 1146.16  105.11 1156.95  106.46 1226.16  107.24
 1285.67  105.18 1350.15  107.72 1384.87  106.63 1399.75  107.66 1523.74  108.27
#Mann= 5 ,-1 , 0
       0     .15       0   854.1     .07       0  911.51    .035       0
 1103.68     .07       0 1146.16     .15       0
#XS Ineff= 2 , 0
       0  816.88  107.39 1241.04       0  107.36
Permanent Ineff=
       F       F
#Block Obstruct= 2 , 0
       0  144.45  108.31               0
Bank Sta=911.51,1103.68
XS Rating Curve= 0 ,0
Exp/Cntr=0.4,0.2

Type RM Length L Ch R = 1 ,1154.309,8.5,8.5,8.5
BEGIN DESCRIPTION:
Upstream Section (12" PIPELINE)
END DESCRIPTION:
XS GIS Cut Line= 5
3039704.2078457813875873.13982763039137.0052400213875289.5114017
3039044.3256353613875195.5627707 3038980.685342713875131.0514168
3038671.4891106913874822.2039374
#Sta/Elev= 30
       0  106.86   84.88  106.12  189.73  108.69   279.6  107.09   354.5  108.33
  379.46  106.82  444.37  105.97  554.21  106.86   634.1  105.31  753.93  107.88
  778.89  107.68  798.86  105.01  833.39  103.26  856.44   98.93  868.61   94.53
  887.52   93.39  889.46   92.27  957.62   91.19  969.06   91.45  972.07   92.95
  973.82   95.41  990.65   97.45   990.9   98.37 1014.14   104.9 1026.89  107.16
 1067.81  108.67 1125.82  108.03 1220.18  104.87 1245.01  106.09 1473.45  106.63
#Mann= 5 ,-1 , 0
       0     .15       0  753.93     .07       0  798.86    .035       0
 1014.14     .07       0 1067.81     .15       0
#XS Ineff= 2 , 0
       0  753.93  107.88 1066.23       0  108.67
Permanent Ineff=
       F       F
#Block Obstruct= 2 , 0
       0  189.73  108.69               0
Bank Sta=798.86,1014.14
XS Rating Curve= 0 ,0
Exp/Cntr=0.4,0.2

Type RM Length L Ch R = 3 ,1148.315,,,
BEGIN DESCRIPTION:
12" PIPELINE
END DESCRIPTION:
Node Name=12" PIPELINE
Bridge Culvert--1,0,-1,-1, 0
Deck Dist Width WeirC Skew NumUp NumDn MinLoCord MaxHiCord MaxSubmerge Is_Ogee
5.5,1,2.6,0, 45, 45, , , 0.98, 0, 0,0,,
  818.73  823.62  828.51  833.39  838.28  843.17  848.06  852.94  857.83  862.72
  867.61   872.5  877.38  882.27  887.16  892.05  896.93  901.82  906.71   911.6
  916.48  921.37  926.26  931.15  936.04  940.92  945.81  950.58  955.35  960.12
  964.89  969.66  974.43   979.2  983.97  988.74  993.51  998.27 1003.04 1007.81
 1012.58 1017.35 1022.12 1026.89 1031.66
  103.67  108.57  108.57  108.57  108.57  108.57  108.57  108.57108.5422108.5422
108.5422108.5422108.5422108.5422108.5422108.5159108.5159108.5159108.5159108.5159
108.5159108.5159108.5159108.5159108.5159108.5159108.5159108.5159108.5159108.4633
108.4633108.4633108.4633108.4633108.4633108.4633108.4394108.4394108.4394108.4394
108.4394108.4394108.4394108.4394  107.22
       0  107.57  107.57  107.57  107.57  107.57  107.57  107.57107.5422107.5422
107.5422107.5422107.5422107.5422107.5422107.5159107.5159107.5159107.5159107.5159
107.5159107.5159107.5159107.5159107.5159107.5159107.5159107.5159107.5159107.4633
107.4633107.4633107.4633107.4633107.4633107.4633107.4394107.4394107.4394107.4394
107.4394107.4394107.4394107.4394       0
  818.73  823.62  828.51  833.39  838.28  843.17  848.06  852.94  857.83  862.72
  867.61   872.5  877.38  882.27  887.16  892.05  896.93  901.82  906.71   911.6
  916.48  921.37  926.26  931.15  936.04  940.92  945.81  950.58  955.35  960.12
  964.89  969.66  974.43   979.2  983.97  988.74  993.51  998.27 1003.04 1007.81
 1012.58 1017.35 1022.12 1026.89 1031.66
  103.67  108.57  108.57  108.57  108.57  108.57  108.57  108.57108.5422108.5422
108.5422108.5422108.5422108.5422108.5422108.5159108.5159108.5159108.5159108.5159
108.5159108.5159108.5159108.5159108.5159108.5159108.5159108.5159108.5159108.4633
108.4633108.4633108.4633108.4633108.4633108.4633108.4394108.4394108.4394108.4394
108.4394108.4394108.4394108.4394  107.22
       0  107.57  107.57  107.57  107.57  107.57  107.57  107.57107.5422107.5422
107.5422107.5422107.5422107.5422107.5422107.5159107.5159107.5159107.5159107.5159
107.5159107.5159107.5159107.5159107.5159107.5159107.5159107.5159107.5159107.4633
107.4633107.4633107.4633107.4633107.4633107.4633107.4394107.4394107.4394107.4394
107.4394107.4394107.4394107.4394       0
Pier Skew, UpSta & Num, DnSta & Num=  ,821, 2 ,821, 2 , 0 , 0 , 0 ,,
     1.4     1.4
      90     108
     1.4     1.4
      90     108
Pier Skew, UpSta & Num, DnSta & Num=  ,857, 2 ,857, 2 , 0 , 0 , 0 ,,
     1.4     1.4
      90     108
     1.4     1.4
      90     108
Pier Skew, UpSta & Num, DnSta & Num=  ,891, 2 ,891, 2 , 0 , 0 , 0 ,,
     1.4     1.4
      90     108
     1.4     1.4
      90     108
Pier Skew, UpSta & Num, DnSta & Num=  ,959, 2 ,959, 2 , 0 , 0 , 0 ,,
     1.4     1.4
      90     108
     1.4     1.4
      90     108
Pier Skew, UpSta & Num, DnSta & Num=  ,990, 2 ,990, 2 , 0 , 0 , 0 ,,
     1.4     1.4
      90     108
     1.4     1.4
      90     108
BR Coef=-1 , 1 , 1 ,0.9, 0 ,,,0.8,-1,1.2,0,
WSPro=,,,, 1 ,,,, 0 ,,,, 0 ,,,,-1 ,-1 ,-1 , 0 , 0 , 0 , 0 , 0
BC Design=,, 0 ,, 0 ,,,,,,
BC Use User HTab Curves=0
BC User HTab FreeFlow(D)= 0

Type RM Length L Ch R = 1 ,1145.811,592.38,570.29,540.17
BEGIN DESCRIPTION:
Downstream Section (12" PIPELINE)
END DESCRIPTION:
XS GIS Cut Line= 5
3039710.5145916913875867.43314613039143.3119859413875283.8047202
3039050.6323812813875189.85608923038986.9920886213875125.3447353
3038677.7958566113874816.4972558
#Sta/Elev= 30
       0   107.4   84.88     106  229.67  108.49  304.57  107.06   354.5  108.79
  374.47  107.22  444.37   106.1  579.18  106.92  649.08  105.21  713.98  107.88
   780.6  108.09  798.86  105.27  838.28   102.7  856.81   98.93  868.98   94.53
  887.89   93.39  893.27   91.93  956.58   90.89  969.42   91.45  972.44   92.95
  974.19   95.41  991.27   97.46  991.27   98.37 1017.35  105.24 1026.89  107.07
 1068.28  108.56 1135.75  107.88 1220.18  104.84 1274.81  106.58 1473.45  106.79
#Mann= 5 ,-1 , 0
       0     .15       0   780.6     .07       0  798.86    .035       0
 1017.35     .07       0 1068.28     .15       0
#XS Ineff= 2 , 0
       0  778.89  108.24 1066.23       0  108.58
Permanent Ineff=
       F       F
#Block Obstruct= 2 , 0
       0  229.67  108.49               0
Bank Sta=798.86,1017.35
XS Rating Curve= 0 ,0
Exp/Cntr=0.4,0.2

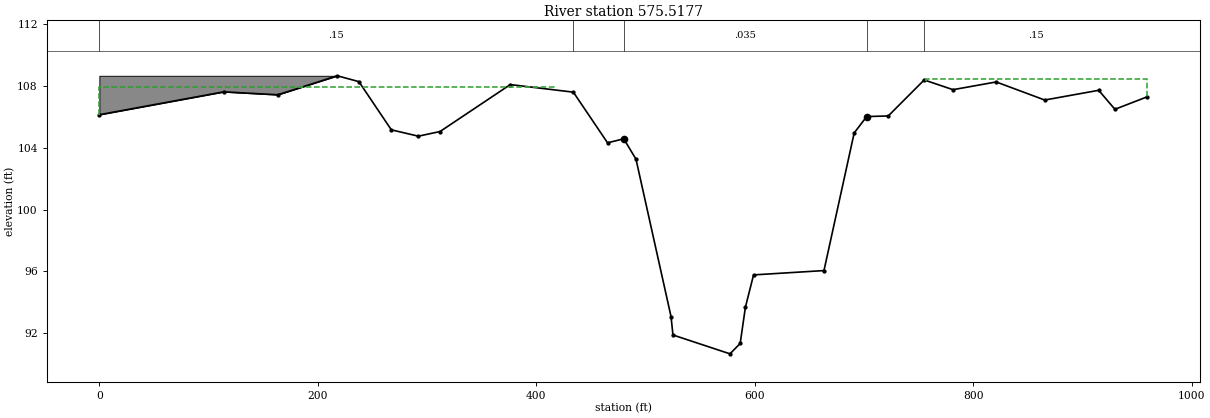
Type RM Length L Ch R = 1 ,575.5177,,,
Node Name=A
XS GIS Cut Line= 4
3039887.0001311213875159.99984973039579.0000909413874859.0001236
3039299.9999927713874710.00009353039129.0000066913874584.0000174
#Sta/Elev= 30
       0  106.14  113.85  107.62  163.35  107.43   217.8  108.66   237.6  108.28
   267.3  105.16  292.05  104.75  311.85  105.05  376.21  108.09  433.93   107.6
  465.25  104.32  480.08  104.58  491.28  103.26  523.37   93.07  525.12   91.88
  577.33   90.66  586.67   91.33  591.45   93.68  598.92   95.77  663.38   96.05
  691.04  104.96  702.47  106.02  722.24  106.06  755.14  108.39  781.53  107.76
  821.05  108.26   865.5  107.09   914.9  107.72  929.72  106.49  959.36   107.3
#Mann= 5 ,-1 , 0
       0     .15       0  433.93     .07       0  480.08    .035       0
  702.47     .07       0  755.14     .15       0
#XS Ineff= 2 , 0
       0  415.81  107.96  756.83       0  108.42
Permanent Ineff=
       F       F
#Block Obstruct= 2 , 0
       0   217.8  108.66  821.05       0  108.26
Bank Sta=480.08,702.47
XS Rating Curve= 0 ,0
Exp/Cntr=0.3,0.1

Chan Stop Cuts=-1
Use User Specified Reach Order=0
Composite Channel Slope=5